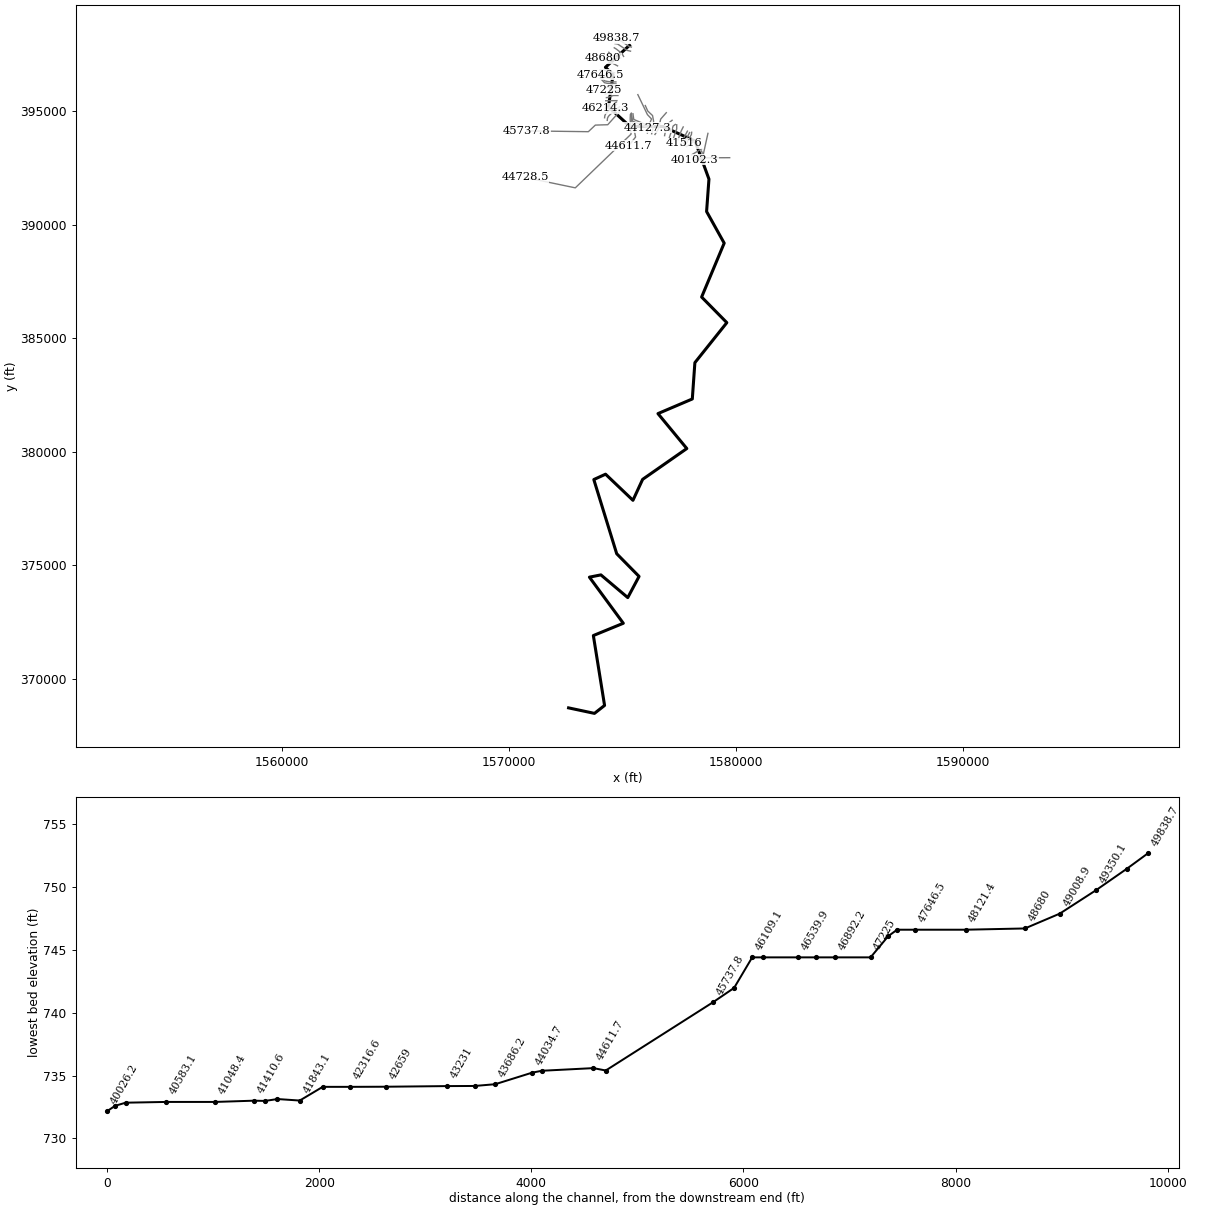
--- PTPLSCRK.prj (project) ---

Proj Title=PTPLSCRK
Current Plan=p01
Default Exp/Contr=0,0
English Units
Geom File=g01
Flow File=f01
Plan File=p01
BEGIN DESCRIPTION:
END DESCRIPTION:
DSS Export Rating Curves= 0
DSS Export Rating Curve Sorted= 0
DSS Export Volume Flow Curves= 0
DXF OffsetX= 0
DXF OffsetY= 0
DXF ScaleX= 0
DXF ScaleY= 0

--- PTPLSCRK.p01 (plan) ---

Plan Title=Floodplain
Program Version=4.00
Geom File=g01
Flow File=f01
K Sum by GR=0
Std Step Tol=0.01
Critical Tol=0.01
Num of Std Step Trials=20
Max Error Tol=0.3
Flow Tol Ratio=0.001
Split Flow NTrial=30
Split Flow Tol=0.02
Split Flow Ratio=0.02
Log Output Level=0
Friction Slope Method=1
Unsteady Friction Slope Method=2
Unsteady Bridges Friction Slope Method=1
Global Log Level=0
CheckData=False
Run HTab=0
Run UNet=0
Run PostProcess=0
UNET Theta=0
UNET Theta Warmup=0
UNET ZTol=0
UNET ZSATol=0
UNET MxIter=0
UNET MaxInSteps=0
UNET DtIC=0
UNET DtMin=0
UNET MaxCRTS=0
UNET WFStab=0
UNET SFStab=0
UNET WFX=0
UNET SFX=0
UNET DSS MLevel=0
UNET DZMax Abort=0
UNET Convert EG Bridges=0
UNET Use Existing IB Tables=0
UNET Froude Limit=0
UNET Froude Power=0
Write IC File=0
Echo Input=False
Echo Output=False
Write Detailed=0

--- PTPLSCRK.f01 (steady flow) ---

Flow Title=NFF Regression Equation
Program Version=4.10
Number of Profiles= 1
Profile Names=P100yr
River Rch & RM=PTPLSCRK,Main            ,49838.7
2137.191
River Rch & RM=PTPLSCRK,Main            ,44611.7
 3256.84
River Rch & RM=PTPLSCRK,Main            ,40201.9
 3525.14
River Rch & RM=PTPLSCRK,Main            ,30895.2
4569.702
River Rch & RM=PTPLSCRK,Main            ,23079.8
 7118.44
River Rch & RM=PTPLSCRK,Main            ,21923.9
8847.448
Boundary for River Rch & Prof#=PTPLSCRK,Main            , 1
Up Type= 0
Dn Type= 3
Dn Slope=0.0008
DSS Import GetInterval= 0
DSS Import GetPeak= 0
DSS Import FillOption= 0

--- PTPLSCRK.g01 (geometry) ---

Geom Title=USGS 10m DEM
Program Version=4.10

River Reach=PTPLSCRK        ,Main
Reach XY= 30
     1575323.114      397900.958     1574262.995      396932.748
     1574598.782      396611.191     1574398.906      395189.549
     1575342.739      394329.777     1576796.936      394325.143
     1578213.393      393681.604     1578824.098      392008.296
     1578719.975      390580.313     1579495.207      389187.784
     1578501.171      386813.268     1579612.161      385685.304
     1578204.234       383922.22     1578090.802      382323.276
     1576578.219      381678.558     1577848.432      380139.801
     1575902.423      378781.746     1575476.439      377858.928
     1574269.437      379009.681     1573752.075      378773.569
     1574760.756       375505.34     1575745.131      374506.208
     1575247.735      373573.917     1574064.575      374573.917
       1573558.6      374474.073     1575051.521      372442.982
     1573732.077       371902.01     1574225.827      368822.843
     1573781.382      368473.538     1572641.275      368715.932

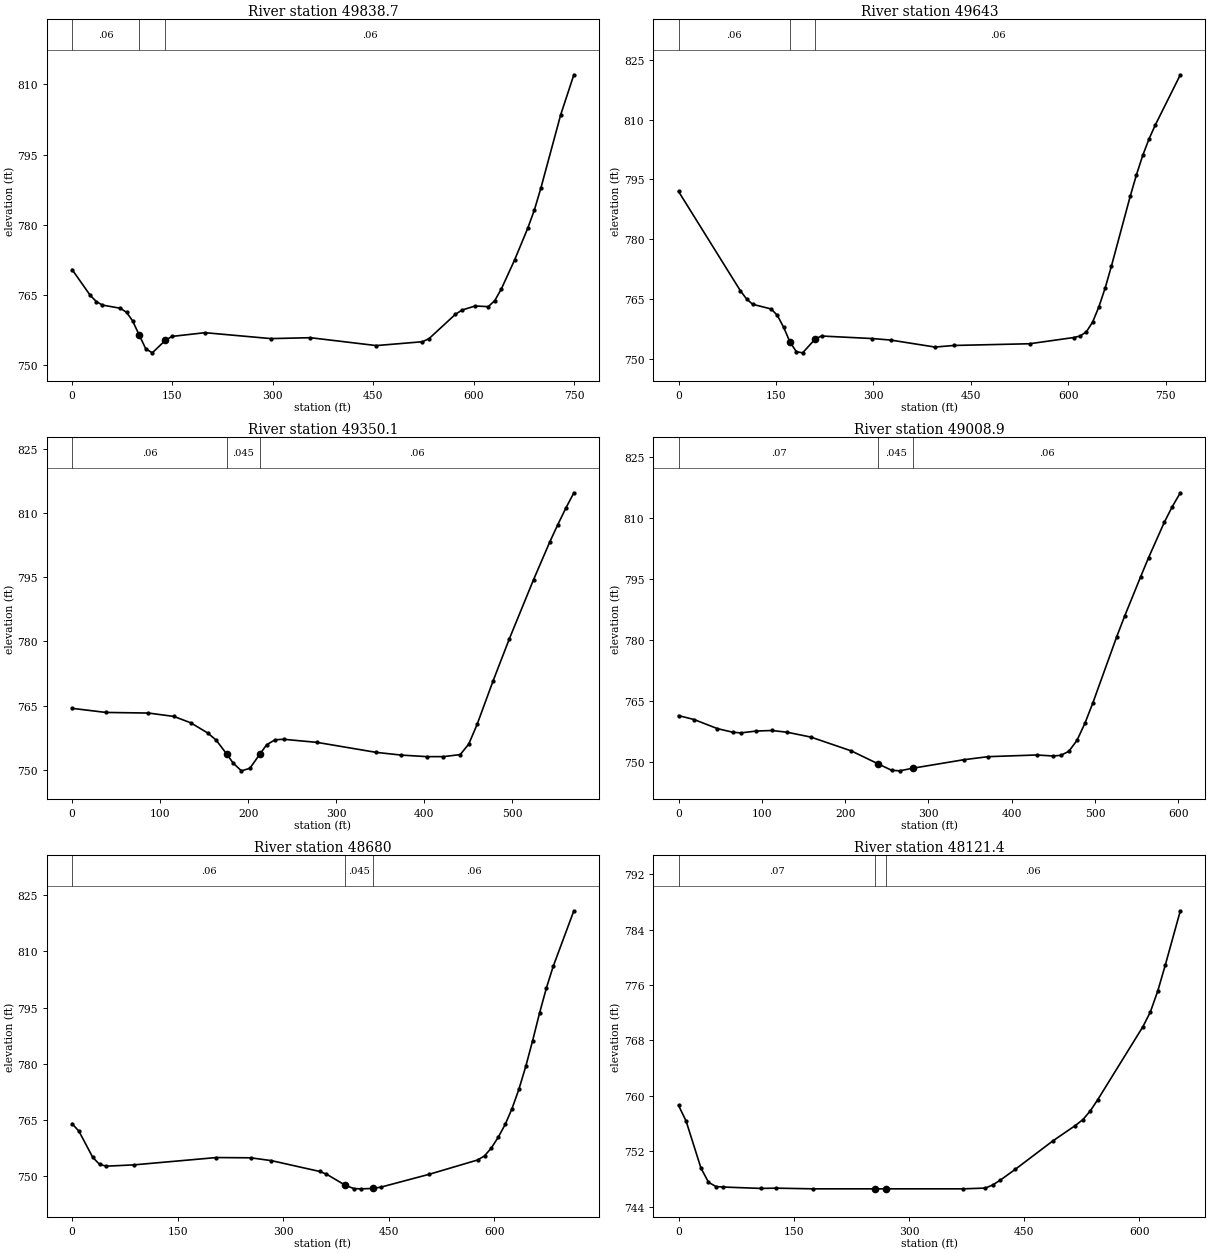
Type RM Length L Ch R = 1 ,49838.7 ,195.6,195.7,195.6
XS GIS Cut Line= 3
     1575408.094      397826.359     1575319.552      397844.588
     1574770.073      398209.171
#Sta/Elev= 30
       0  770.45    27.1  764.95    36.2  763.62    45.2  762.87    72.3  762.18
    81.4  761.31    90.4  759.51   100.2   756.5   110.1  753.53   119.9  752.67
   139.6  755.37   149.4  756.18   198.7  756.97   297.1  755.71   356.1   755.9
   454.6  754.22   523.5  755.04   533.3  755.69   572.7  760.88   582.5  761.79
   602.2  762.67   621.9  762.53   631.7  763.83   641.6  766.36   661.2  772.48
   680.9  779.27   690.8  783.16   700.6  787.88   730.1  803.47   749.8  812.02
#Mann= 3 , 0 , 0
       0     .06       0   100.2    .045       0   139.6     .06       0
Bank Sta=100.2,139.6
XS Rating Curve= 0 ,0
Exp/Cntr=0.3,0.1

Type RM Length L Ch R = 1 ,49643   ,294.2,292.9,290.6
XS GIS Cut Line= 4
     1575369.032      397644.067     1575220.594      397677.921
     1574801.323      397959.171      1574686.74      397974.796
#Sta/Elev= 30
       0  791.95    95.2  767.05   104.7  764.99   114.2  763.64   142.7  762.46
   152.2  760.86     162  757.82   171.7  754.15   181.4  751.75   191.1  751.46
   210.5  754.93   220.2  755.68   297.9  755.05     327  754.66     395  752.91
   424.1  753.31   540.6  753.74   608.6   755.3   618.3  755.67     628  756.72
   637.7  759.16   647.4  763.02   657.1  767.76   666.8  773.29   695.7  790.78
   705.3  796.16   714.9  800.99   724.6  805.13   734.2   808.6   772.8  821.22
#Mann= 3 , 0 , 0
       0     .06       0   171.7    .045       0   210.5     .06       0
Bank Sta=171.7,210.5
XS Rating Curve= 0 ,0
Exp/Cntr=0.3,0.1

Type RM Length L Ch R = 1 ,49350.1 ,337.2,341.2,343.8
XS GIS Cut Line= 4
     1575064.344      397412.296     1574986.219      397545.109
     1574746.636      397735.213     1574652.886      397792.505
#Sta/Elev= 30
       0  764.35    38.5  763.39    86.7  763.25   115.6  762.46   134.8  760.96
   154.1  758.58   163.6  756.92     176753.5634   182.8  751.58   192.3  749.74
   201.9  750.33     213 753.575     221  755.85   230.6     757   240.1  757.12
   278.3  756.39   345.2  754.06   373.9  753.42   402.6  753.06   421.7  753.06
   440.8  753.54   450.4  755.98   459.9  760.58   478.2  770.83   496.6  780.63
     524  794.42   542.3  803.17   551.5  807.27   560.6  811.12   569.8  814.74
#Mann= 3 , 0 , 0
       0     .06       0     176    .045       0     213     .06       0
Bank Sta=176,213
XS Rating Curve= 0 ,0
Exp/Cntr=0.3,0.1

Type RM Length L Ch R = 1 ,49008.9 ,327.8,328.9,329.2
XS GIS Cut Line= 4
     1574928.927      397344.588     1574770.073      397344.588
     1574491.427      397500.838     1574413.302      397597.192
#Sta/Elev= 30
       0  761.44    18.7  760.47    46.7  758.24    65.4  757.34    74.8  757.19
    93.4  757.65   112.1  757.78   130.8  757.34   158.9  756.16   207.3  752.78
     240749.5542   255.7  748.02   265.3  747.88     282748.5503   342.8  750.62
   371.8  751.36   429.9  751.77   449.3  751.53     459  751.68   468.6  752.68
   478.3  755.34   487.9  759.56   497.4  764.56     526  780.77   535.6  785.87
   554.7  795.49   564.2  800.16   583.3  808.94   592.8  812.75   602.4  816.12
#Mann= 3 , 0 , 0
       0     .07       0     240    .045       0     282     .06       0
Bank Sta=240,282
XS Rating Curve= 0 ,0
Exp/Cntr=0.3,0.1

Type RM Length L Ch R = 1 ,48680   ,565.4,558.6,560
XS GIS Cut Line= 2
     1574798.719       396995.63     1574168.511      397328.963
#Sta/Elev= 30
       0  764.07     9.8  762.05    29.3  755.12    39.1   753.2    48.8  752.74
    87.9  753.09   205.1  755.04   253.9  754.97   283.2  754.22   351.6  751.34
   361.4  750.62     388747.6729   400.4  746.76   410.2   746.7     428746.7983
   439.5  747.19   507.8   750.6   576.2  754.39     586  755.48   595.7   757.6
   605.5  760.48   615.3  763.85     625  768.07   634.8  773.23   644.6  779.35
   654.3  786.18   664.1  793.51   673.9  800.24   683.6  806.02   712.9  820.81
#Mann= 3 , 0 , 0
       0     .06       0     388    .045       0     428     .06       0
Bank Sta=388,428
XS Rating Curve= 0 ,0
Exp/Cntr=0.3,0.1

Type RM Length L Ch R = 1 ,48121.4 ,460.9,475,476
XS GIS Cut Line= 3
     1574665.907      396693.546     1574184.136      396815.942
     1574027.886      396815.942
#Sta/Elev= 26
       0  758.63     9.8  756.39    29.2  749.59      39  747.55    48.7  746.93
    58.5  746.86   107.2  746.66   126.7   746.7   175.4   746.6   255.3   746.6
   270.3   746.6   370.4   746.6   399.6  746.71   409.4  747.18   419.1  747.87
   438.6  749.43   487.3  753.51   516.6  755.73   526.4  756.58   536.1  757.84
   545.9  759.48   604.5  769.97   614.3  772.11     624  775.16   633.8   778.9
   653.3   786.7
#Mann= 3 , 0 , 0
       0     .07       0   255.3    .045       0   270.3     .06       0
Bank Sta=255.3,270.3
XS Rating Curve= 0 ,0
Exp/Cntr=0.3,0.1

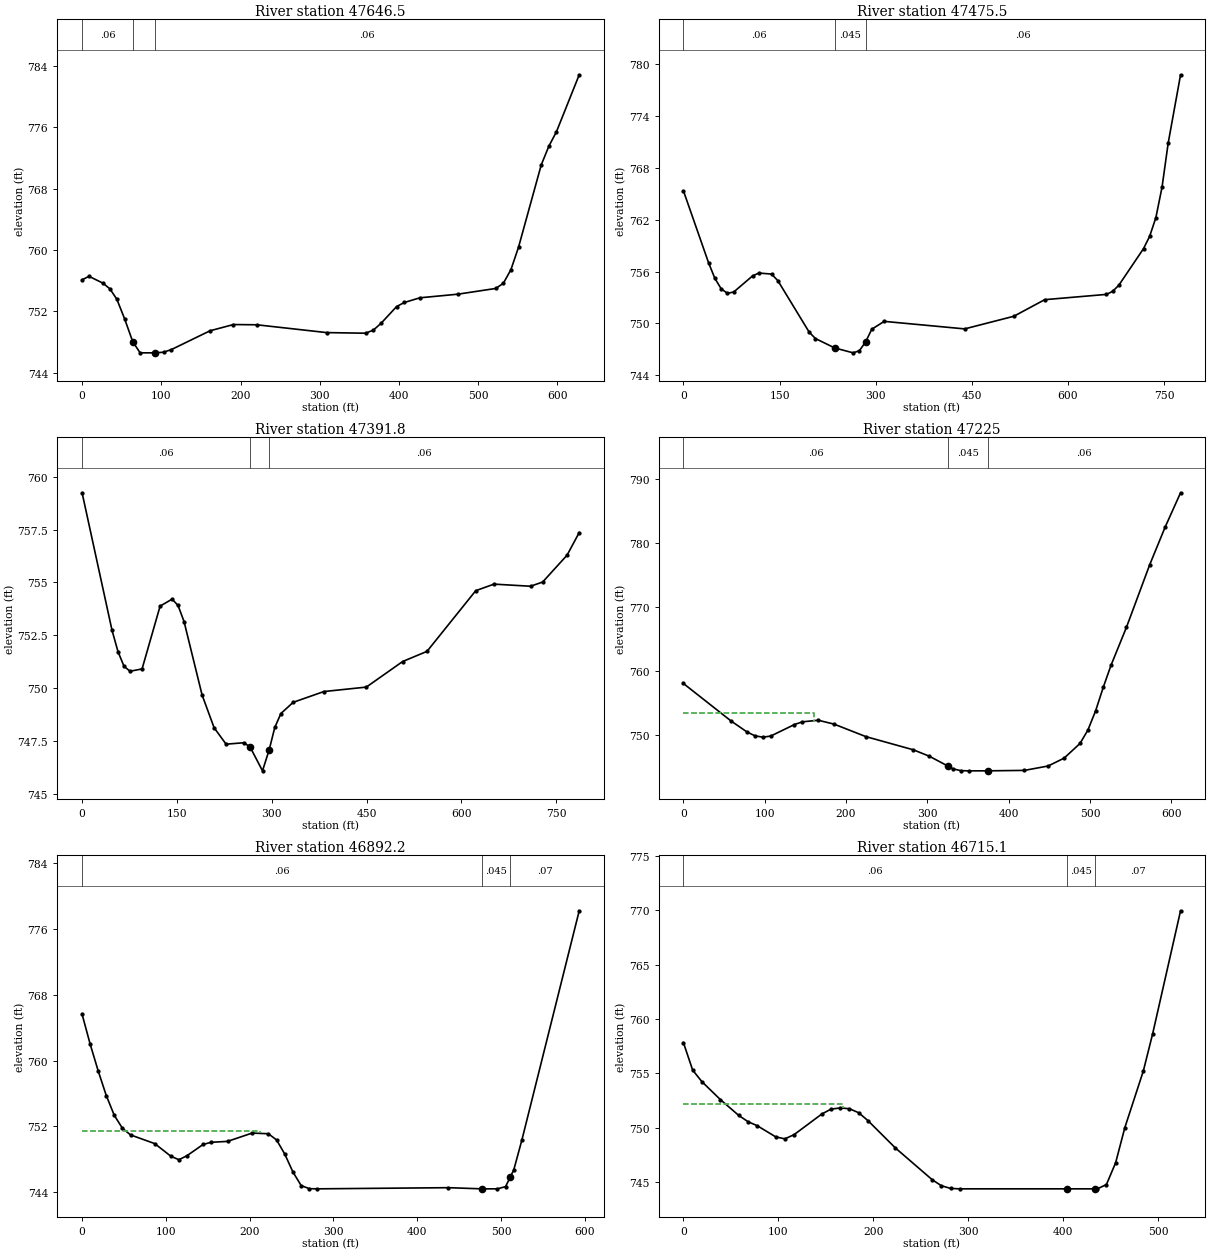
Type RM Length L Ch R = 1 ,47646.5 ,132.1,171,175.5
XS GIS Cut Line= 4
     1574632.921      396415.769     1574589.518      396409.258
     1574218.424      396502.574     1574049.153      396611.081
#Sta/Elev= 30
       0  756.13     8.8  756.58    26.3  755.69    35.1  754.95    43.9  753.59
    53.7  751.03      64748.0427    73.3   746.6      92   746.6   102.8  746.68
   112.6  747.02   161.6  749.48   191.1  750.29   220.5  750.26   308.8  749.24
   357.8  749.16   367.7  749.56   377.5  750.46   397.1  752.64   406.9  753.17
   426.5  753.78   474.4  754.25   522.3     755   531.8  755.67   541.4  757.45
     551  760.39   579.7  771.13   589.3  773.56   598.9  775.45   627.6  782.87
#Mann= 3 , 0 , 0
       0     .06       0      64    .045       0      92     .06       0
Bank Sta=64,92
XS Rating Curve= 0 ,0
Exp/Cntr=0.3,0.1

Type RM Length L Ch R = 1 ,47475.5 ,117.6,83.6,81.2
XS GIS Cut Line= 5
     1574726.236       396287.73     1574481.011      396292.071
     1574346.462      396311.602     1574233.615      396333.303
     1574040.473      396535.126
#Sta/Elev= 30
       0  765.34    39.2  757.02      49  755.22    58.9  754.01    68.7  753.48
    78.5  753.64   107.9   755.5   117.7  755.83   137.4  755.71   147.2  754.96
   196.2  748.99     206  748.25     236747.1664   264.7   746.6   274.4  746.84
   284.1  747.85   293.8  749.33   313.2  750.24   438.7  749.37   515.4  750.83
   563.6  752.75   659.9  753.36   669.5  753.71   679.2  754.42   717.7  758.65
   727.3  760.08     737  762.24   746.6  765.76   756.2  770.86   775.5  778.76
#Mann= 3 , 0 , 0
       0     .06       0     236    .045       0   284.1     .06       0
Bank Sta=236,284.1
XS Rating Curve= 0 ,0
Exp/Cntr=0.3,0.1

Type RM Length L Ch R = 1 ,47391.8 ,156.3,166.8,174.9
XS GIS Cut Line= 5
     1574728.407      396203.095      1574472.33      396211.775
     1574337.782      396231.307     1574224.934      396253.008
     1574031.792      396454.831
#Sta/Elev= 30
       0  759.24    47.4  752.73    56.9  751.72    66.4  751.03    75.9   750.8
    94.9  750.91   123.4  753.88   142.4  754.21   151.8  753.91   161.3  753.15
   189.8  749.68   208.8  748.13   227.8  747.35   256.2  747.42   265.9  747.21
   285.4  746.09     296747.0876   304.8  748.14   314.5   748.8   333.9  749.33
   382.5  749.84   449.6  750.05   507.1  751.26   545.6  751.74   622.7  754.61
   651.6  754.92   709.4  754.82   728.6  755.02   767.2  756.29   786.4  757.36
#Mann= 3 , 0 , 0
       0     .06       0   265.9    .045       0     296     .06       0
Bank Sta=265.9,296
XS Rating Curve= 0 ,0
Exp/Cntr=0.3,0.1

Type RM Length L Ch R = 1 ,47225   ,330.7,332.9,334.7
XS GIS Cut Line= 3
     1574745.768      396146.671     1574261.827      396031.654
     1574188.042      395944.848
#Sta/Elev= 30
       0  758.07    58.5  752.21      78   750.5    87.8  749.89    97.5  749.67
   107.3  749.84   136.6  751.65   146.3  752.07   165.8  752.32   185.3  751.71
   224.3  749.76   282.8  747.69   302.4  746.69     325745.1659   331.6  744.71
   341.4  744.42   351.1   744.4     374   744.4   419.4  744.47   448.6  745.16
   468.2  746.39   487.7  748.68   497.4  750.77   506.9  753.78   516.4   757.5
   525.9  760.93   544.9  766.88   573.4  776.64   592.4  782.54   611.4  787.92
#Mann= 3 , 0 , 0
       0     .06       0     325    .045       0     374     .06       0
#XS Ineff= 2 , 0
           161.2  753.52
Permanent Ineff=
       F       F
Bank Sta=325,374
XS Rating Curve= 0 ,0
Exp/Cntr=0.3,0.1

Type RM Length L Ch R = 1 ,46892.2 ,176.7,177,177.2
XS GIS Cut Line= 3
     1574821.723      395892.765     1574667.643      395894.935
     1574253.146      395749.536
#Sta/Elev= 30
       0  765.63     9.6  762.01    19.3  758.71    28.9  755.74    38.5  753.32
    48.2  751.76    57.8  750.96    86.7   749.9   105.9  748.37   115.6  747.94
   125.2  748.43   144.5   749.8   154.1  750.06   173.6  750.17   202.9  751.18
   222.4   751.1   232.2  750.34     242  748.61   251.7  746.44   261.5   744.8
   271.2  744.42     281   744.4   437.2  744.54     477   744.4   495.7   744.4
   505.5  744.67     511745.8149   515.3  746.71     525  750.35   593.4  778.21
#Mann= 3 , 0 , 0
       0     .06       0     477    .045       0     511     .07       0
#XS Ineff= 2 , 0
          212.58  751.38
Permanent Ineff=
       F       F
Bank Sta=477,511
XS Rating Curve= 0 ,0
Exp/Cntr=0.3,0.1

Type RM Length L Ch R = 1 ,46715.1 ,182.4,175.2,165.8
XS GIS Cut Line= 4
     1574815.212      395690.942     1574611.219      395690.942
     1574365.993      395601.966       1574307.4      395597.626
#Sta/Elev= 30
       0  757.83     9.7  755.31    19.4  754.25    38.9   752.6    58.3  751.14
      68  750.57    77.7   750.2    97.1  749.18   106.8  748.99   116.6  749.38
   145.7  751.27   155.4  751.72   165.1  751.83   174.8  751.76   184.6  751.39
   194.3  750.67   223.3  748.15     262  745.24   271.6  744.69   281.3  744.44
     291   744.4     404   744.4   433.4   744.4   435.9   744.4   445.5  744.79
   455.2  746.79   464.9  750.02   484.4  755.23   494.2  758.64   523.6  769.94
#Mann= 3 , 0 , 0
       0     .06       0     404    .045       0   433.4     .07       0
#XS Ineff= 2 , 0
          168.47  752.17
Permanent Ineff=
       F       F
Bank Sta=404,433.4
XS Rating Curve= 0 ,0
Exp/Cntr=0.3,0.1

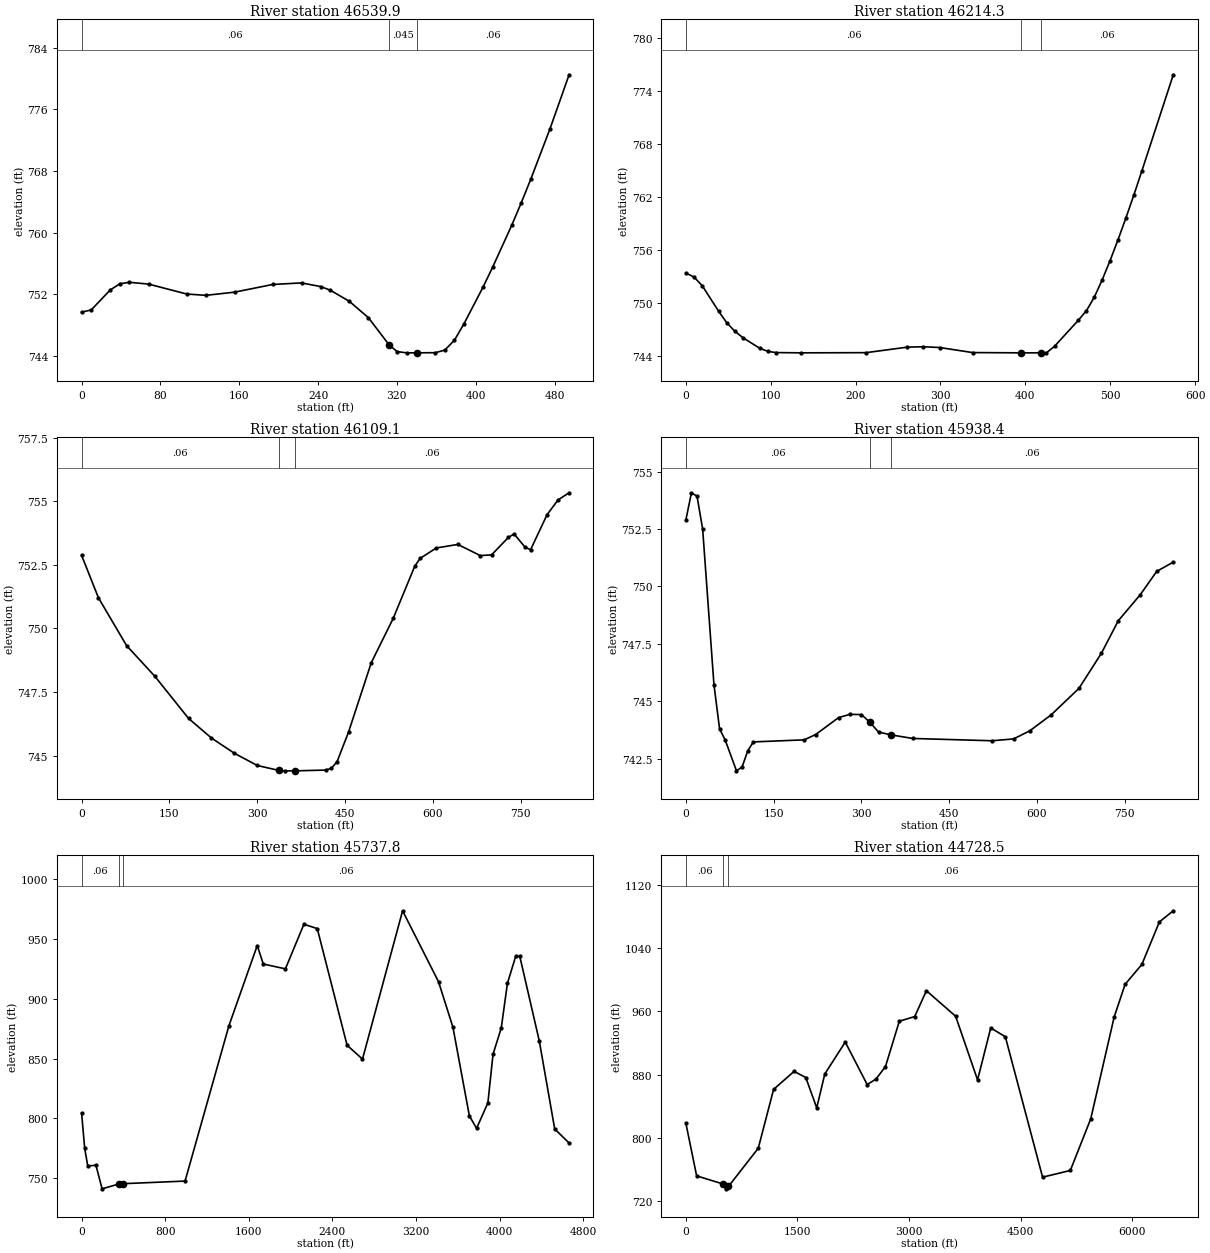
Type RM Length L Ch R = 1 ,46539.9 ,309.5,325.6,340.7
XS GIS Cut Line= 2
     1574771.809      395465.248     1574277.018      395460.907
#Sta/Elev= 30
       0  749.68     9.7  749.96    29.1  752.56    38.8  753.36    48.5  753.55
    67.9  753.32   106.7  752.03   126.1  751.86   155.2  752.27     194  753.27
   223.2  753.47   242.6     753   252.3  752.53   271.7  751.09   291.1  748.96
     312745.4565   320.2  744.56   329.9   744.4     340   744.4     359  744.42
   368.7  744.76   378.4  746.03   388.1  748.16   407.5  752.94   417.2  755.51
   436.6  760.95   446.3  763.88     456  766.95   475.4  773.46   494.8  780.47
#Mann= 3 , 0 , 0
       0     .06       0     312    .045       0     340     .06       0
Bank Sta=312,340
XS Rating Curve= 0 ,0
Exp/Cntr=0.3,0.1

Type RM Length L Ch R = 1 ,46214.3 ,103.8,105.3,105.3
XS GIS Cut Line= 3
     1574743.598      395402.314     1574392.035      395131.046
     1574261.827      395131.046
#Sta/Elev= 30
       0  753.43     9.6  752.98    19.3     752    38.6  749.12    48.3   747.8
    57.9  746.83    67.6  746.09    86.9  744.93    96.5  744.57   106.2  744.43
   135.2   744.4   212.4  744.42   260.6  745.04     280  745.09   299.2     745
   337.9  744.43     395   744.4     418   744.4   424.8   744.4   434.4  745.14
   462.6   748.1     472  749.17   481.3   750.7   490.6  752.67   499.9  754.84
   509.2  757.19   518.5  759.66   527.8  762.23   537.1  764.92   574.3  775.85
#Mann= 3 , 0 , 0
       0     .06       0     395    .045       0     418     .06       0
Bank Sta=395,418
XS Rating Curve= 0 ,0
Exp/Cntr=0.3,0.1

Type RM Length L Ch R = 1 ,46109.1 ,170.3,170.6,170.9
XS GIS Cut Line= 6
     1574767.469      395306.828      1574622.07       395196.15
     1574376.844      394987.817     1574279.188      394890.161
     1574237.955      394803.355     1574227.105      394710.039
#Sta/Elev= 30
       0  752.87    28.8   751.2    76.9  749.32     125  748.12   182.7  746.46
   221.8  745.69     261  745.09   300.1  744.61     337744.4161   346.7   744.4
     365   744.4   416.9  744.43   426.6   744.5   436.4  744.76   455.9  745.92
   494.8  748.65   532.2  750.39     569  752.44   578.2  752.75   605.8  753.16
   642.7   753.3   681.1  752.86   700.3  752.89   729.2  753.58   738.8  753.71
   757.6  753.19   766.9  753.09   795.1  754.47   813.9  755.05   832.7  755.33
#Mann= 3 , 0 , 0
       0     .06       0     337    .045       0     365     .06       0
Bank Sta=337,365
XS Rating Curve= 0 ,0
Exp/Cntr=0.3,0.1

Type RM Length L Ch R = 1 ,45938.4 ,196.2,200.6,203.5
XS GIS Cut Line= 6
     1574884.657       395191.81     1574739.257      395081.133
     1574494.032        394872.8     1574396.375      394775.144
     1574355.143      394688.338     1574344.292      394595.022
#Sta/Elev= 30
       0  752.88     9.6  754.08    19.2  753.93    28.8   752.5    48.1  745.72
    57.7   743.8    67.3  743.31    86.6  741.97    96.2  742.14   105.8  742.84
   115.4  743.23   202.3  743.32   221.8  743.55     261  744.29   280.5  744.43
   300.1  744.42   314.3744.0862   329.3  743.66     350743.5388   387.7  743.38
     523  743.28   559.8  743.36   587.4  743.71   624.2  744.41   671.5  745.56
   709.9  747.09   738.8  748.51   776.3  749.64   804.5  750.66   832.7  751.06
#Mann= 3 , 0 , 0
       0     .06       0   314.3    .045       0     350     .06       0
Bank Sta=314.3,350
XS Rating Curve= 0 ,0
Exp/Cntr=0.3,0.1

Type RM Length L Ch R = 1 ,45737.8 ,807,1009.3,1025.6
XS GIS Cut Line= 5
     1575021.375      395133.216     1574365.993       394404.05
     1573819.441       394387.05     1573510.951      394096.865
     1570795.952      394132.168
#Sta/Elev= 30
       0  804.35    29.4  774.79    58.8  760.03   137.3  760.54   196.1  740.82
     354  744.81     397 745.141   990.2  747.32    1410  877.43  1681.2  944.64
    1739  929.13  1950.8   925.1  2127.8  962.46  2255.7   958.8    2541   861.1
  2688.6   849.5  3072.3  973.74  3416.6  914.24  3554.3  876.15  3711.7  801.88
  3780.6  791.49  3888.8  812.86    3938  853.58  4016.7  875.49  4075.7  912.94
  4154.4  935.46  4193.8  935.68  4380.7  864.74  4528.2  791.01    4666   779.2
#Mann= 3 , 0 , 0
       0     .06       0     354    .045       0     397     .06       0
Bank Sta=354,397
XS Rating Curve= 0 ,0
Exp/Cntr=0.3,0.1

Type RM Length L Ch R = 1 ,44728.5 ,313,116.8,123.2
XS GIS Cut Line= 5
     1575364.691      394873.668     1575354.275      394660.126
     1575392.881      393989.347     1572936.871      391623.117
     1570726.508      392083.556
#Sta/Elev= 30
       0  818.88   145.8  751.81   505.9  741.39   535.1   735.4   574.1   738.5
   974.1  786.74  1180.5  861.25  1455.7  884.02    1613  876.23  1760.4  837.87
  1868.5  880.68  2143.7  921.08  2438.6  867.34  2556.5  874.24  2684.3  890.09
    2871  947.53  3077.4  953.33  3234.7  986.09  3627.8  953.75  3922.6  873.23
  4099.6  938.99  4296.1  927.83  4796.8  750.15  5169.8  758.63  5444.6  824.09
  5758.8  952.67    5906  994.09  6131.8  1019.4  6367.4 1073.17  6553.9 1087.21
#Mann= 3 , 0 , 0
       0     .06       0   505.9    .045       0   574.1     .06       0
Bank Sta=505.9,574.1
XS Rating Curve= 0 ,0
Exp/Cntr=0.3,0.1

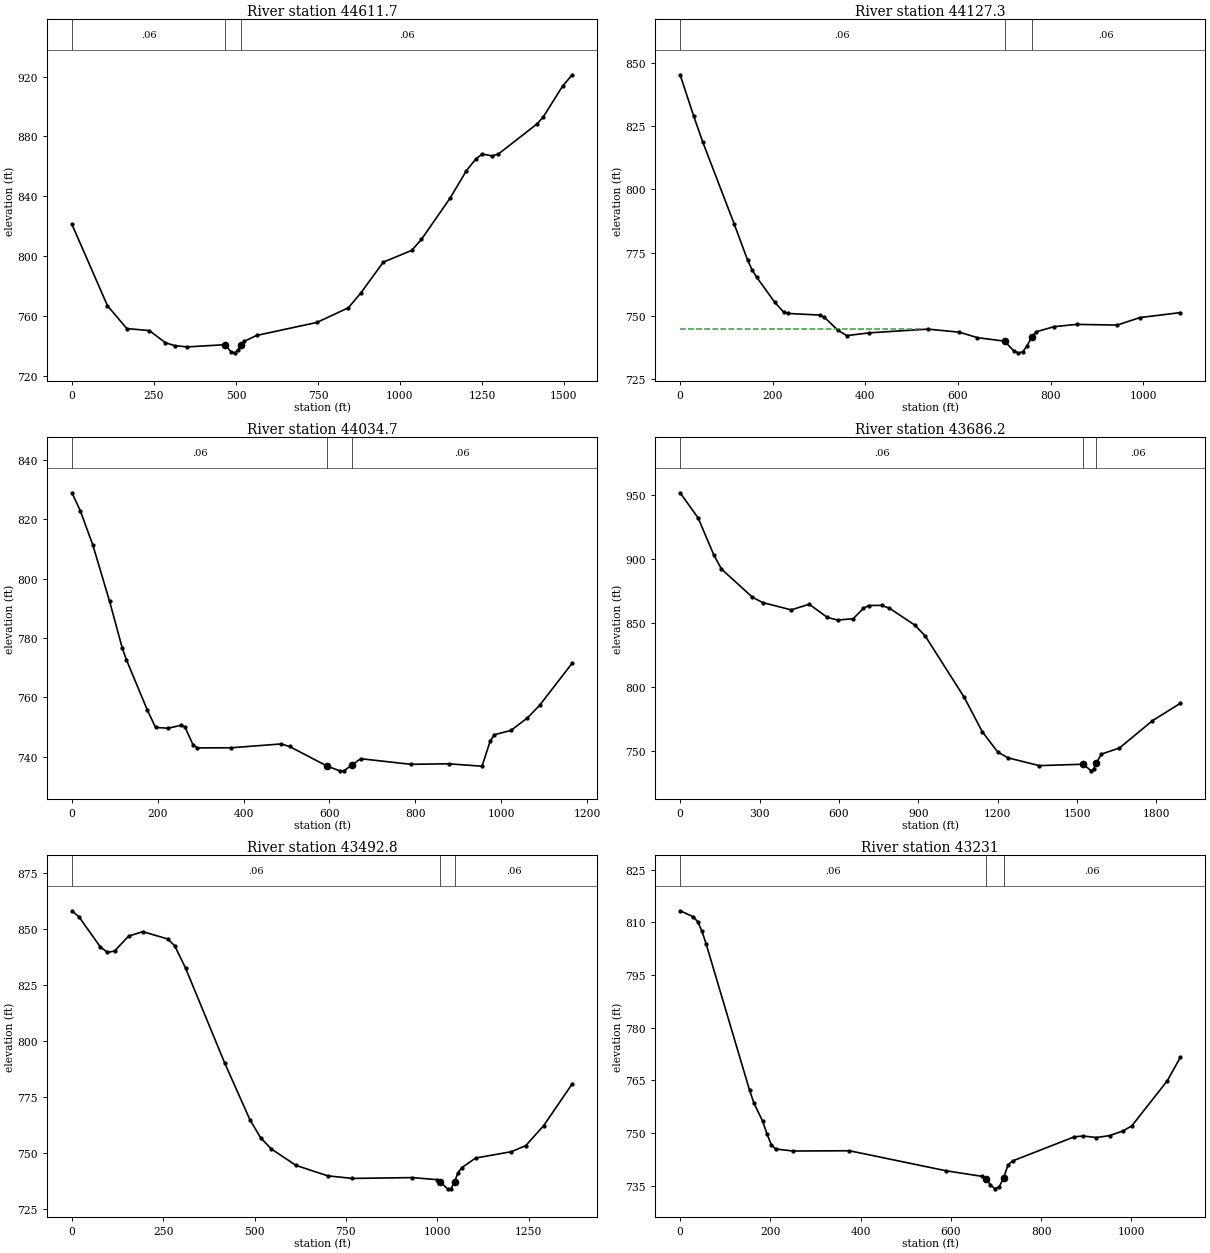
Type RM Length L Ch R = 1 ,44611.7 ,463.7,484.4,502.3
XS GIS Cut Line= 5
     1575395.941      394873.668     1575414.171      394579.397
     1575502.712      394316.376     1575592.022       393861.38
     1575290.015      393476.384
#Sta/Elev= 30
       0  821.26   108.1  767.09   167.1  751.78   235.9  750.44     285  742.34
     314  740.34   352.2  739.56   467.1  741.04   486.2  735.94   495.8  735.59
   505.4  737.33   514.9  740.92   524.5  743.19   562.8   747.2   746.2  755.84
   842.8  765.66   881.5  775.76   949.1   796.1    1036  803.98  1065.4  811.26
  1153.5  839.04  1202.4  857.08  1231.8  865.12  1251.3  868.27  1280.7  867.05
  1300.3  868.31  1417.7  888.31  1437.3  893.14    1496  913.63  1525.4  921.17
#Mann= 3 , 0 , 0
       0     .06       0   467.1    .045       0   514.9     .06       0
Bank Sta=467.1,514.9
XS Rating Curve= 0 ,0
Exp/Cntr=0.3,0.1

Type RM Length L Ch R = 1 ,44127.3 ,91.5,92.6,390.9
XS GIS Cut Line= 3
     1575408.962      394915.334     1575461.795      394559.412
     1576125.108      394277.314
#Sta/Elev= 30
       0  845.34    29.2  829.02    48.6  818.87   116.7  786.37   145.9  771.97
   155.6  768.15   165.3  765.31   204.2   755.4   223.7  751.47   233.4  750.95
   301.5  750.32   311.2  749.49   340.4  744.38   359.8  742.19   408.5  743.28
   535.2  744.76   603.3  743.54   642.3  741.37   700.7  740.01   720.2  736.25
     730  735.38   739.7   735.7   749.4  738.16   759.2  741.56   768.9  743.69
   807.9  745.74   856.6  746.63   944.3  746.36     993  749.32  1080.6  751.29
#Mann= 3 , 0 , 0
       0     .06       0   700.7    .045       0   759.2     .06       0
#XS Ineff= 2 , 0
          522.94  744.64
Permanent Ineff=
       F       F
Bank Sta=700.7,759.2
XS Rating Curve= 0 ,0
Exp/Cntr=0.3,0.1

Type RM Length L Ch R = 1 ,44034.7 ,385.6,348.5,14
XS GIS Cut Line= 5
     1575476.671      394886.689     1575512.422      394635.942
     1576158.881      394361.714     1576127.156      394270.989
     1576116.836       394157.24
#Sta/Elev= 30
       0  828.93    19.5  822.81    48.7  811.26    87.7  792.31   116.9  776.73
   126.6  772.74   175.4  755.75   194.8  749.86   224.1  749.59   253.3  750.55
     263  750.08   282.5  743.87   292.3  742.96   370.3     743   487.4  744.29
   506.9  743.44   594.6  736.82   623.9  735.23   633.6  735.24   653.2  737.27
   672.7  739.32   789.7  737.43   877.5   737.6   955.5  736.79   974.7   745.3
   984.3   747.4  1022.8  748.84  1061.1  753.03  1089.7   757.3  1165.8  771.54
#Mann= 3 , 0 , 0
       0     .06       0   594.6    .045       0   653.2     .06       0
Bank Sta=594.6,653.2
XS Rating Curve= 0 ,0
Exp/Cntr=0.3,0.1

Type RM Length L Ch R = 1 ,43686.2 ,186.6,193.4,199.8
XS GIS Cut Line= 5
     1575691.742      395729.513     1576113.653      394849.543
     1576294.379      394657.522     1576143.337      394285.126
     1576112.087       394037.73
#Sta/Elev= 30
       0  952.02    68.3   932.2   126.9  903.51   156.1  892.31   273.2  870.25
   312.3  866.05   419.6  860.34   487.9  864.75   556.3  854.44   595.3  852.39
   653.8  853.38   692.9  861.56   712.4  863.74   761.2  863.88   790.5  861.69
   888.1  848.27   927.1  839.65  1073.6   791.9  1141.9  764.96  1200.5     749
  1239.6  744.47  1357.2  738.39  1523.8  739.49  1553.2  734.31    1563  735.76
  1572.8  740.38  1592.4  747.45  1660.6  752.22  1785.3  773.58  1890.8  787.21
#Mann= 3 , 0 , 0
       0     .06       0  1523.8    .045       0  1572.8     .06       0
Bank Sta=1523.8,1572.8
XS Rating Curve= 0 ,0
Exp/Cntr=0.3,0.1

Type RM Length L Ch R = 1 ,43492.8 ,264.9,261.8,259
XS GIS Cut Line= 6
     1576020.421      395248.787     1576126.324      395009.203
     1576339.865      394807.815     1576385.293      394560.925
     1576357.082       394253.85     1576300.658       394005.37
#Sta/Elev= 30
       0   858.1    19.4  855.35    77.6  841.99      97  839.56   116.4  840.14
   155.2  846.83     194  848.78     262  845.55   281.5  842.43   310.9  832.57
   418.5   790.1     487  765.03   516.3  756.99   545.7  751.95   613.4  744.62
   700.3  739.96   767.9  738.81   931.8  739.18   999.2  738.27  1008.9  737.22
  1028.2  734.17  1037.8  734.24  1047.4  737.38    1057  741.33  1066.7  743.53
  1105.2  747.89  1203.1  750.73  1242.3  753.41  1291.3   762.3  1369.7  780.98
#Mann= 3 , 0 , 0
       0     .06       0  1008.9    .045       0  1047.4     .06       0
Bank Sta=1008.9,1047.4
XS Rating Curve= 0 ,0
Exp/Cntr=0.3,0.1

Type RM Length L Ch R = 1 ,43231   ,575.5,572,567
XS GIS Cut Line= 4
     1576945.189      394934.189     1576697.793      394652.071
     1576598.607      394213.779     1576445.829      393974.196
#Sta/Elev= 30
       0  813.29    28.9  811.61    38.5  810.23    48.1  807.57    57.7  803.82
   153.9  762.22   163.6  758.56   182.8  753.42   192.4  749.81     202  746.71
   211.7   745.5   250.2  744.92   375.2     745   590.2  739.28   668.3  737.73
   678.1  737.07   687.8  735.32   697.6  734.16   707.4   734.8   717.1  737.34
   726.9  741.03   736.7  742.09   873.6  748.96   893.2   749.2   922.6  748.76
     952  749.31   981.4  750.64    1001  752.06  1079.4  764.85  1108.8  771.61
#Mann= 3 , 0 , 0
       0     .06       0   678.1    .045       0   717.1     .06       0
Bank Sta=678.1,717.1
XS Rating Curve= 0 ,0
Exp/Cntr=0.3,0.1

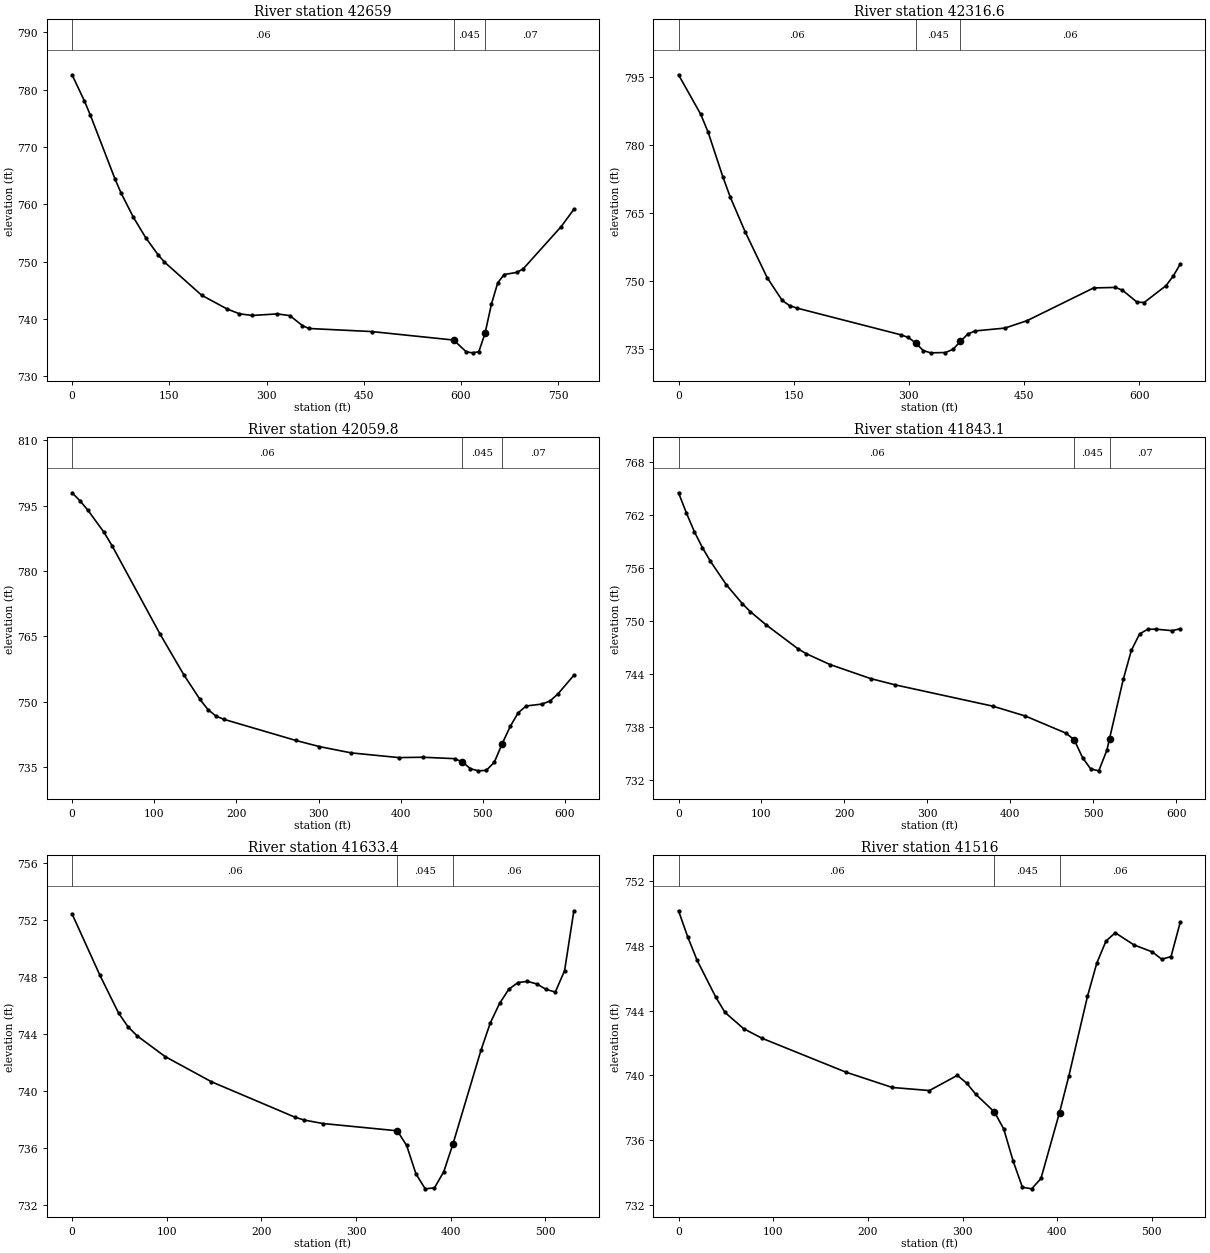
Type RM Length L Ch R = 1 ,42659   ,340.9,342.3,341.7
XS GIS Cut Line= 4
     1577200.629       394600.23     1577075.629      394498.668
     1576893.337      394048.147       1576869.9      393923.147
#Sta/Elev= 30
       0  782.61      19  778.05    28.4  775.52    66.3  764.42    75.8  761.94
    94.7  757.74   113.7  754.18   132.6  751.23   142.1  749.99   199.9  744.16
   238.8  741.78   258.3  740.92   277.7  740.63   316.6   740.9     336   740.6
   355.5  738.86   365.2  738.36   462.4  737.82   588.7  736.34   608.2  734.28
   617.9  734.11   627.6  734.31   637.3  737.58   647.1  742.64   656.8  746.33
   666.6  747.77   686.2  748.14     696  748.75   754.7  756.14   774.2  759.15
#Mann= 3 , 0 , 0
       0     .06       0   588.7    .045       0   637.3     .07       0
Bank Sta=588.7,637.3
XS Rating Curve= 0 ,0
Exp/Cntr=0.3,0.1

Type RM Length L Ch R = 1 ,42316.6 ,256.9,256.8,255.9
XS GIS Cut Line= 4
     1577341.254      394415.334     1577247.504      394347.626
       1577119.9      393962.209     1577078.233      393837.209
#Sta/Elev= 30
       0  795.53    28.9   786.8    38.6  782.82    57.8  772.94    67.5  768.45
    86.7  760.86   115.6  750.65     135  745.68   144.6  744.53   154.3  743.98
   289.6  738.08   299.3   737.5     309  736.25   318.6  734.61   328.3   734.1
   347.6  734.17   357.3  734.86     367  736.61   376.6  738.25   386.3  738.94
     425  739.57     454  741.22   540.5  748.44   568.7  748.55   578.1  747.94
   596.9  745.31   606.3  745.22   634.6  748.92     644  751.02   653.4  753.73
#Mann= 3 , 0 , 0
       0     .06       0     309    .045       0     367     .06       0
Bank Sta=309,367
XS Rating Curve= 0 ,0
Exp/Cntr=0.3,0.1

Type RM Length L Ch R = 1 ,42059.8 ,216.9,216.7,216.5
XS GIS Cut Line= 3
     1577403.754      394402.314     1577403.754      394217.418
     1577260.525      393816.376
#Sta/Elev= 30
       0  797.94     9.7  796.09    19.5  793.88    38.9  788.86    48.7  785.78
     107  765.53   136.2   756.1   155.7   750.5   165.4  748.16   175.2  746.67
   184.9  745.92     272   741.1     301  739.67   339.8  738.22   397.8  737.14
   426.9  737.22   465.6   736.9   475.2  736.14   484.9  734.59   494.6   734.1
   504.3  734.22     514  736.08   523.6  740.35   533.3  744.28     543  747.42
   552.7  748.99     572  749.43   581.7  750.12   591.4  751.76   610.8  756.04
#Mann= 3 , 0 , 0
       0     .06       0   475.2    .045       0   523.6     .07       0
Bank Sta=475.2,523.6
XS Rating Curve= 0 ,0
Exp/Cntr=0.3,0.1

Type RM Length L Ch R = 1 ,41843.1 ,213.1,209.7,206.1
XS GIS Cut Line= 3
     1577690.212      394305.959     1577604.275      394134.084
      1577463.65      393746.064
#Sta/Elev= 30
       0  764.53     9.6  762.21    19.2   760.1    28.8  758.31    38.4  756.77
    57.6  754.11    76.9  751.96    86.5  751.06   105.7  749.55   144.1  746.84
   153.7   746.3   182.6  745.06   231.5  743.47     261  742.76   378.9  740.34
   418.2  739.22   467.3  737.27   477.1  736.51     487  734.51   496.8  733.23
   506.6  733.01   516.4  735.36  519.57  736.66   536.1  743.38   545.9  746.67
   555.8  748.53   565.6  749.06   575.4  749.07     595   748.9   604.9  749.12
#Mann= 3 , 0 , 0
       0     .06       0   477.1    .045       0  519.57     .07       0
Bank Sta=477.1,519.57
XS Rating Curve= 0 ,0
Exp/Cntr=0.3,0.1

Type RM Length L Ch R = 1 ,41633.4 ,117.1,117.5,117.9
XS GIS Cut Line= 2
     1577875.108      394121.064     1577627.712      393652.314
#Sta/Elev= 28
       0  752.41    29.4  748.11    49.1  745.46    58.9  744.51    68.7  743.86
    98.2  742.41   147.2  740.64   235.6  738.15   245.4  737.95     265  737.71
   343.5   737.2   353.4  736.17   363.2  734.18     373  733.13   382.8   733.2
   392.6  734.33   402.4   736.3   431.9  742.85   441.7  744.76   451.5  746.13
   461.3  747.13   471.1   747.6     481  747.68   490.8   747.5   500.6  747.12
   510.4  746.93   520.2  748.43     530  752.63
#Mann= 3 , 0 , 0
       0     .06       0   343.5    .045       0   402.4     .06       0
Bank Sta=343.5,402.4
XS Rating Curve= 0 ,0
Exp/Cntr=0.3,0.1

Type RM Length L Ch R = 1 ,41516   ,106.6,105.4,104.3
XS GIS Cut Line= 2
     1577971.462      394058.564     1577724.066      393589.814
#Sta/Elev= 30
       0  750.18     9.8  748.55    19.6  747.12    39.3  744.84    49.1  743.89
    68.7  742.89    88.3  742.29   176.7   740.2   225.8  739.25     265  739.06
   294.5     740   304.3  739.52   314.1  738.82   333.7  737.73   343.5  736.68
   353.4   734.7   363.2  733.08     373  732.98   382.8  733.62   402.4   737.7
   412.2  739.95   431.9  744.88   441.7  746.93   451.5  748.31   461.3  748.82
     481  748.07   500.6  747.63   510.4  747.18   520.2  747.35     530  749.49
#Mann= 3 , 0 , 0
       0     .06       0   333.7    .045       0   402.4     .06       0
Bank Sta=333.7,402.4
XS Rating Curve= 0 ,0
Exp/Cntr=0.3,0.1

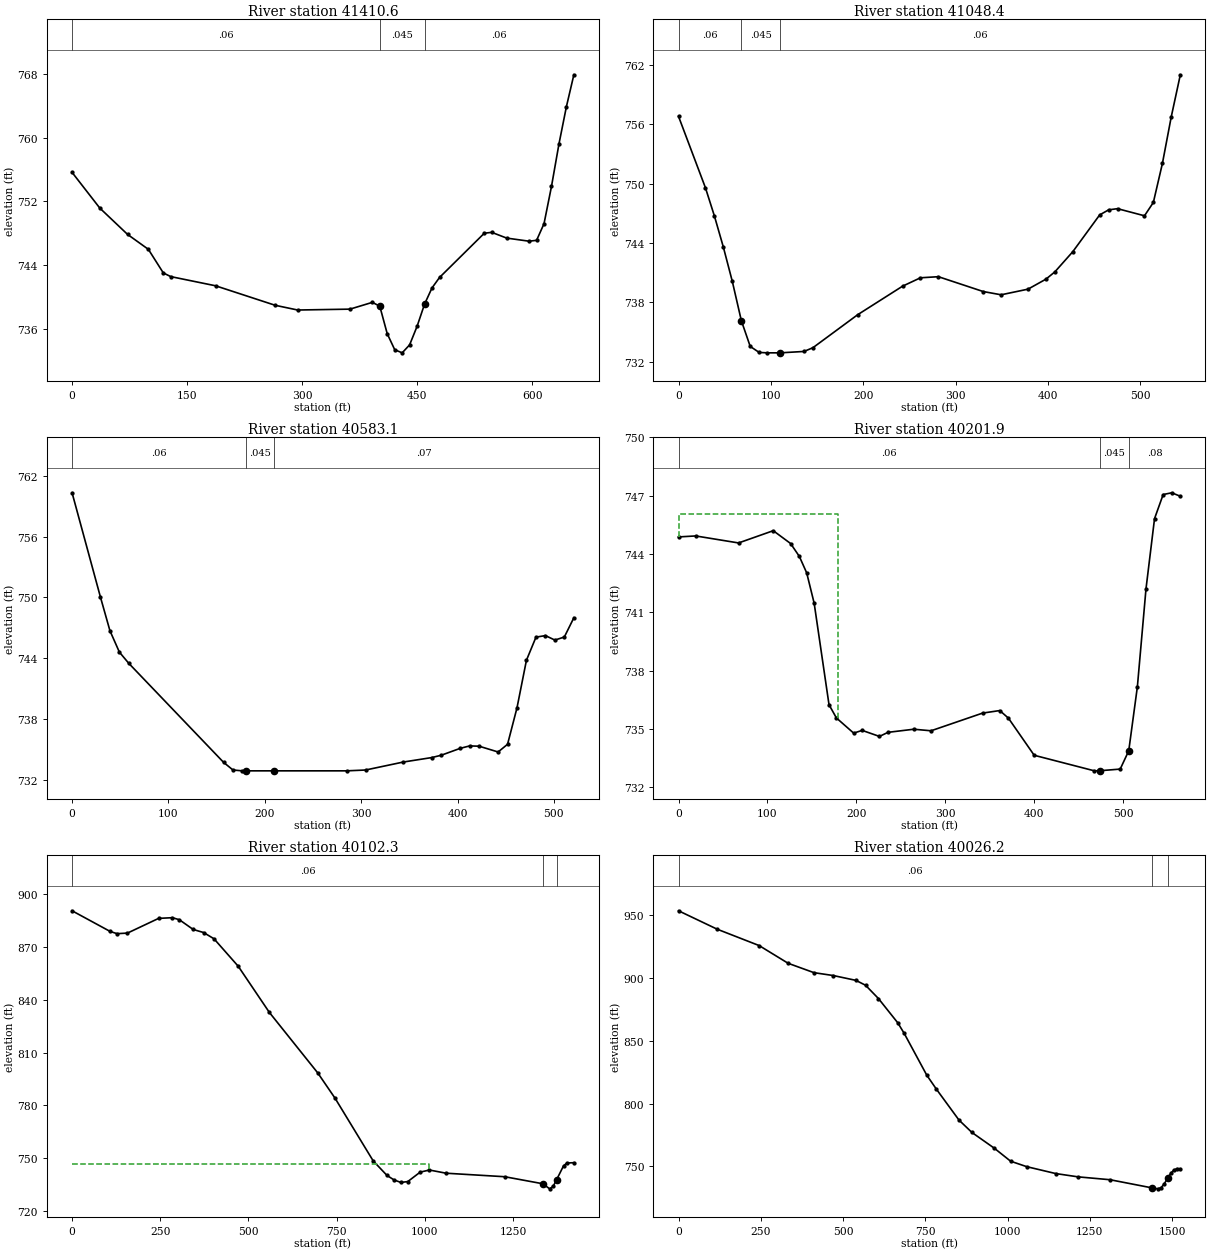
Type RM Length L Ch R = 1 ,41410.6 ,372.3,362.2,351.2
XS GIS Cut Line= 4
     1578062.608      394071.584     1578052.191      393972.626
     1577846.462      393608.043     1577747.504      393514.293
#Sta/Elev= 30
       0  755.63    36.2  751.15    72.4  747.85    99.5  745.98     119  743.02
   128.7  742.56   187.1  741.41     265  738.96   294.2  738.37   362.4  738.48
   391.6  739.33   401.3  738.85     411   735.4   420.8  733.39   430.5     733
   440.2     734     450  736.34   459.7  739.11   469.4  741.14   479.2  742.45
   537.6     748   547.3  748.11   566.8  747.39     596     747   605.8  747.11
   615.5   749.2   625.2  753.86     635  759.21   644.7  763.88   654.4  767.87
#Mann= 3 , 0 , 0
       0     .06       0   401.3    .045       0   459.7     .06       0
Bank Sta=401.3,459.7
XS Rating Curve= 0 ,0
Exp/Cntr=0.3,0.1

Type RM Length L Ch R = 1 ,41048.4 ,466.1,465.3,464.1
XS GIS Cut Line= 2
     1578281.358      393738.251     1577828.233      393438.772
#Sta/Elev= 30
       0  756.81    29.1   749.6    38.8  746.75    48.5   743.6    58.2  740.13
      68736.1529    77.6  733.55    87.3  732.94    96.3   732.9     110   732.9
   135.8  733.04   145.5  733.42     194  736.76   242.5  739.64   261.9  740.49
   281.3   740.6   329.8   739.1   349.2  738.77   378.3  739.34   397.7  740.35
   407.4  741.09   426.8  743.13   455.9  746.85   465.6  747.36   475.2  747.48
   504.4  746.76     514  748.11   523.8  752.05   533.4  756.78   543.2  761.02
#Mann= 3 , 0 , 0
       0     .06       0      68    .045       0     110     .06       0
Bank Sta=68,110
XS Rating Curve= 0 ,0
Exp/Cntr=0.3,0.1

Type RM Length L Ch R = 1 ,40583.1 ,385.4,381.2,376.1
XS GIS Cut Line= 2
     1578505.316      393342.418     1578057.508      393076.793
#Sta/Elev= 27
       0  760.33    29.5  750.02    39.3  746.72    49.1  744.61    58.9   743.5
   157.2  733.74     167  732.98   176.8   732.9   180.8   732.9     210   732.9
   284.9   732.9   304.5  732.98   343.8  733.77   373.3  734.21   383.1  734.44
   402.8  735.12   412.6  735.36   422.4  735.33   442.1  734.76   451.9  735.52
   461.7  739.12   471.5  743.81   481.4  746.09   491.2  746.24     501   745.8
   510.8   746.1   520.7     748
#Mann= 3 , 0 , 0
       0     .06       0   180.8    .045       0     210     .07       0
Bank Sta=180.8,210
XS Rating Curve= 0 ,0
Exp/Cntr=0.3,0.1

Type RM Length L Ch R = 1 ,40201.9 ,97.7,99.6,101.4
XS GIS Cut Line= 5
     1578496.202      393247.366     1578524.848      393175.751
     1578522.243      393117.157     1578519.639      393075.491
     1578155.056      392946.584
#Sta/Elev= 30
       0  744.87    19.3  744.92    67.5  744.56   106.5  745.19     126  744.53
   135.8  743.87   144.1  743.02   152.5  741.46   169.2  736.24   177.5  735.56
   196.9  734.78   206.5  734.92   225.9  734.61   235.5  734.82   264.5  734.98
   283.9   734.9   341.9  735.81   361.2  735.94   370.9  735.55   399.9  733.64
   467.6  732.84     474732.8467   496.6  732.93   506.2  733.87   515.9  737.16
   525.6   742.2   535.2  745.81   544.9  747.05   554.6  747.14   564.2  746.96
#Mann= 3 , 0 , 0
       0     .06       0     474    .045       0   506.2     .08       0
#XS Ineff= 2 , 0
          179.75  746.05
Permanent Ineff=
       F       F
Bank Sta=474,506.2
XS Rating Curve= 0 ,0
Exp/Cntr=0.3,0.1

Type RM Length L Ch R = 1 ,40102.3 ,75.7,76.1,76.4
XS GIS Cut Line= 4
     1578779.211      394023.292     1578574.376      393093.646
     1578561.618      393015.633     1578204.319       392854.74
#Sta/Elev= 30
       0  890.54     108   878.8   127.6  877.54     157  877.86   245.4  886.22
   284.6  886.62   304.2  885.45   343.5  879.92   372.9  878.18   402.4  874.64
   471.1  859.04   559.4  832.81   696.8  798.39   745.8  784.03   853.8  748.47
   893.1  740.18   912.7  737.68   932.3  736.22   951.9  736.72   987.1  742.09
  1013.4  743.28  1060.4  741.47  1226.9  739.47  1334.7  735.48  1354.3  732.59
  1364.1     734  1373.9   737.8  1393.5  745.64  1403.2  747.26  1422.8  747.44
#Mann= 3 , 0 , 0
       0     .06       0  1334.7    .045       0  1373.9     .08       0
#XS Ineff= 2 , 0
          1013.1  746.71
Permanent Ineff=
       F       F
Bank Sta=1334.7,1373.9
XS Rating Curve= 0 ,0
Exp/Cntr=0.3,0.1

Type RM Length L Ch R = 1 ,40026.2 ,164.8,165.6,166.5
XS GIS Cut Line= 3
     1579736.881      392951.735     1578580.512      392946.584
      1578246.31      392790.334
#Sta/Elev= 30
       0  953.42   117.6  938.75     245  925.74   333.2  911.63   411.6  904.18
   470.4  901.89     539  898.06   568.4  894.18   607.6   883.6   666.4  864.27
     686  855.84   754.6  822.59     784   811.4   852.6  786.85   891.8  777.03
   960.4  764.38  1009.4  754.15  1058.4   749.8  1146.6  744.32  1214.6  741.69
  1311.7  739.41  1437.8732.9957  1457.3  732.16    1467  733.12  1476.8  736.28
  1487.8741.1346  1496.2  744.46  1505.9  747.16  1515.6  748.21  1525.3   748.1
#Mann= 3 , 0 , 0
       0     .06       0  1437.8    .045       0  1487.8      .1       0
Bank Sta=1437.8,1487.8
XS Rating Curve= 0 ,0
Exp/Cntr=0.3,0.1