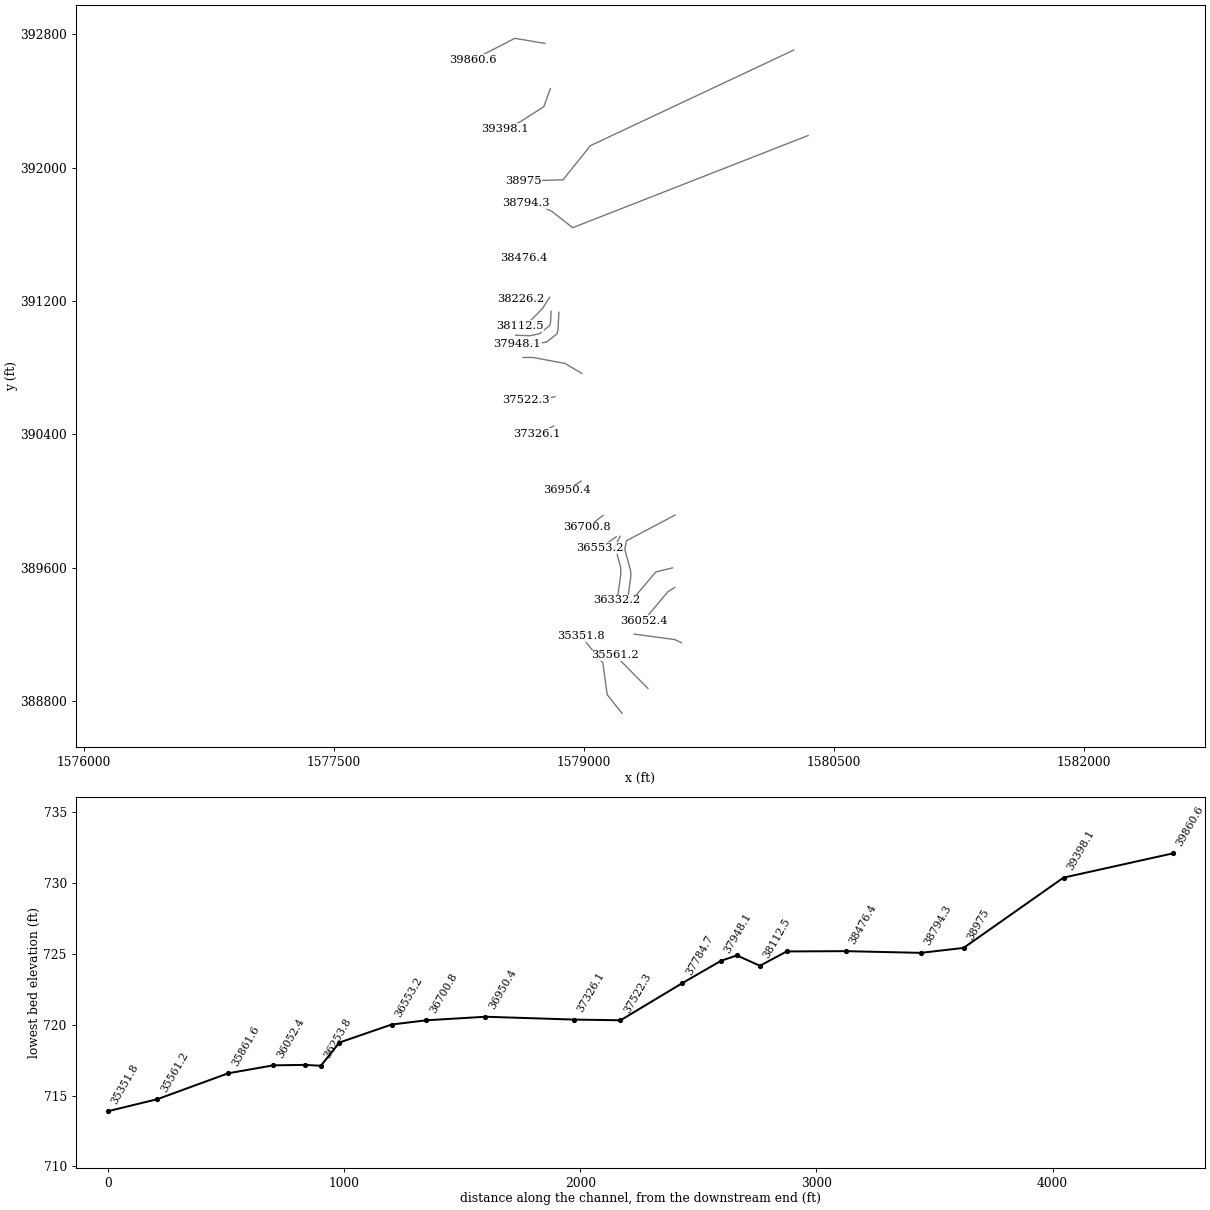
HEC-RAS study PTPLSCRK.prj: PTPLSCRK

--- PTPLSCRK.g01 (geometry) --- (continued)

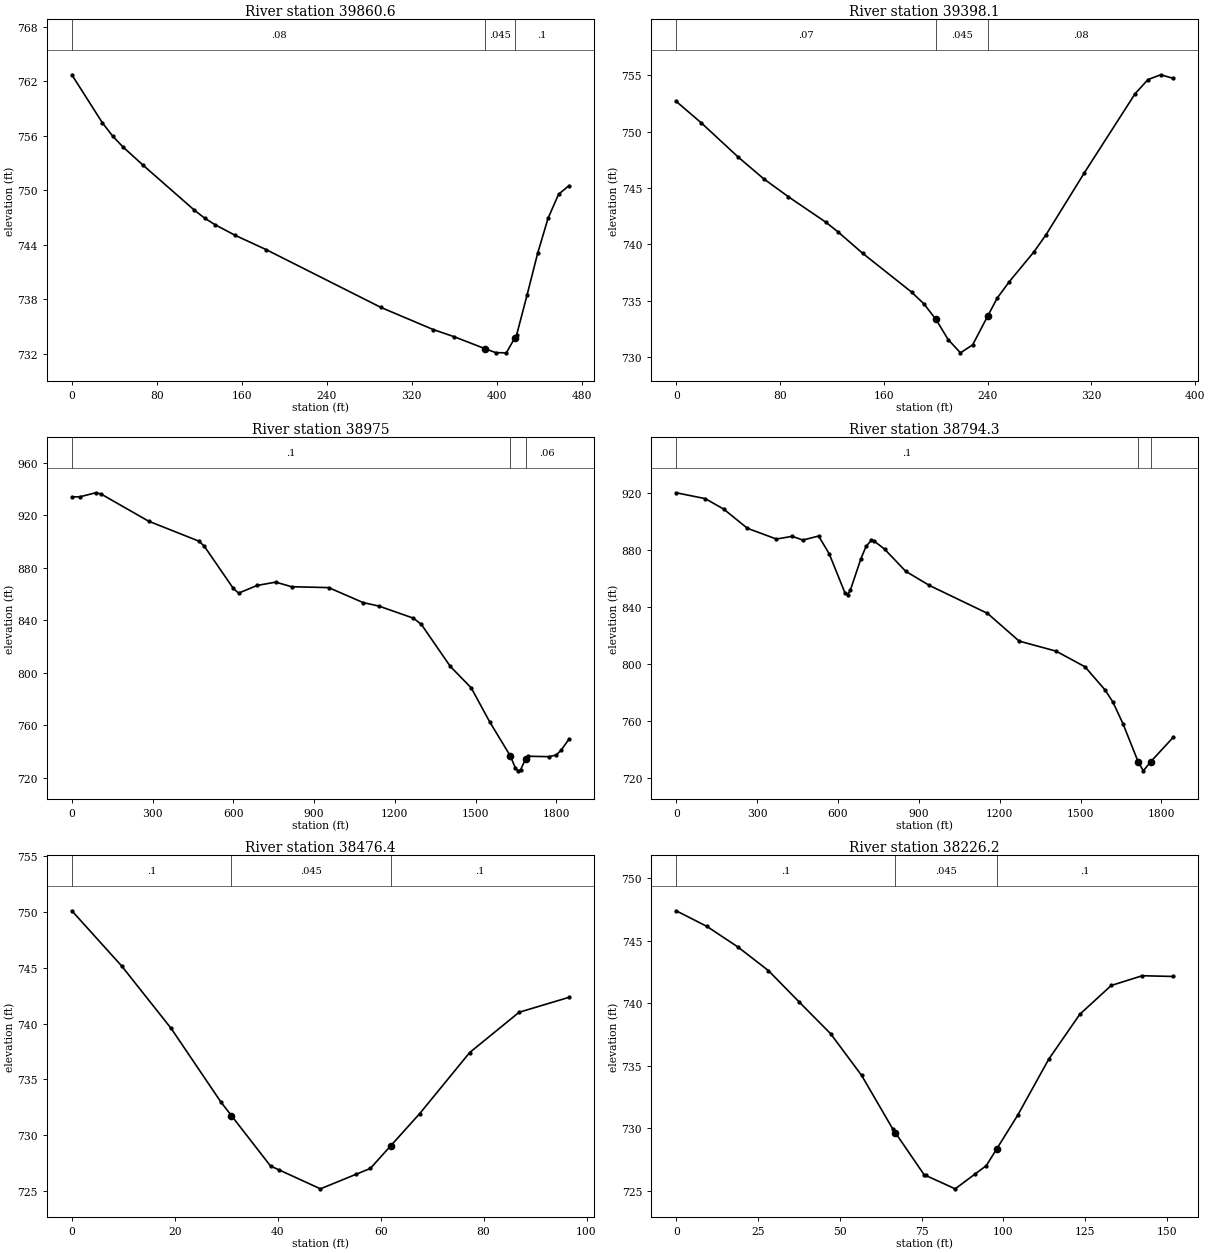
Type RM Length L Ch R = 1 ,39860.6 ,460.4,462.5,464.6
XS GIS Cut Line= 3
     1578764.973      392744.762     1578584.852      392775.144
     1578330.946      392644.935
#Sta/Elev= 23
       0  762.74    28.8  757.44    38.5  755.97    48.1  754.79    67.3  752.75
   115.4  747.81     125  746.94   134.6  746.23   153.8  745.04   182.7  743.48
   290.9   737.1   340.1  734.66   359.8  733.87     389732.5438   399.1  732.11
     409  732.09     417733.7387   418.8  734.11   428.6   738.5   438.5  743.07
   448.3  746.93   458.2  749.57     468  750.52
#Mann= 3 , 0 , 0
       0     .08       0     389    .045       0     417      .1       0
Bank Sta=389,417
XS Rating Curve= 0 ,0
Exp/Cntr=0.3,0.1

Type RM Length L Ch R = 1 ,39398.1 ,435.2,423.1,411
XS GIS Cut Line= 4
     1578797.526      392473.494     1578758.463      392364.987
     1578615.234      392273.841     1578526.258      392232.609
#Sta/Elev= 24
       0  752.68    19.2  750.79      48  747.72    67.3  745.83    86.5  744.22
   115.3  741.97   124.8   741.1   143.6  739.22   181.4  735.77   190.8  734.74
   200.2  733.35   209.6  731.56   219.1  730.38   228.5  731.09     240733.6176
   247.4  735.23   256.8   736.7   275.7  739.33   285.1  740.86   314.5  746.33
   353.7  753.36   363.6  754.61   373.4  755.04   383.2  754.72
#Mann= 3 , 0 , 0
       0     .07       0   200.2    .045       0     240     .08       0
Bank Sta=200.2,240
XS Rating Curve= 0 ,0
Exp/Cntr=0.3,0.1

Type RM Length L Ch R = 1 ,38975   ,190.9,180.7,169.7
XS GIS Cut Line= 4
     1580257.714      392704.339     1579038.096      392131.422
      1578873.48      391926.619     1578636.935      391920.109
#Sta/Elev= 30
       0     934    29.5  934.04    88.5  937.12   108.2  936.22   285.2  915.49
   472.1  900.29   491.8  896.51     600  864.26   619.6  860.72   688.5  866.58
   757.3  869.08   816.4   865.6   954.1  864.92  1081.9  853.54  1140.9  850.84
  1268.8  841.66  1298.3  836.94  1405.9  804.94  1483.7  788.59  1551.8  762.86
  1629.2  736.65  1648.1  727.34  1657.6  725.42    1667  726.18    1686  734.66
  1695.4  736.52  1771.2  736.21  1799.6  737.47  1818.5  741.38  1846.9  749.59
#Mann= 3 , 0 , 0
       0      .1       0  1629.2    .045       0    1686     .06       0
Bank Sta=1629.2,1686
XS Rating Curve= 0 ,0
Exp/Cntr=0.3,0.1

Type RM Length L Ch R = 1 ,38794.3 ,307.8,317.8,328.2
XS GIS Cut Line= 5
      1580344.52      392192.186     1578931.915      391639.607
     1578806.206      391737.817     1578695.529        391789.9
     1578649.956       391787.73
#Sta/Elev= 30
       0  920.31   107.6  916.22   176.2  908.86   264.2  895.37   371.9  887.81
   430.6  889.75   469.7  887.11   528.4  889.93   567.6  877.48   626.3  849.89
   636.1  848.87   645.9  851.81     685  873.89   704.6   882.8   724.2   886.9
     734  886.45   773.1  880.72   851.4  865.19   939.5  855.22  1154.8  835.64
  1272.2  816.17  1409.2  809.12  1516.8  798.09  1591.9  781.63  1620.1  773.34
  1657.6  758.06    1714  731.28  1732.8  725.07    1761  731.62  1844.3  748.71
#Mann= 3 , 0 , 0
       0      .1       0    1714    .045       0    1761      .1       0
Bank Sta=1714,1761
XS Rating Curve= 0 ,0
Exp/Cntr=0.3,0.1

Type RM Length L Ch R = 1 ,38476.4 ,251,250.2,249.5
XS GIS Cut Line= 2
     1578733.959      391459.316     1578637.387      391458.231
#Sta/Elev= 15
       0  750.12     9.7  745.16    19.3  739.57      29  732.95      31731.7604
    38.6  727.24    40.3  726.88    48.3  725.19    55.3  726.51      58  727.02
      62  729.07    67.6  731.94    77.3  737.41    86.9  741.02    96.6  742.36
#Mann= 3 , 0 , 0
       0      .1       0      31    .045       0      62      .1       0
Bank Sta=31,62
XS Rating Curve= 0 ,0
Exp/Cntr=0.3,0.1

Type RM Length L Ch R = 1 ,38226.2 ,92.6,113.7,132.1
XS GIS Cut Line= 3
     1578752.405      391239.047     1578731.788       391207.58
     1578617.406      391210.108
#Sta/Elev= 21
       0  747.39     9.4  746.14    18.8  744.51    28.2  742.61    37.6   740.1
    47.2  737.57    56.7  734.23    66.2  729.96      67 729.655    75.8   726.3
    76.3  726.24    85.3  725.17    91.3  726.34    94.8  727.02      98728.3633
   104.4  731.05   113.9  735.53   123.4  739.12     133  741.42   142.5   742.2
     152  742.14
#Mann= 3 , 0 , 0
       0      .1       0      67    .045       0      98      .1       0
Bank Sta=67,98
XS Rating Curve= 0 ,0
Exp/Cntr=0.3,0.1

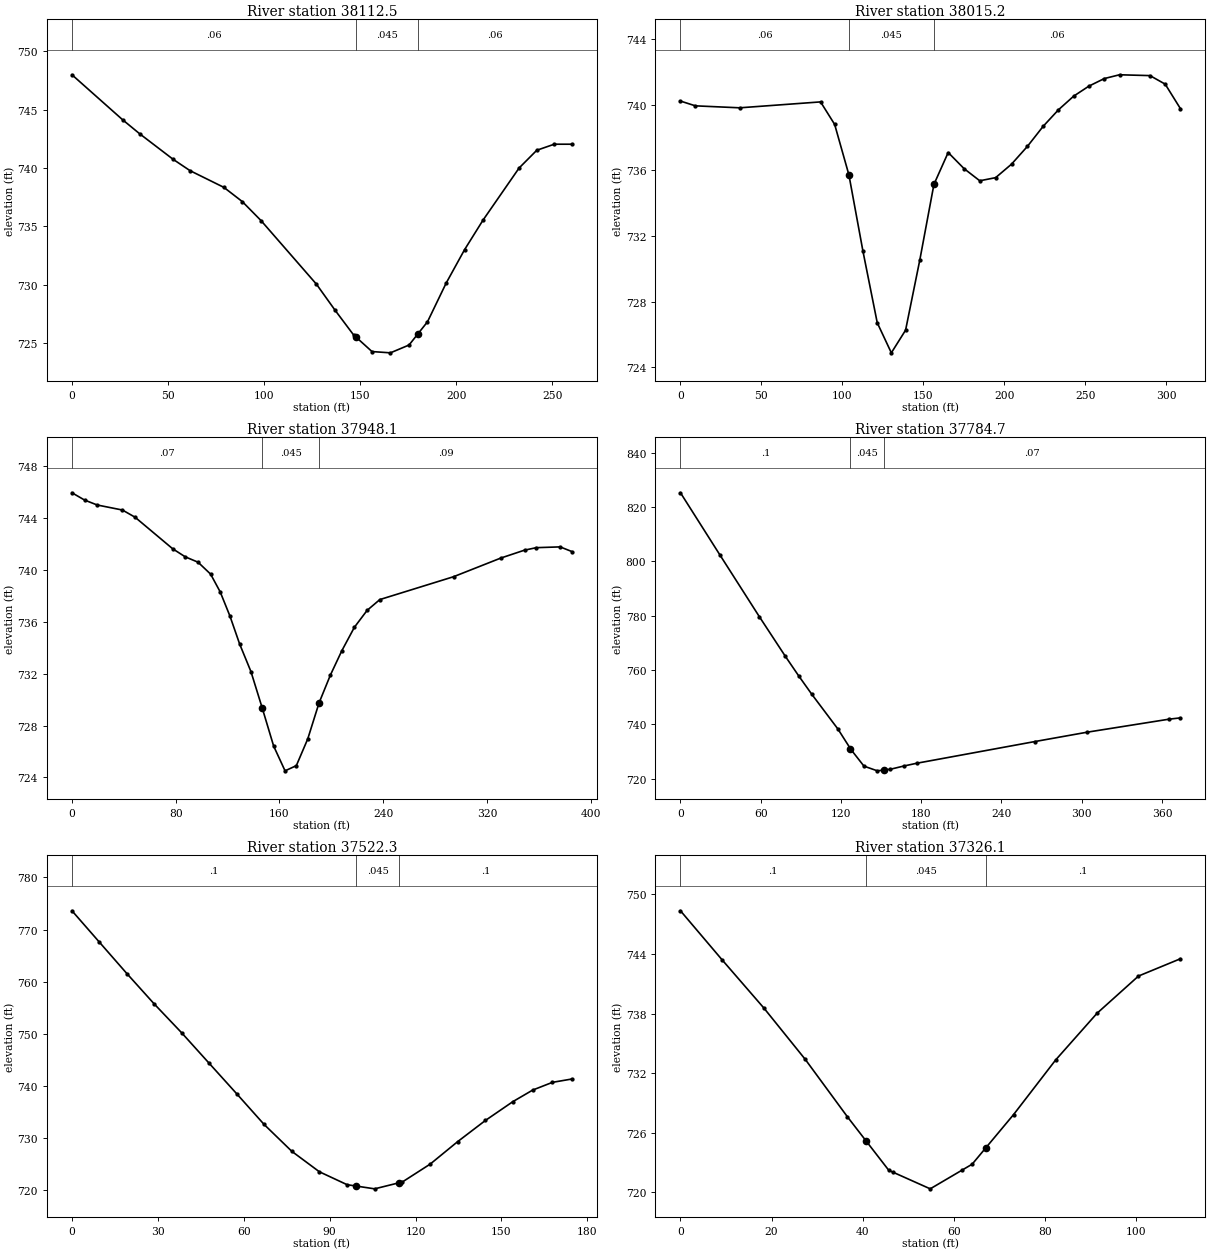
Type RM Length L Ch R = 1 ,38112.5 ,102.4,97.3,94.2
XS GIS Cut Line= 4
      1578793.74      391222.434     1578750.772      391156.028
     1578650.511      391051.862     1578613.934      391050.386
#Sta/Elev= 24
       0  747.99    26.4  744.13    35.2  742.94    52.7  740.74    61.5  739.77
    79.1  738.34    88.7  737.12    98.4   735.5   127.3  730.04   136.9  727.83
   146.6   725.7     148725.4915   156.2  724.27   165.8  724.16   175.5  724.83
     180725.7628   185.1  726.82   194.8  730.13   204.4     733     214  735.53
   232.8     740     242  741.52   251.1  742.04   260.3  742.04
#Mann= 3 , 0 , 0
       0     .06       0     148    .045       0     180     .06       0
Bank Sta=148,180
XS Rating Curve= 0 ,0
Exp/Cntr=0.3,0.1

Type RM Length L Ch R = 1 ,38015.2 ,66.9,67.2,66.9
XS GIS Cut Line= 6
     1578802.318      391138.135     1578799.063      391074.116
     1578793.637      391052.415     1578731.788      391003.587
      1578674.28      390991.651     1578589.625      390994.874
#Sta/Elev= 27
       0  740.21     9.2  739.92    36.6   739.8    86.5  740.16    95.2  738.79
     104  735.72   112.7  731.06   121.5  726.72   130.2  724.89     139  726.27
   147.8  730.55   156.5  735.14   165.3  737.08   175.1   736.1   184.8  735.36
   194.6  735.55   204.4  736.37   214.2  737.45     224  738.68   233.4  739.68
   242.8  740.51   252.2  741.12   261.7  741.58   271.1  741.81   289.9  741.76
   299.3  741.24   308.7  739.75
#Mann= 3 , 0 , 0
       0     .06       0     104    .045       0   156.5     .06       0
Bank Sta=104,156.5
XS Rating Curve= 0 ,0
Exp/Cntr=0.3,0.1

Type RM Length L Ch R = 1 ,37948.1 ,182.5,163.4,143.9
XS GIS Cut Line= 6
     1578849.173      391132.026     1578843.551      391025.288
     1578838.125      391003.587     1578776.276      390954.759
     1578718.768      390942.823     1578600.041      390943.658
#Sta/Elev= 30
       0  745.94     9.7  745.38    19.4     745    38.9  744.61    48.6  744.06
    77.7  741.62    87.4     741    97.2  740.59   106.9  739.67   114.3   738.3
   121.8  736.44   129.3  734.28     138  732.16   146.8  729.32   155.5  726.42
   164.3  724.51     173  724.91   181.8  726.97   190.5  729.74   199.3   731.9
   208.1  733.77   217.8  735.58   227.6  736.88   237.4  737.71   294.2  739.47
   330.7  740.91     349  741.52   358.1  741.71   376.4  741.77   385.5  741.41
#Mann= 3 , 0 , 0
       0     .07       0   146.8    .045       0   190.5     .09       0
Bank Sta=146.8,190.5
XS Rating Curve= 0 ,0
Exp/Cntr=0.3,0.1

Type RM Length L Ch R = 1 ,37784.7 ,256.7,262.4,266.6
XS GIS Cut Line= 4
     1578987.194      390765.707     1578885.868      390825.635
     1578692.726      390861.443     1578633.047      390861.443
#Sta/Elev= 19
       0  825.26    29.4  802.45    58.9  779.72    78.5  765.02    88.3  757.95
    98.1  751.17   117.7  738.34     127731.1467   127.5  730.76   137.2  724.67
   147.2  722.94   152.2  723.24     157  723.53   166.8  724.69   176.6  725.73
     265  733.72   304.3  737.18   365.3  741.95   373.8  742.43
#Mann= 3 , 0 , 0
       0      .1       0     127    .045       0   152.2     .07       0
Bank Sta=127,152.2
XS Rating Curve= 0 ,0
Exp/Cntr=0.3,0.1

Type RM Length L Ch R = 1 ,37522.3 ,187,196.2,206.3
XS GIS Cut Line= 4
     1578826.189      390625.983     1578769.766      390615.132
     1578673.195      390615.132     1578653.663      390608.622
#Sta/Elev= 22
       0   773.6     9.6  767.57    19.2  761.55    28.7  755.76    38.3  750.22
    47.9  744.38    57.5  738.55    67.1  732.65    76.8  727.49    86.4  723.58
    96.1   721.1    99.3  720.84   105.7  720.31   114.3  721.48   115.4  721.63
   125.1  725.05   134.7  729.36   144.4  733.42     154  737.03   160.9  739.24
   167.8  740.72   174.6  741.36
#Mann= 3 , 0 , 0
       0      .1       0    99.3    .045       0   114.3      .1       0
Bank Sta=99.3,114.3
XS Rating Curve= 0 ,0
Exp/Cntr=0.3,0.1

Type RM Length L Ch R = 1 ,37326.1 ,373.3,375.6,378.1
XS GIS Cut Line= 2
     1578817.509      390450.201     1578718.768      390402.458
#Sta/Elev= 17
       0  748.35     9.1  743.43    18.3  738.56    27.4  733.38    36.6  727.63
    40.7 725.197    45.7  722.23    46.7  722.02    54.8  720.36    61.7  722.22
      64  722.84      67724.4883    73.1  727.84    82.3  733.32    91.4  738.03
   100.5  741.78   109.7  743.52
#Mann= 3 , 0 , 0
       0      .1       0    40.7    .045       0      67      .1       0
Bank Sta=40.7,67
XS Rating Curve= 0 ,0
Exp/Cntr=0.3,0.1

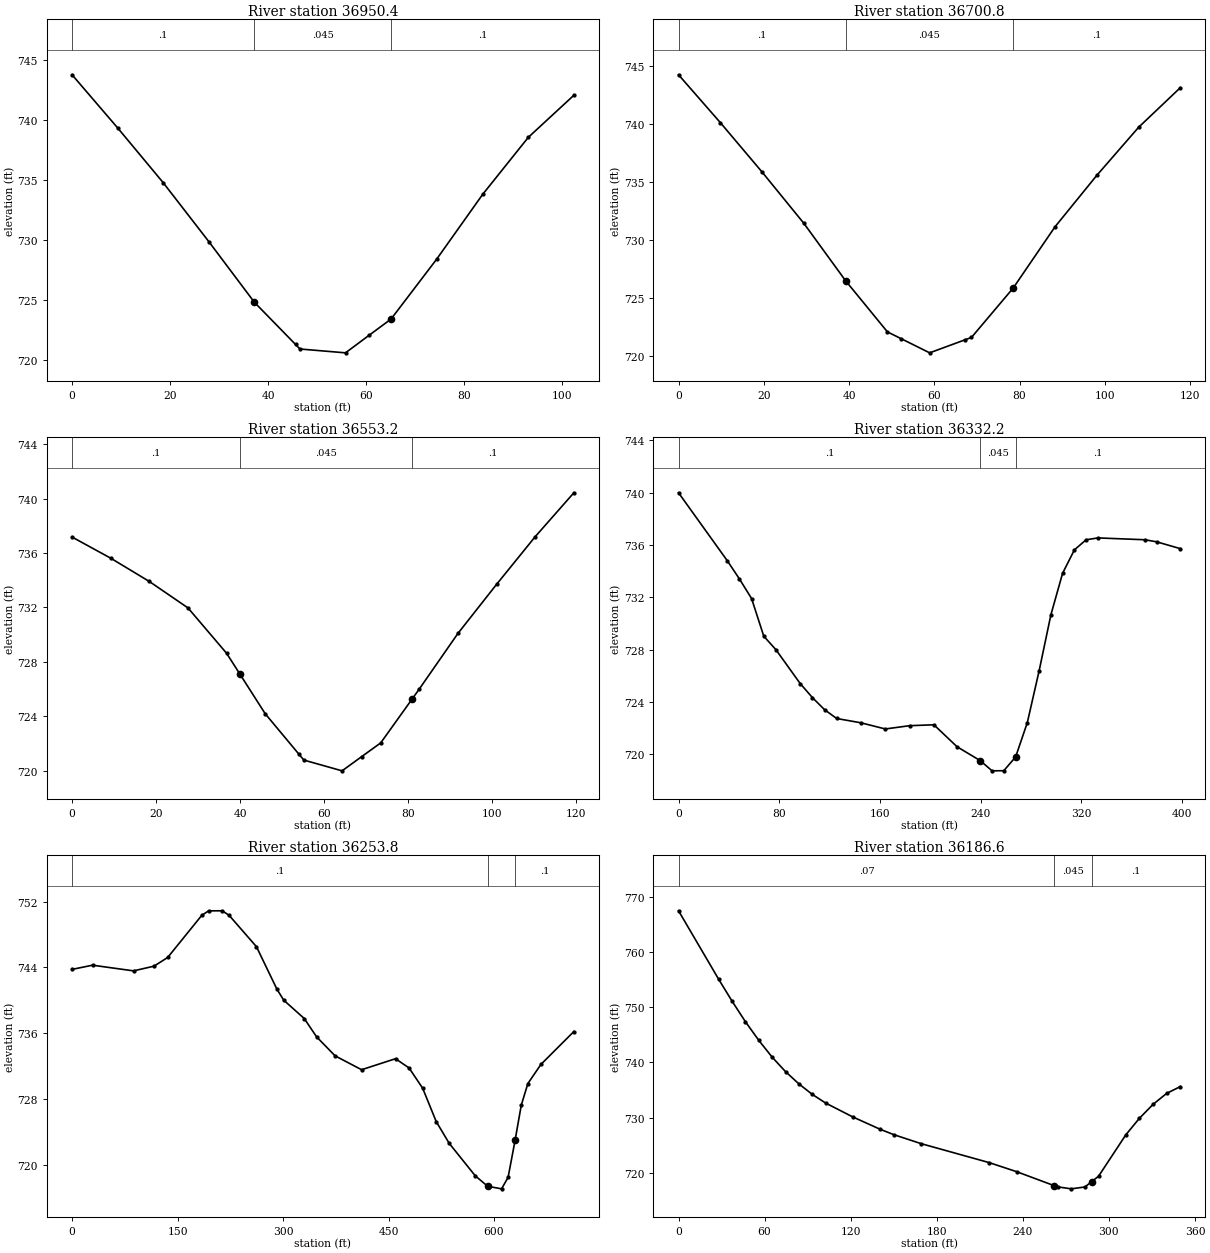
Type RM Length L Ch R = 1 ,36950.4 ,247.8,249.7,251.9
XS GIS Cut Line= 2
     1578983.525       390120.34     1578896.719      390066.087
#Sta/Elev= 14
       0  743.75     9.3  739.32    18.6  734.75    27.9  729.84    37.2  724.78
    45.6  721.26    46.5  720.88    55.8  720.56    60.6  722.02    65.1  723.38
    74.4  728.37    83.8  733.78    93.1  738.53   102.4  742.04
#Mann= 3 , 0 , 0
       0      .1       0    37.2    .045       0    65.1      .1       0
Bank Sta=37.2,65.1
XS Rating Curve= 0 ,0
Exp/Cntr=0.3,0.1

Type RM Length L Ch R = 1 ,36700.8 ,148.5,147.5,146.2
XS GIS Cut Line= 2
      1579113.95       389913.96       1579020.2       389842.78
#Sta/Elev= 15
       0  744.21     9.8   740.1    19.6  735.85    29.4  731.44    39.2   726.5
      49  722.11    52.2  721.53    58.9  720.31    67.2  721.43    68.7  721.63
    78.5  725.88    88.3  731.14    98.1  735.56   107.9  739.69   117.7   743.1
#Mann= 3 , 0 , 0
       0      .1       0    39.2    .045       0    78.5      .1       0
Bank Sta=39.2,78.5
XS Rating Curve= 0 ,0
Exp/Cntr=0.3,0.1

Type RM Length L Ch R = 1 ,36553.2 ,52.5,221.1,244.3
XS GIS Cut Line= 2
     1579193.377      389786.139     1579094.636      389718.865
#Sta/Elev= 18
       0  737.17     9.2  735.62    18.4  733.91    27.6  731.97    36.8  728.64
      40727.0957      46   724.2      54  721.24    55.2   720.8    64.3  720.01
      69  721.06    73.5  722.06      81725.2883    82.7  726.02    91.9   730.1
   101.1   733.7   110.3   737.2   119.5  740.42
#Mann= 3 , 0 , 0
       0      .1       0      40    .045       0      81      .1       0
Bank Sta=40,81
XS Rating Curve= 0 ,0
Exp/Cntr=0.3,0.1

Type RM Length L Ch R = 1 ,36332.2 ,226,78.3,74.6
XS GIS Cut Line= 5
     1579217.248      389789.394      1579185.06      389729.814
     1579220.504      389599.507     1579220.504      389562.615
     1579198.802       389405.28
#Sta/Elev= 29
       0  739.99    38.7   734.8    48.4   733.4      58  731.91    67.7  729.03
    77.4  727.99    96.7   725.4   106.3  724.34     116  723.41   125.6  722.74
   144.9  722.41   164.2  721.94   183.5  722.19   202.8  722.26   221.2  720.58
   239.6  719.52     249  718.74   258.3  718.75   267.7   719.8     277  722.43
   286.4   726.4   295.7  730.66     305  733.84   314.4  735.63   323.7   736.4
   333.1  736.54   370.4   736.4   379.8  736.24   398.5  735.72
#Mann= 3 , 0 , 0
       0      .1       0   239.6    .045       0   267.7      .1       0
Bank Sta=239.6,267.7
XS Rating Curve= 0 ,0
Exp/Cntr=0.3,0.1

Type RM Length L Ch R = 1 ,36253.8 ,81.5,67.2,53.5
XS GIS Cut Line= 6
     1579546.025      389916.347     1579254.115      389762.076
     1579244.739      389710.283     1579280.183      389579.976
     1579280.183      389543.083     1579258.481      389385.748
#Sta/Elev= 30
       0  743.76    29.1  744.27    87.4  743.58   116.5  744.15     136  745.21
   184.5  750.33   194.2  750.87   213.6  750.88   223.4  750.32   262.2  746.52
   291.3  741.36     301  740.02   330.2  737.79   347.7  735.57     374  733.26
   411.7  731.57     460  732.91   479.3  731.78   498.6  729.32   517.8  725.28
   536.3  722.63   573.4  718.68     591717.4144   610.8   717.1   620.1   718.5
     630 722.983   638.8  727.26   648.2  729.89   666.8  732.22   713.6  736.21
#Mann= 3 , 0 , 0
       0      .1       0     591    .045       0     630      .1       0
Bank Sta=591,630
XS Rating Curve= 0 ,0
Exp/Cntr=0.3,0.1

Type RM Length L Ch R = 1 ,36186.6 ,134.3,134.2,134.7
XS GIS Cut Line= 3
     1579530.834      389599.507     1579431.007      389575.635
     1579271.502      389386.833
#Sta/Elev= 27
       0  767.42      28  755.03    37.3  751.09    46.6  747.38      56  743.98
    65.3  740.95    74.6  738.34      84  736.11    93.3  734.22   102.6  732.66
   121.6  730.14   140.7  727.91   150.2  726.94   169.2  725.32   216.7  721.89
   235.7  720.26     262717.7215   264.2  717.52   273.8  717.16   283.3   717.5
     288718.4594   292.8  719.44   311.8  726.92   321.3  729.92   330.8  732.43
   340.3  734.42   349.8  735.64
#Mann= 3 , 0 , 0
       0     .07       0     262    .045       0     288      .1       0
Bank Sta=262,288
XS Rating Curve= 0 ,0
Exp/Cntr=0.3,0.1

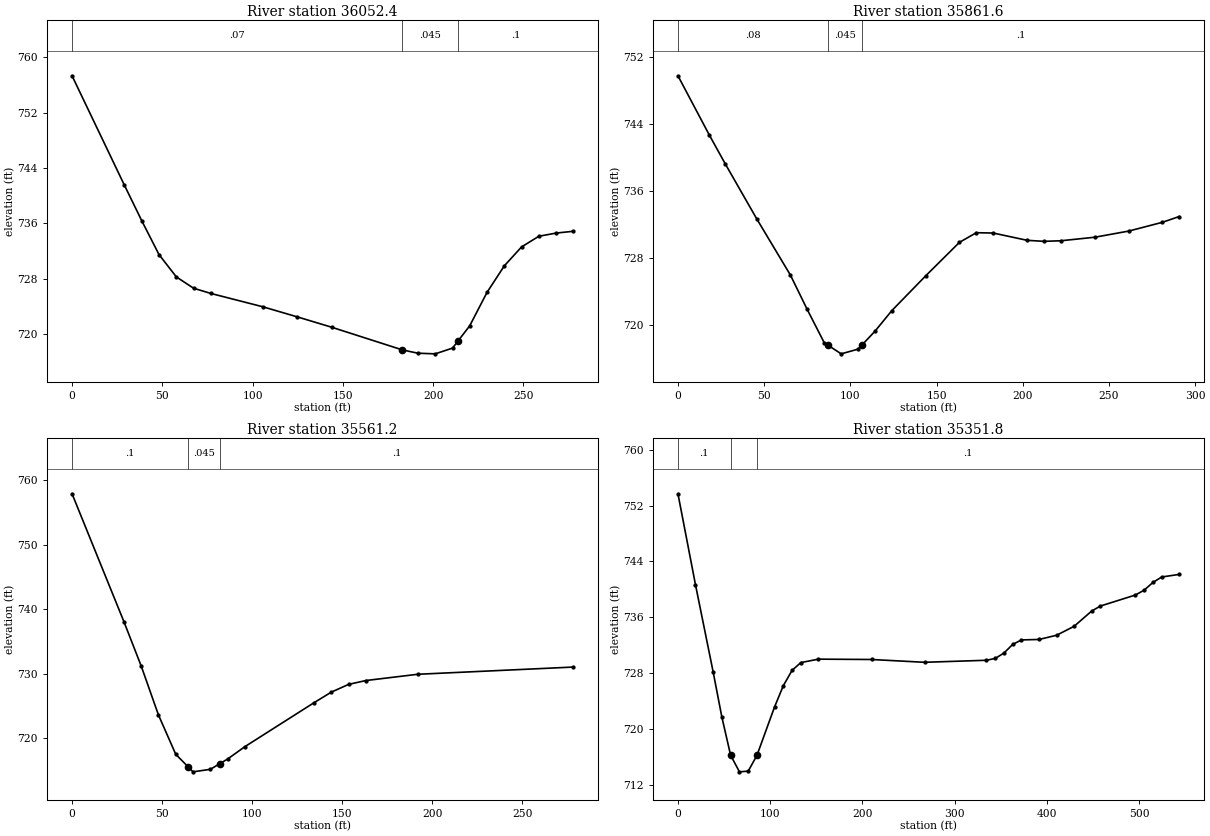
Type RM Length L Ch R = 1 ,36052.4 ,213.5,190.8,167.6
XS GIS Cut Line= 3
     1579544.939      389482.319     1579503.707      389457.363
     1579356.137      389281.582
#Sta/Elev= 22
       0  757.33    28.9  741.57    38.6  736.38    48.2  731.47    57.8  728.25
    67.3  726.62    76.9  725.86   105.6  723.94   124.7  722.48   143.8  720.98
     183717.6998   191.6  717.22   201.2  717.13   210.8  717.96     214719.0446
   220.3  721.18   229.9  726.02   239.5  729.86     249  732.58   258.6  734.13
   268.2  734.59   277.7  734.85
#Mann= 3 , 0 , 0
       0     .07       0     183    .045       0     214      .1       0
Bank Sta=183,214
XS Rating Curve= 0 ,0
Exp/Cntr=0.3,0.1

Type RM Length L Ch R = 1 ,35861.6 ,315.1,300.4,285.4
XS GIS Cut Line= 3
     1579585.087      389150.288     1579543.854      389169.819
     1579300.853      389202.523
#Sta/Elev= 24
       0  749.74    18.2  742.67    27.4  739.25    45.6  732.71    65.2  725.98
      75  721.86    84.9  717.88    86.8  717.63    94.7  716.57   104.5  717.13
     107 717.676   114.3  719.27   124.1  721.73   143.7  725.87   163.3  729.87
   173.1  731.02   182.9  730.98   202.6  730.11   212.4  729.99   222.2  730.06
   241.8  730.48   261.4  731.21     281  732.26   290.8  732.95
#Mann= 3 , 0 , 0
       0     .08       0    86.8    .045       0     107      .1       0
Bank Sta=86.8,107
XS Rating Curve= 0 ,0
Exp/Cntr=0.3,0.1

Type RM Length L Ch R = 1 ,35561.2 ,212,209.4,206.9
XS GIS Cut Line= 2
     1579383.264      388876.851     1579187.572      389074.919
#Sta/Elev= 17
       0  757.89    28.8  738.05    38.4  731.17      48  723.56    57.6  717.46
    64.6  715.48    67.2  714.74    76.8  715.13      82715.9988    86.4  716.73
      96  718.65   134.4  725.47     144  727.11   153.6  728.31   163.2  728.91
     192  729.88   278.4     731
#Mann= 3 , 0 , 0
       0      .1       0    64.6    .045       0      82      .1       0
Bank Sta=64.6,82
XS Rating Curve= 0 ,0
Exp/Cntr=0.3,0.1

Type RM Length L Ch R = 1 ,35351.8 ,95.7,109.6,123.1
XS GIS Cut Line= 4
     1579228.099      388727.111     1579139.123      388838.873
     1579113.082       389028.76     1578981.788      389191.521
#Sta/Elev= 30
       0  753.69      19  740.68    38.1  728.24    47.6  721.74    57.1  716.27
    66.7  713.89    76.2  713.99    85.7  716.26   104.8  723.19   114.3  726.23
   123.8  728.42   133.3  729.53   152.4  730.02   209.9  729.97   267.4  729.57
   334.5  729.86     344  730.12   353.5  730.89     363  732.13   372.5  732.77
   391.6  732.84   410.6  733.44   429.6  734.72   448.6   736.9   458.1  737.62
   496.1   739.2   505.6   739.9   515.1     741   524.6  741.78   543.6  742.15
#Mann= 3 , 0 , 0
       0      .1       0    57.1    .045       0    85.7      .1       0
Bank Sta=57.1,85.7
XS Rating Curve= 0 ,0
Exp/Cntr=0.3,0.1