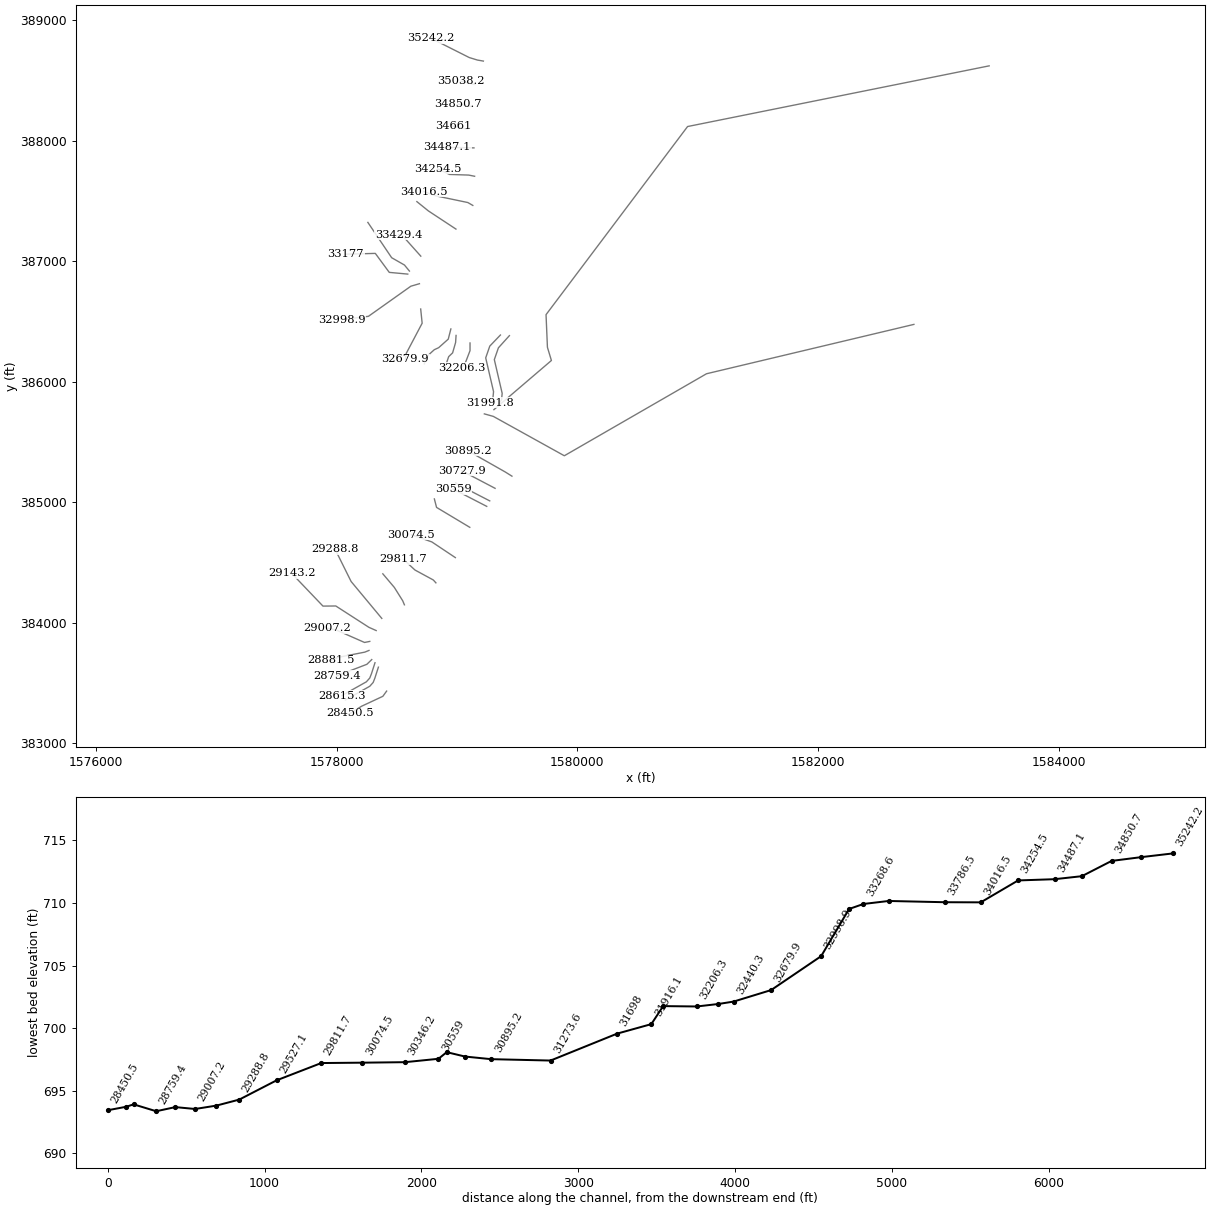
HEC-RAS study PTPLSCRK.prj: PTPLSCRK

--- PTPLSCRK.g01 (geometry) --- (continued)

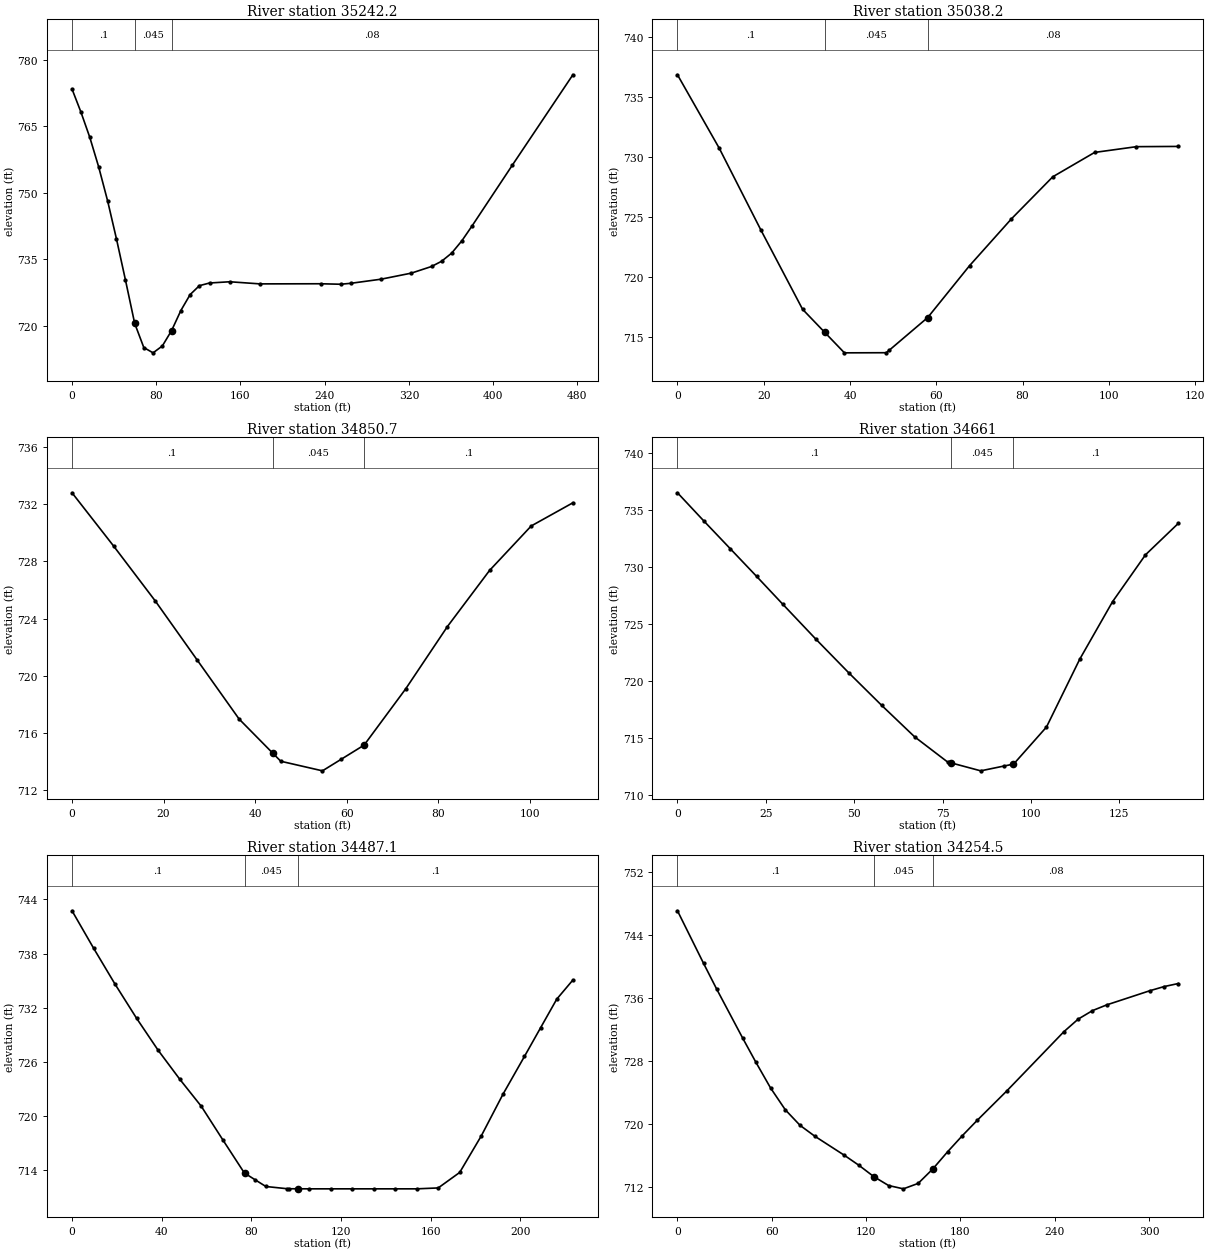
Type RM Length L Ch R = 1 ,35242.2 ,202.6,204,205.3
XS GIS Cut Line= 4
     1579219.419      388663.092     1579169.505      388671.773
     1579102.231      388692.389     1578785.391      388851.894
#Sta/Elev= 30
       0  773.41     8.4  768.26    16.9  762.52    25.3  755.88    33.8  748.22
    42.2  739.66    50.7  730.44    59.5  720.62    68.2  715.15      77  713.96
    85.8  715.51    94.6  718.98   103.4   723.5   112.2  727.09     121   729.1
   130.6   729.7   149.8  729.98   178.6   729.5   236.1  729.53   255.2  729.42
   264.8  729.63   293.6  730.56   322.4  731.93   341.5  733.42   351.1   734.6
   360.7  736.45   370.3   739.2   379.9  742.52   418.2  756.23   475.8  776.63
#Mann= 3 , 0 , 0
       0      .1       0    59.5    .045       0    94.6     .08       0
Bank Sta=59.5,94.6
XS Rating Curve= 0 ,0
Exp/Cntr=0.3,0.1

Type RM Length L Ch R = 1 ,35038.2 ,186.4,187.5,188.5
XS GIS Cut Line= 2
     1579147.804      388468.865     1579034.957      388495.991
#Sta/Elev= 15
       0  736.83     9.7   730.7    19.3  723.92      29  717.29    34.1  715.38
    38.7  713.66    48.4  713.67    49.1  713.88      58   716.6    67.7  720.92
    77.4  724.82      87  728.33    96.7  730.36   106.4  730.84   116.1  730.86
#Mann= 3 , 0 , 0
       0      .1       0    34.1    .045       0      58     .08       0
Bank Sta=34.1,58
XS Rating Curve= 0 ,0
Exp/Cntr=0.3,0.1

Type RM Length L Ch R = 1 ,34850.7 ,190.1,189.7,189.4
XS GIS Cut Line= 2
     1579114.167      388286.573     1579006.745      388307.189
#Sta/Elev= 15
       0   732.8     9.1  729.07    18.2  725.23    27.4  721.08    36.5  716.98
    43.8  714.61    45.6  714.03    54.7  713.36    58.8  714.17    63.8  715.16
    72.9   719.1      82  723.45    91.2  727.37   100.3  730.48   109.4   732.1
#Mann= 3 , 0 , 0
       0      .1       0    43.8    .045       0    63.8      .1       0
Bank Sta=43.8,63.8
XS Rating Curve= 0 ,0
Exp/Cntr=0.3,0.1

Type RM Length L Ch R = 1 ,34661   ,169.1,173.9,178.2
XS GIS Cut Line= 3
     1579105.486      388105.366     1579076.189      388099.941
     1578966.597      388122.727
#Sta/Elev= 20
       0  736.51     7.4  734.06    14.9  731.62    22.4  729.18    29.8  726.74
    39.1   723.7    48.4  720.75    57.8  717.87    67.1  715.12    76.4  712.92
    77.5  712.83    85.8  712.14    92.5  712.57      95712.7238    95.1  712.73
   104.4  715.98   113.8  721.92   123.1  726.97   132.4  731.07   141.7  733.83
#Mann= 3 , 0 , 0
       0      .1       0    77.5    .045       0      95      .1       0
Bank Sta=77.5,95
XS Rating Curve= 0 ,0
Exp/Cntr=0.3,0.1

Type RM Length L Ch R = 1 ,34487.1 ,232.8,232.6,232.3
XS GIS Cut Line= 3
     1579141.294      387942.606     1578939.471      387946.946
     1578918.854      387953.457
#Sta/Elev= 29
       0  742.74     9.6   738.6    19.2   734.6    28.8  730.82    38.4  727.28
    48.1  724.05    57.7  721.05    67.3  717.33    76.9  713.66      77713.6442
    81.8  712.89    86.5  712.16    96.1  711.91    96.8  711.91     101711.9053
   105.7   711.9   115.4   711.9     125   711.9   134.6   711.9   144.2   711.9
   153.8   711.9   163.4     712     173  713.72   182.6  717.76   192.3  722.39
   201.9  726.59   209.1  729.77   216.3  732.94   223.5  735.06
#Mann= 3 , 0 , 0
       0      .1       0      77    .045       0     101      .1       0
Bank Sta=77,101
XS Rating Curve= 0 ,0
Exp/Cntr=0.3,0.1

Type RM Length L Ch R = 1 ,34254.5 ,242,238,233.7
XS GIS Cut Line= 4
     1579146.719      387707.146     1579097.891      387716.911
     1578938.386      387722.337     1578839.644      387768.995
#Sta/Elev= 27
       0  747.12    16.6  740.44    24.9  737.19    41.5  730.94    49.8  727.91
    59.2  724.62    68.6  721.84      78  719.86    87.4  718.48   106.1  716.07
   115.5  714.78   124.9  713.35   134.3  712.22   143.7   711.8   153.1  712.49
   162.4  714.32   171.8   716.5   181.2  718.55   190.6  720.49   209.4  724.22
   245.8  731.76   254.9  733.36     264  734.44   273.1  735.17   300.4  736.96
   309.5  737.49   318.6  737.88
#Mann= 3 , 0 , 0
       0      .1       0   124.9    .045       0   162.4     .08       0
Bank Sta=124.9,162.4
XS Rating Curve= 0 ,0
Exp/Cntr=0.3,0.1

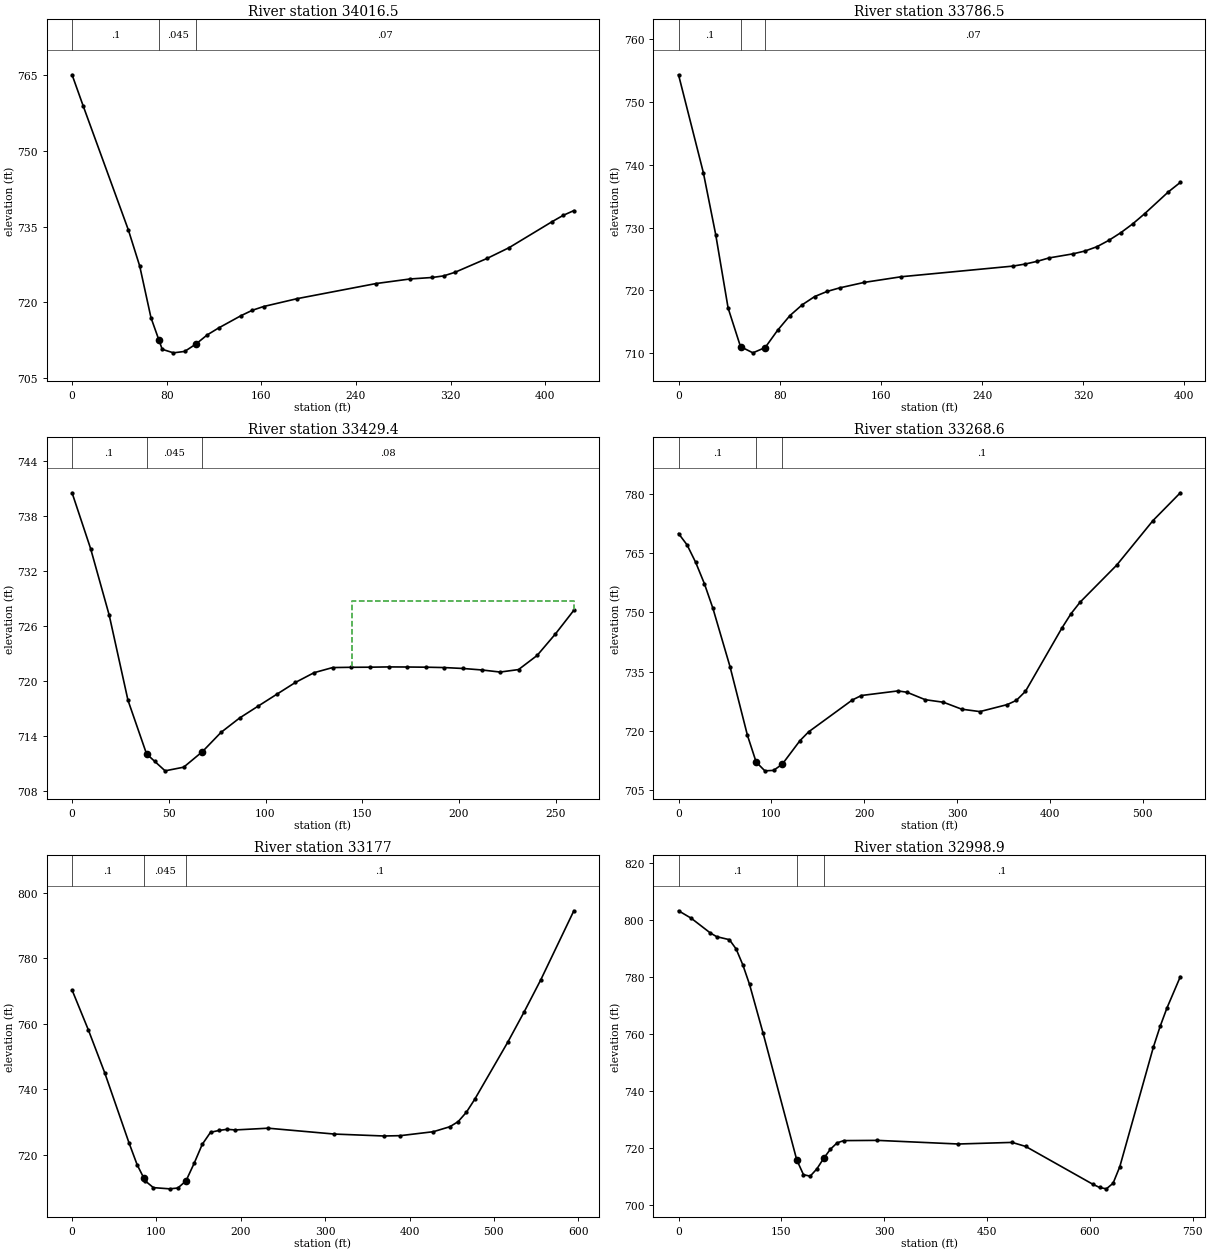
Type RM Length L Ch R = 1 ,34016.5 ,238.4,230,221.3
XS GIS Cut Line= 4
     1579131.528      387465.175     1579090.295      387489.047
     1578820.113       387545.47     1578725.712      387580.193
#Sta/Elev= 26
       0  764.98     9.5  758.76    47.6  734.32    57.2  727.18    66.7     717
   73.52712.5132    76.2  710.75    85.7  710.05    95.2  710.33   104.8   711.8
   114.3   713.6   123.8  714.95   142.8  717.39   152.3  718.45   161.9   719.2
   190.4  720.76     257  723.74   285.6  724.64   304.6  724.94   314.1  725.25
   323.7  725.96   351.1  728.73   369.4  730.82     406  735.99   415.1   737.2
   424.2  738.15
#Mann= 3 , 0 , 0
       0      .1       0   73.52    .045       0   104.8     .07       0
Bank Sta=73.52,104.8
XS Rating Curve= 0 ,0
Exp/Cntr=0.3,0.1

Type RM Length L Ch R = 1 ,33786.5 ,362.5,357.1,350.9
XS GIS Cut Line= 3
     1578991.554      387268.778     1578762.604      387419.602
     1578667.118      387496.642
#Sta/Elev= 28
       0   754.3    19.6  738.75    29.4  728.87    39.2  717.19      49  711.05
    58.8  710.06    68.5   710.9    78.3  713.64    88.1  715.99    97.9  717.72
   107.7  719.02   117.5  719.83   127.3  720.39   146.9  721.27   176.2  722.17
   264.4  723.86   274.2  724.19   283.6  724.62     293  725.16   311.9  725.81
   321.4  726.26   330.8  726.94   340.2  727.95   349.7  729.17   359.1  730.57
   368.5  732.18   387.4  735.68   396.8  737.18
#Mann= 3 , 0 , 0
       0      .1       0      49    .045       0    68.5     .07       0
Bank Sta=49,68.5
XS Rating Curve= 0 ,0
Exp/Cntr=0.3,0.1

Type RM Length L Ch R = 1 ,33429.4 ,153.4,160.8,167.9
XS GIS Cut Line= 3
      1578699.67      387044.168     1578552.101      387209.099
     1578516.294       387222.12
#Sta/Elev= 29
       0  740.53     9.6  734.42    19.2  727.16    28.9  717.87    38.5  712.01
    42.7   711.2    48.1  710.16    57.7  710.56    67.4  712.26      77  714.36
    86.6  715.93    96.2  717.23   105.8  718.52   115.5  719.82   125.1  720.88
   134.7  721.44   144.3  721.47     154  721.48   163.6  721.51   173.2   721.5
   182.8  721.48   192.4  721.44   202.1  721.34   211.7  721.18   221.3  720.95
   230.8  721.22   240.4  722.76   249.9  725.12   259.4   727.7
#Mann= 3 , 0 , 0
       0      .1       0    38.5    .045       0    67.4     .08       0
#XS Ineff= 2 , 0
                           144.9          728.72
Permanent Ineff=
       F       F
Bank Sta=38.5,67.4
XS Rating Curve= 0 ,0
Exp/Cntr=0.3,0.1

Type RM Length L Ch R = 1 ,33268.6 ,82.2,91.7,101.3
XS GIS Cut Line= 4
     1578605.269       386920.47     1578564.037      386970.384
       1578457.7      387031.148     1578260.217      387324.116
#Sta/Elev= 30
       0  769.96     9.2  767.08    18.5  762.65    27.8   757.3      37  751.06
    55.5  736.24    74.2  718.92    83.6  712.14      93  709.92   102.4  710.03
   111.8  711.62   130.7  717.53   140.1  719.78   187.2  727.85     197  728.98
   236.3  730.14   246.1   729.8   265.7  727.92   285.4  727.27     305  725.52
   324.6  724.91   354.1  726.68   363.9  727.75   373.7  730.04   412.9  746.03
   422.8  749.69   432.6  752.61   471.8  761.92   511.1  773.25   540.5  780.27
#Mann= 3 , 0 , 0
       0      .1       0    83.6    .045       0   111.8      .1       0
Bank Sta=83.6,111.8
XS Rating Curve= 0 ,0
Exp/Cntr=0.3,0.1

Type RM Length L Ch R = 1 ,33177   ,162,178.1,194.2
XS GIS Cut Line= 4
     1578591.554      386895.094     1578437.908      386909.417
     1578322.023      387066.969     1578077.231      387060.459
#Sta/Elev= 30
       0  770.31    19.3  758.12    38.6  745.08    67.5  723.58    77.2  716.84
    85.1   712.8    86.8  711.93    96.4  709.89   115.7  709.52   125.4  709.77
     135  711.94   144.7  717.32   154.3  723.12   164.1   726.8   173.9  727.36
   183.6  727.72   193.4  727.53   232.5  728.06   310.8  726.27   369.5  725.68
   389.1  725.78   428.2  726.99   447.8  728.51   457.6  730.06   467.4  732.94
   477.2  736.86   516.4  754.34     536  763.68   555.6  773.44   594.8  794.54
#Mann= 3 , 0 , 0
       0      .1       0    85.1    .045       0     135      .1       0
Bank Sta=85.1,135
XS Rating Curve= 0 ,0
Exp/Cntr=0.3,0.1

Type RM Length L Ch R = 1 ,32998.9 ,308.4,319,329.6
XS GIS Cut Line= 4
     1578688.386      386815.436     1578617.205      386794.602
     1578264.775      386544.602     1578040.816      386516.825
#Sta/Elev= 30
       0  803.18    18.5  800.57    46.4   795.4    55.6  794.11    74.2  793.05
      84   789.8    93.8  784.22   103.6  777.35   123.3  760.32   172.4  715.92
   182.2  710.72     192  710.18   201.8  712.75   211.6  716.39   221.5  719.63
   231.3  721.86   241.1  722.65   290.2  722.73   408.1  721.46   486.6  722.02
   506.3  720.61   604.4  707.34   614.2  706.22     624  705.75   633.8   707.7
   643.6   713.5   692.7  755.49   702.5   762.7   712.3  769.06   731.9   780.1
#Mann= 3 , 0 , 0
       0      .1       0   172.4    .045       0   211.6      .1       0
Bank Sta=172.4,211.6
XS Rating Curve= 0 ,0
Exp/Cntr=0.3,0.1

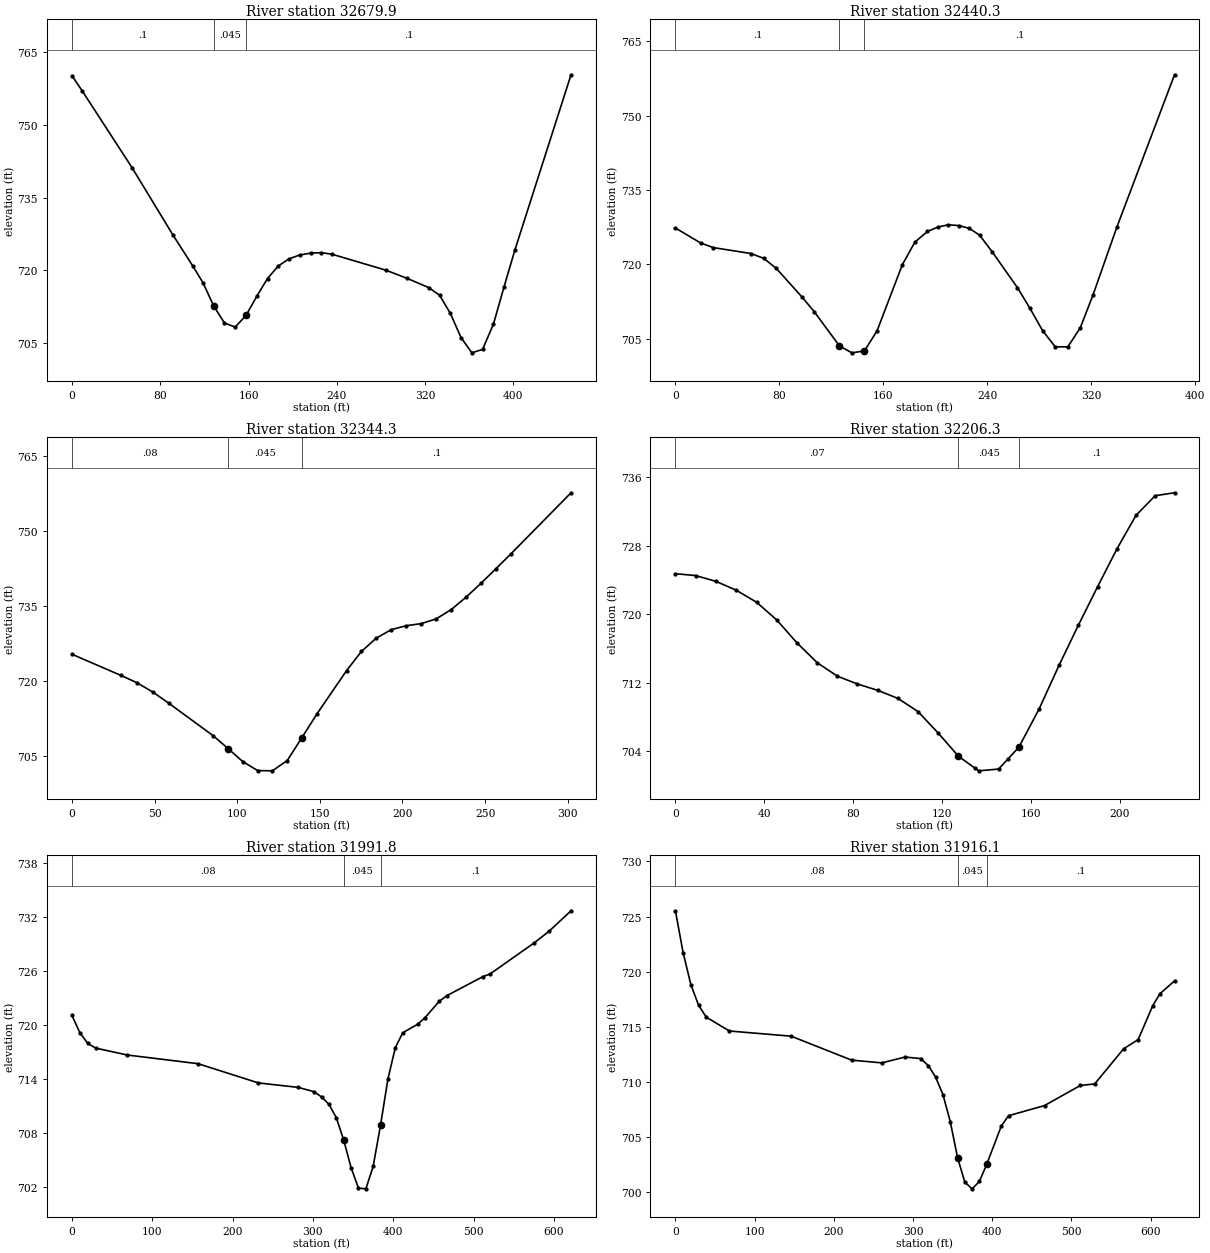
Type RM Length L Ch R = 1 ,32679.9 ,248.1,239.6,231.4
XS GIS Cut Line= 4
     1578698.802      386605.366     1578710.955      386487.311
     1578579.011      386237.311     1578572.066      386186.964
#Sta/Elev= 30
       0  760.09     9.1  757.03    54.8  741.03    91.3  727.37   109.6  720.88
   118.7  717.49   128.4  712.71   138.2  709.18   147.9  708.34   157.7  710.73
   167.4  714.65   177.2  718.34   186.9   720.9   196.7  722.39   206.4  723.18
   216.2  723.56   225.9  723.66   235.6  723.34   284.4  720.06   303.9  718.35
   323.4  716.46   333.1  714.89   342.9  711.15   352.6  706.15   362.4  703.04
   372.1  703.76   381.9  708.94   391.6  716.68   401.4  724.25   452.2  760.27
#Mann= 3 , 0 , 0
       0      .1       0   128.4    .045       0   157.7      .1       0
Bank Sta=128.4,157.7
XS Rating Curve= 0 ,0
Exp/Cntr=0.3,0.1

Type RM Length L Ch R = 1 ,32440.3 ,82.7,96,108.8
XS GIS Cut Line= 6
     1578949.453      386439.929     1578927.752      386355.294
     1578848.064      386284.417     1578811.606       386267.49
     1578739.992      386202.386     1578729.575      386150.303
#Sta/Elev= 30
       0  727.31    19.4  724.29    29.1  723.36    58.2  722.16      68  721.18
    77.7  719.14    97.1  713.48   106.8  710.44   126.2  703.53   135.8  702.12
   145.5  702.51   155.2  706.57   174.6  719.88   184.3  724.46     194  726.62
   202.1  727.51   210.1  727.96   218.1   727.8   226.2  727.24   234.2  725.83
   243.9  722.47   263.2  715.28   272.9  711.09   282.6  706.59   292.3  703.34
     302  703.32   311.6  707.18   321.3  713.74   339.8  727.53   384.1  758.23
#Mann= 3 , 0 , 0
       0      .1       0   126.2    .045       0   145.5      .1       0
Bank Sta=126.2,145.5
XS Rating Curve= 0 ,0
Exp/Cntr=0.3,0.1

Type RM Length L Ch R = 1 ,32344.3 ,139.7,137.9,136.3
XS GIS Cut Line= 5
     1578992.596       386385.98     1578988.689      386327.386
      1578963.95      386241.448     1578931.398      386210.198
     1578896.242      386107.334
#Sta/Elev= 26
       0  725.28    29.4  721.08    39.2   719.6    48.9  717.72    58.7  715.45
    85.6  708.93    94.5  706.38   103.4  703.78   112.4  701.98   121.3  701.93
   130.3     704   139.2   708.6   148.2  713.31   166.2  722.01   175.2  725.85
   184.2  728.52   193.3  730.22   202.3  730.99   211.4  731.42   220.4  732.36
   229.5  734.23   238.6  736.74   247.6  739.52   256.7  742.45   265.8  745.44
     302  757.62
#Mann= 3 , 0 , 0
       0     .08       0    94.5    .045       0   139.2      .1       0
Bank Sta=94.5,139.2
XS Rating Curve= 0 ,0
Exp/Cntr=0.3,0.1

Type RM Length L Ch R = 1 ,32206.3 ,198.8,214.6,230.5
XS GIS Cut Line= 4
     1579108.481       386323.48     1579108.481      386259.678
     1579069.419      386158.115     1579036.867      386117.751
#Sta/Elev= 28
       0  724.73     9.1  724.51    18.2  723.84    27.3  722.81    36.5   721.4
    45.6  719.33    54.7  716.65    63.8  714.34    72.9  712.77    81.9  711.86
      91  711.12   100.1  710.18   109.1  708.65   118.2  706.14   127.3  703.44
   134.6  702.07   136.4  701.73   145.4  701.94   149.6  703.12   154.5  704.49
   163.6  708.95   172.6  714.06   181.3  718.74   189.9  723.21   198.6  727.62
   207.2  731.54   215.8  733.83   224.5  734.17
#Mann= 3 , 0 , 0
       0     .07       0   127.3    .045       0   154.5      .1       0
Bank Sta=127.3,154.5
XS Rating Curve= 0 ,0
Exp/Cntr=0.3,0.1

Type RM Length L Ch R = 1 ,31991.8 ,76.2,75.7,76.1
XS GIS Cut Line= 6
     1579360.841      386389.535     1579272.544      386297.438
     1579238.689      386199.782     1579303.794      385919.834
     1579298.585      385865.146     1579272.544      385827.386
#Sta/Elev= 30
       0  721.05     9.8  719.14    19.6  717.95    29.4  717.42    68.7  716.65
     157  715.68   232.2  713.54   281.3  713.05   300.9  712.58   310.7  711.99
   319.9  711.17   329.1  709.68   338.3  707.19   347.5  704.12   356.7  701.84
   365.9  701.76     375  704.26   384.2  708.85   393.4  713.99   402.6  717.47
   411.8  719.12   430.2  720.06   439.2  720.77   457.3  722.62   466.3  723.23
   511.5  725.36   520.5  725.66   575.5  729.12   593.8   730.4   621.3  732.69
#Mann= 3 , 0 , 0
       0     .08       0   338.3    .045       0   384.2      .1       0
Bank Sta=338.3,384.2
XS Rating Curve= 0 ,0
Exp/Cntr=0.3,0.1

Type RM Length L Ch R = 1 ,31916.1 ,245,218.1,190.1
XS GIS Cut Line= 6
     1579435.494      386384.327     1579344.158      386283.115
     1579310.304      386185.459     1579375.408      385905.511
       1579370.2      385850.823     1579344.158      385813.063
#Sta/Elev= 30
       0  725.53     9.7  721.74    19.5  718.83    29.2  716.97      39  715.88
    68.2  714.63   146.1  714.16   222.4  711.99   260.6  711.74     290  712.27
   309.6  712.13   319.5  711.48   328.6  710.43   337.8  708.86     347  706.41
   356.2  703.15   365.4  700.92   374.6  700.32   383.8     701     393  702.54
   411.4  706.01   420.6  706.95     466  707.87   511.2  709.69   529.3  709.83
   565.9  713.02   584.2  713.85   602.6  716.92   611.7  718.01   630.1  719.17
#Mann= 3 , 0 , 0
       0     .08       0   356.2    .045       0     393      .1       0
Bank Sta=356.2,393
XS Rating Curve= 0 ,0
Exp/Cntr=0.3,0.1

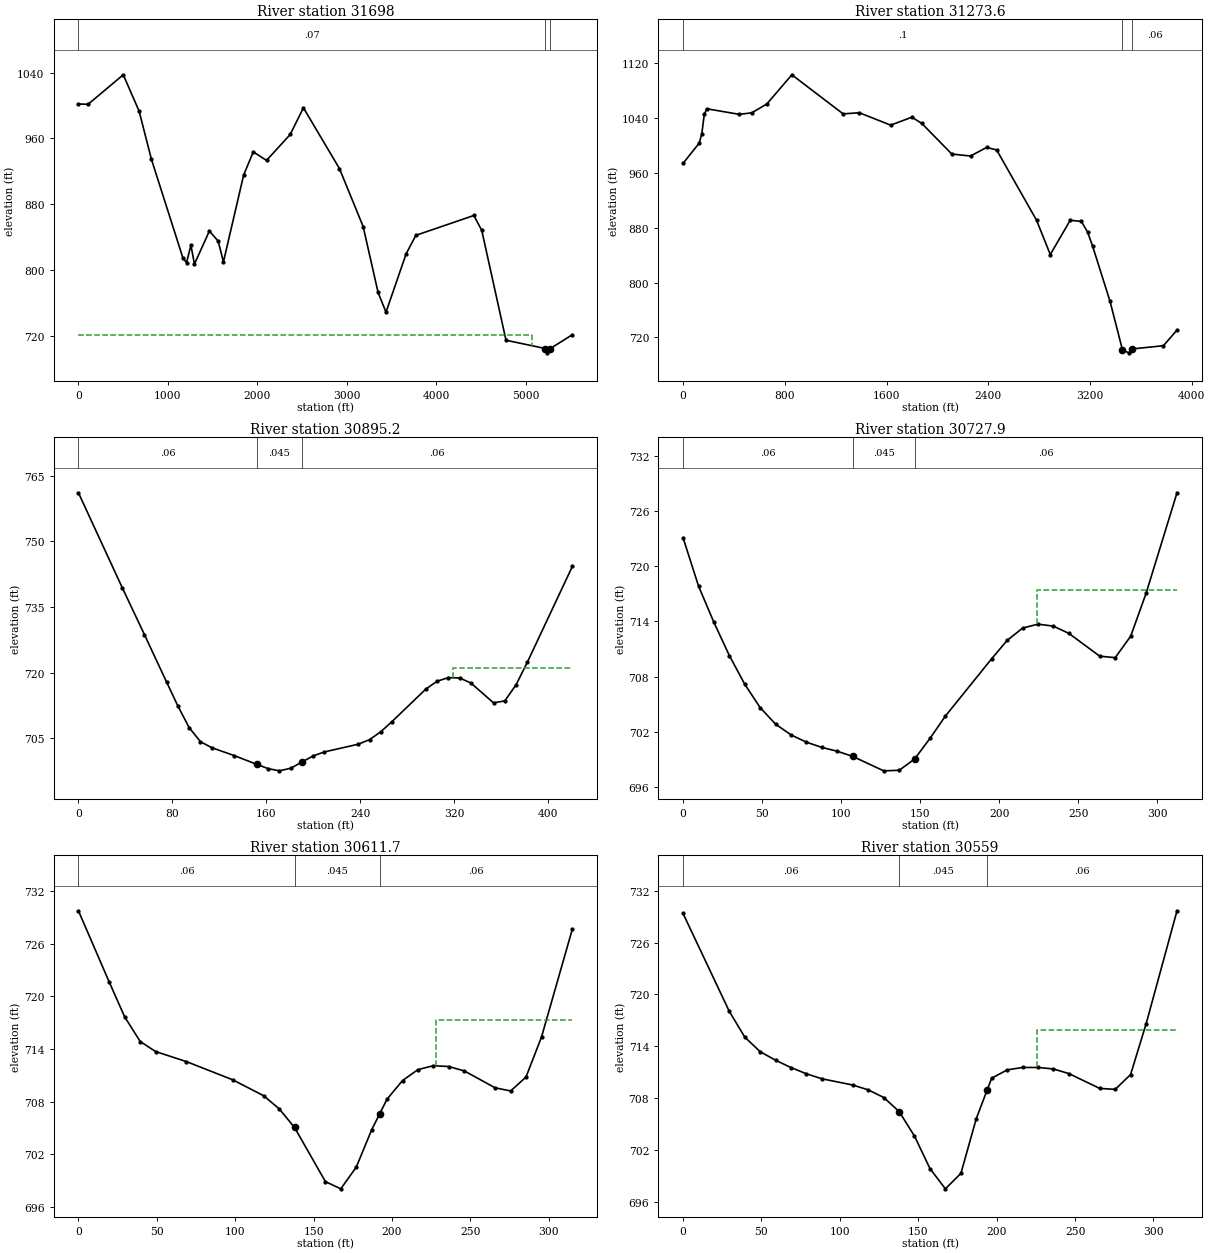
Type RM Length L Ch R = 1 ,31698   ,451.4,424.4,396.4
XS GIS Cut Line= 6
     1583419.356       388623.52     1580914.997      388119.856
     1579739.682      386558.477     1579751.276      386287.455
     1579784.262       386178.08     1579306.832      385770.094
#Sta/Elev= 30
       0  1001.8   108.1 1001.44   501.1 1037.26   677.9  993.28   815.5  934.83
  1169.2  814.44  1208.5  809.13  1257.6  830.27  1296.9  807.36  1463.9  847.48
  1562.2   835.3  1621.1  809.99  1847.1  915.54  1955.2  943.65  2102.6  933.24
  2367.8  964.78  2515.2  997.19  2917.9  923.36    3183  852.98    3350  772.86
  3438.4  748.97  3664.2  819.97  3772.3  842.27  4420.4  866.37  4508.8  848.34
  4780.1  714.87  5218.1  704.82  5237.8  699.56  5267.2  704.21  5522.3  721.62
#Mann= 3 , 0 , 0
       0     .07       0  5218.1    .045       0  5267.2     .09       0
#XS Ineff= 2 , 0
         5065.82     721
Permanent Ineff=
       F       F
Bank Sta=5218.1,5267.2
XS Rating Curve= 0 ,0
Exp/Cntr=0.3,0.1

Type RM Length L Ch R = 1 ,31273.6 ,378.4,378.4,378.4
XS GIS Cut Line= 5
     1582794.356      386477.686     1581072.133      386067.964
     1579891.578      385387.408     1579302.058      385714.105
     1579227.405      385734.938
#Sta/Elev= 30
       0  973.84   127.8 1003.59   147.5 1017.23   167.2  1045.5   186.9 1053.58
   442.6  1045.4   540.9 1047.68   658.9 1060.55   855.6 1103.16  1258.9 1046.11
  1386.7 1047.76  1632.6 1029.67  1799.7 1041.29  1878.1 1032.09  2113.4  987.49
  2260.5  984.62  2387.9  997.21  2466.3  993.41    2780  890.89  2887.9  840.84
  3044.7   890.9    3133   889.2  3181.8  873.31  3220.9     853  3357.6  772.65
  3455.3  701.82  3504.1  697.41  3533.4  703.15  3777.6  707.81  3884.4  730.65
#Mann= 3 , 0 , 0
       0      .1       0  3455.3    .045       0  3533.4     .06       0
Bank Sta=3455.3,3533.4
XS Rating Curve= 0 ,0
Exp/Cntr=0.3,0.1

Type RM Length L Ch R = 1 ,30895.2 ,166.4,167.2,167.4
XS GIS Cut Line= 3
     1579456.571      385218.011     1579401.016      385252.733
     1579091.988       385428.08
#Sta/Elev= 30
       0   761.1    37.4  739.36    56.2  728.69    75.1  717.82    84.7  712.36
    94.3  707.42   103.9   704.2   113.5  702.82   132.7  701.01   151.9  699.01
   161.5  698.04   171.2  697.52   180.8  698.11   190.4  699.53     200  700.94
   209.6  701.85   238.4  703.61     248  704.66   257.6  706.46   267.2   708.8
     296  716.23   305.6  718.02   315.2  718.84   324.8  718.75   334.4  717.59
   353.6  713.07   363.2  713.51   372.8  717.19   382.4  722.34   420.8  744.28
#Mann= 3 , 0 , 0
       0     .06       0   151.9    .045       0   190.4     .06       0
#XS Ineff= 2 , 0
                          318.87          721.12
Permanent Ineff=
       F       F
Bank Sta=151.9,190.4
XS Rating Curve= 0 ,0
Exp/Cntr=0.3,0.1

Type RM Length L Ch R = 1 ,30727.9 ,116.4,116.3,116.7
XS GIS Cut Line= 2
     1579316.597        385117.1     1579039.905      385262.499
#Sta/Elev= 28
       0  723.13     9.8  717.86    19.5  713.92    29.3  710.29    39.1  707.15
    48.8  704.62    58.6  702.81    68.4  701.64    78.1  700.85    87.9  700.28
    97.7  699.86   107.4   699.3     127  697.73   136.8  697.79   146.5  699.01
   156.3  701.27     166  703.69   195.4  709.96   205.1  711.94   214.9  713.28
   224.7  713.71   234.4  713.49   244.2   712.7   263.7  710.22   273.5  710.06
   283.3   712.4     293  717.05   312.6  728.02
#Mann= 3 , 0 , 0
       0     .06       0   107.4    .045       0   146.5     .06       0
#XS Ineff= 2 , 0
                          223.83           717.4
Permanent Ineff=
       F       F
Bank Sta=107.4,146.5
XS Rating Curve= 0 ,0
Exp/Cntr=0.3,0.1

Type RM Length L Ch R = 1 ,30611.7 ,52.7,52.6,52.6
XS GIS Cut Line= 2
      1579272.11      385012.933     1578992.162      385157.247
#Sta/Elev= 26
       0  729.73    19.7  721.59    29.5  717.65    39.4  714.85    49.2  713.71
    68.9  712.56    98.4  710.49   118.1  708.68     128  707.19   137.8  705.07
   157.5   698.9   167.3  698.08   177.2  700.56     187   704.8     192706.5806
   196.8  708.29   206.7  710.41   216.5  711.65   226.4   712.1   236.2     712
   246.1   711.5   265.7  709.58   275.6  709.22   285.4   710.8   295.3  715.36
     315  727.66
#Mann= 3 , 0 , 0
       0     .06       0   137.8    .045       0     192     .06       0
#XS Ineff= 2 , 0
                          228.05          717.34
Permanent Ineff=
       F       F
Bank Sta=137.8,192
XS Rating Curve= 0 ,0
Exp/Cntr=0.3,0.1

Type RM Length L Ch R = 1 ,30559   ,214.1,212.9,211.2
XS GIS Cut Line= 2
     1579247.153       384967.36     1578967.205      385111.674
#Sta/Elev= 29
       0  729.36    29.5  718.05    39.4  715.07    49.2  713.39      59  712.41
    68.9  711.55    78.7  710.84    88.6  710.26   108.3  709.54   118.1  708.98
     128   708.1   137.8  706.48   147.6  703.64   157.5  699.88   167.3  697.55
   177.2  699.34     187  705.66     194708.9957   196.8  710.33   206.7  711.29
   216.5  711.57   226.4  711.57   236.2   711.4   246.1  710.86   265.7  709.15
   275.6  709.04   285.4  710.75   295.3  716.61     315  729.67
#Mann= 3 , 0 , 0
       0     .06       0   137.8    .045       0     194     .06       0
#XS Ineff= 2 , 0
                          225.81          715.88
Permanent Ineff=
       F       F
Bank Sta=137.8,194
XS Rating Curve= 0 ,0
Exp/Cntr=0.3,0.1

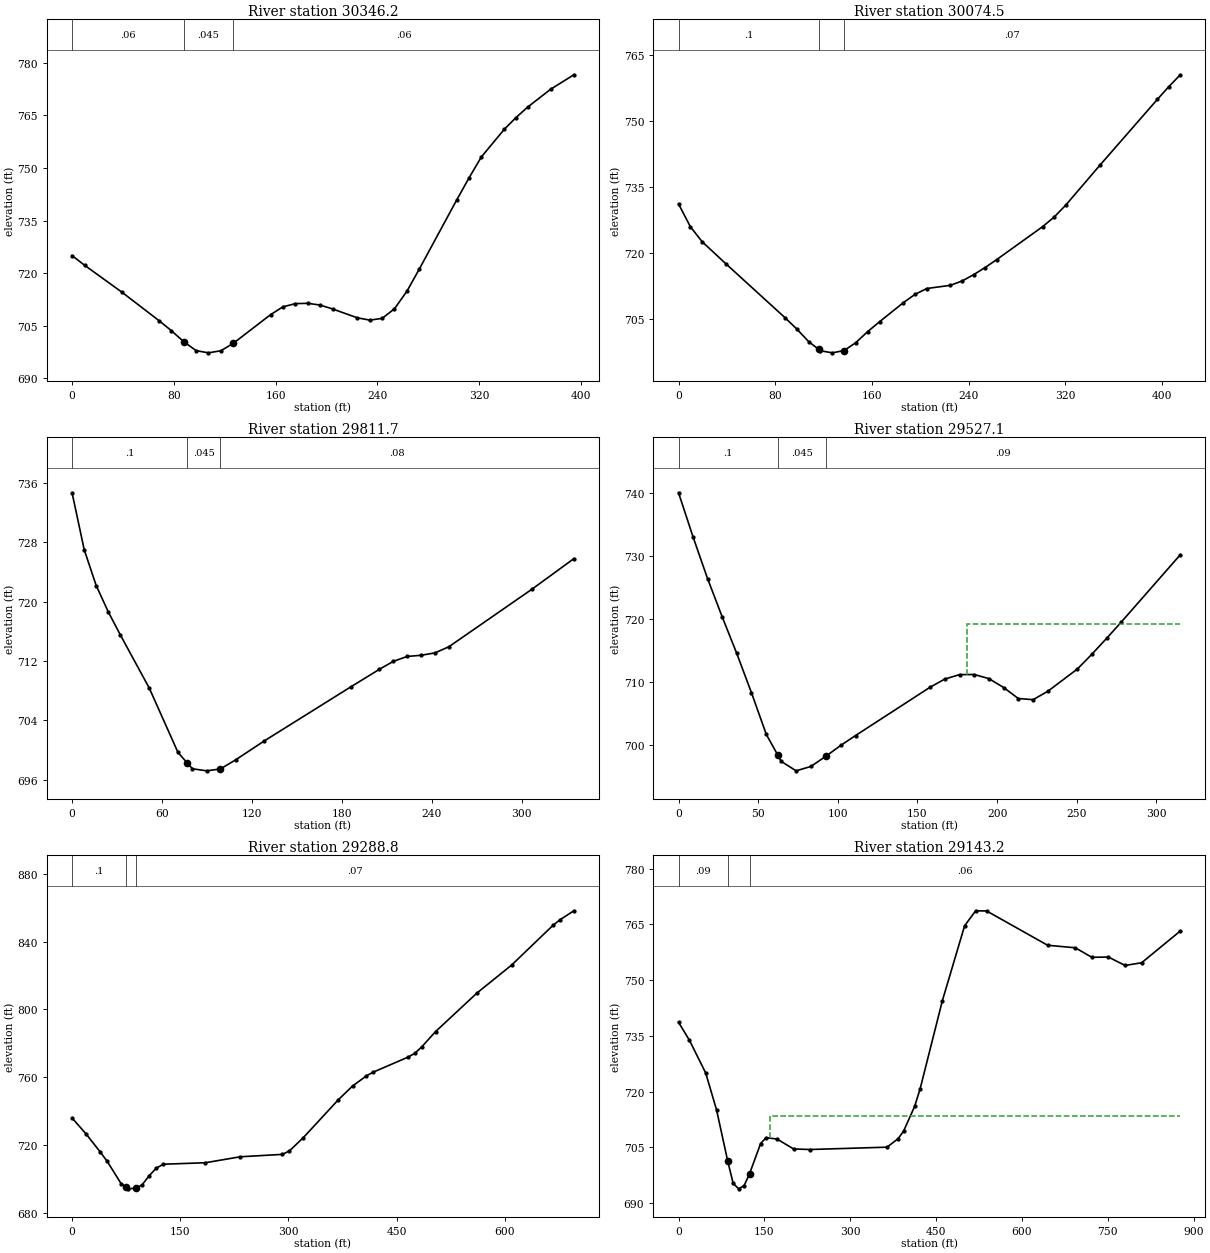
Type RM Length L Ch R = 1 ,30346.2 ,272.8,271.6,270.6
XS GIS Cut Line= 3
     1579106.552       384793.45     1578830.573      384958.721
     1578812.385      385029.099
#Sta/Elev= 30
       0  725.01     9.8  722.26      39  714.62    68.2   706.5      78  703.62
    87.7  700.48    97.5  697.91   107.2  697.28     117  697.88   126.7  699.99
     156  708.16   165.7  710.39   175.5  711.31   185.2   711.4     195   710.9
   204.7   709.8   224.2  707.27     234  706.61   243.7   707.1   253.4  709.84
   263.2  714.86   272.9  721.15   302.2  740.79   311.9   747.1   321.7  753.14
   339.8  761.05   348.9  764.35     358  767.32   376.2  772.45   394.4  776.56
#Mann= 3 , 0 , 0
       0     .06       0    87.7    .045       0   126.7     .06       0
Bank Sta=87.7,126.7
XS Rating Curve= 0 ,0
Exp/Cntr=0.3,0.1

Type RM Length L Ch R = 1 ,30074.5 ,260.8,262.9,264.9
XS GIS Cut Line= 3
     1578986.736      384542.013     1578791.424      384672.221
     1578621.068        384731.9
#Sta/Elev= 29
       0  731.06     9.8  725.88    19.6  722.47    39.1  717.49      88  705.25
    97.8  702.67   107.6  699.81     116698.0186   117.4  697.72   127.2  697.24
     137697.7586   146.7  699.56   156.5  702.06   166.3   704.3   185.8  708.59
   195.6  710.51   205.4  711.85     225  712.58   234.7  713.57   244.2     715
   253.7  716.62   263.2  718.41   301.2  725.89   310.7  728.06   320.2  730.73
   348.7  739.87   396.2  754.81   405.7  757.72   415.2   760.4
#Mann= 3 , 0 , 0
       0      .1       0     116    .045       0     137     .07       0
Bank Sta=116,137
XS Rating Curve= 0 ,0
Exp/Cntr=0.3,0.1

Type RM Length L Ch R = 1 ,29811.7 ,296.2,284.5,272.9
XS GIS Cut Line= 4
     1578825.061      384332.594      1578803.36      384356.466
      1578651.45      384438.931     1578555.964      384526.822
#Sta/Elev= 22
       0  734.65     8.1  726.99    16.1  722.16    24.2   718.6    32.3  715.48
    51.5  708.36    70.7  699.68    76.7  698.31    80.3  697.49    89.9  697.21
      99697.4659   109.1  698.68   128.3  701.24   185.9   708.5   205.1  710.88
   214.4  711.95   223.6  712.61   232.9  712.77   242.2  713.09   251.5  713.92
   307.1  721.69   334.9  725.78
#Mann= 3 , 0 , 0
       0      .1       0    76.7    .045       0      99     .08       0
Bank Sta=76.7,99
XS Rating Curve= 0 ,0
Exp/Cntr=0.3,0.1

Type RM Length L Ch R = 1 ,29527.1 ,235.2,238.3,241.2
XS GIS Cut Line= 4
     1578563.559      384150.303     1578549.453       384183.94
     1578480.009      384294.617     1578384.523      384407.464
#Sta/Elev= 28
       0  740.05     9.1  733.04    18.2  726.41    27.4  720.32    36.5  714.53
    45.8  708.24    55.1  701.62    62.4  698.29    64.5  697.33    73.8  695.83
    83.1  696.53    92.5  698.15   101.8  699.87   111.1  701.44   157.8  709.11
   167.1  710.42   176.4  711.13   185.6  711.15   194.8   710.5   204.1  709.08
   213.3  707.33   222.6  707.15   231.8  708.48   250.3  712.01   259.5  714.38
   268.8  716.92     278  719.51     315   730.2
#Mann= 3 , 0 , 0
       0      .1       0    62.4    .045       0    92.5     .09       0
#XS Ineff= 2 , 0
                          180.95           719.2
Permanent Ineff=
       F       F
Bank Sta=62.4,92.5
XS Rating Curve= 0 ,0
Exp/Cntr=0.3,0.1

Type RM Length L Ch R = 1 ,29288.8 ,138.8,145.7,152.6
XS GIS Cut Line= 3
     1578375.842      384037.455     1578120.978      384343.912
       1577988.8      384610.065
#Sta/Elev= 30
       0  736.05    19.4  726.66    38.9   716.1    48.6  710.56      68  697.35
    74.2  695.41    77.8  694.29    89.2  694.72    97.2  696.69   106.9  702.01
   116.7  706.43   126.4   708.8   184.7  709.67   233.3  713.19   291.6   714.6
   301.4  716.64   320.8  724.54   369.4  746.89   388.9  754.88   408.2  760.91
   417.8  763.11   465.7   771.9   475.3  774.17   484.9  777.99     504  786.97
   561.6  809.77   609.5   826.2     667  849.66   676.6   852.9   695.8  858.19
#Mann= 3 , 0 , 0
       0      .1       0    74.2    .045       0    89.2     .07       0
Bank Sta=74.2,89.2
XS Rating Curve= 0 ,0
Exp/Cntr=0.3,0.1

Type RM Length L Ch R = 1 ,29143.2 ,132.4,136,139.5
XS GIS Cut Line= 5
     1578329.184      383936.544      1578268.42      383963.671
     1577993.898      384140.537     1577887.253      384139.593
     1577626.821      384412.148
#Sta/Elev= 30
       0  738.65      19  733.82    47.5  724.99    66.5  715.02      86701.2241
    95.4  695.31     105  693.81   114.6  694.68   124.2  697.92   143.4  706.01
     153   707.6   172.2  707.21     201  704.55   229.8   704.4   364.3  705.03
   383.5   707.3   393.1  709.32   412.5     716   422.2   720.8     461  744.49
   499.8  764.62   519.1  768.67   538.4  768.61   644.8  759.39   693.1  758.71
   722.1  756.15   751.1  756.21   780.1  753.95   809.1  754.68   876.7  763.23
#Mann= 3 , 0 , 0
       0     .09       0      86    .045       0   124.2     .06       0
#XS Ineff= 2 , 0
                          159.35          713.33
Permanent Ineff=
       F       F
Bank Sta=86,124.2
XS Rating Curve= 0 ,0
Exp/Cntr=0.3,0.1

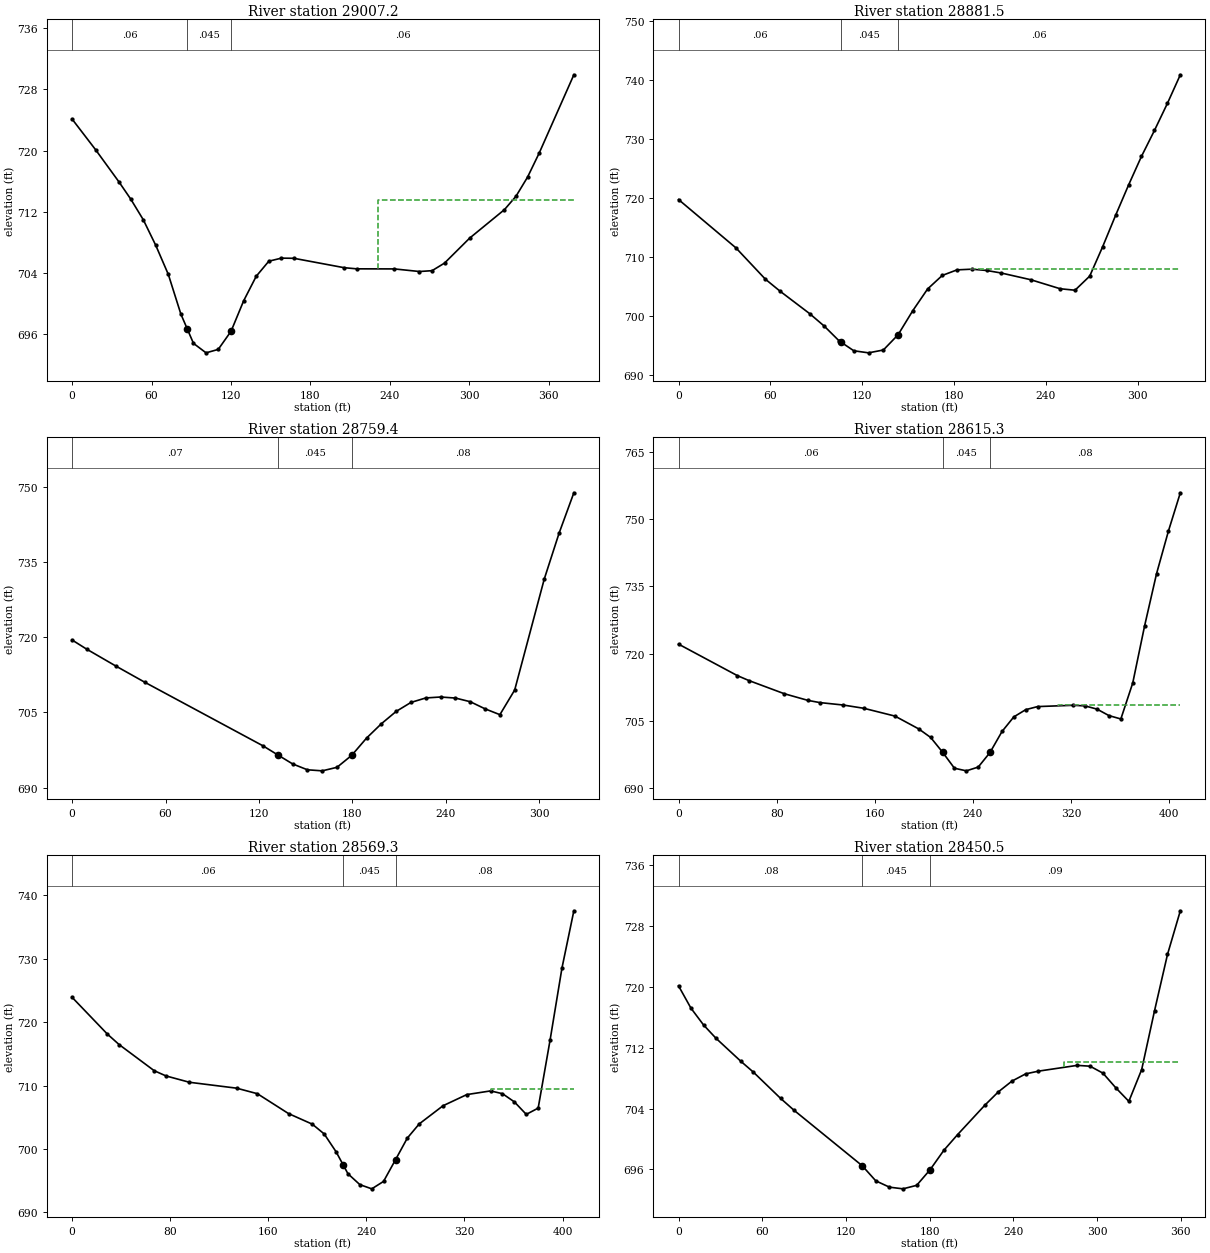
Type RM Length L Ch R = 1 ,29007.2 ,111.5,125.7,139.3
XS GIS Cut Line= 4
     1578276.016      383846.483     1578232.613      383837.803
     1577998.238      383940.884     1577921.198       383957.16
#Sta/Elev= 30
       0  724.13    17.7  720.13    35.4  715.91    44.3  713.66    53.8  710.95
    63.2  707.61    72.7   703.8    82.2   698.6      87696.6699    91.7  694.78
   101.2  693.54   110.4  693.99   120.1  696.37   129.6  700.35   139.1  703.56
   148.6  705.53   158.1  705.93   167.5  705.91   205.5  704.68     215  704.53
   243.4  704.52   262.4  704.18   271.9  704.29   281.3  705.28   300.3  708.55
   326.6  712.28   335.3  714.03     344  716.52   352.8  719.67     379  729.92
#Mann= 3 , 0 , 0
       0     .06       0      87    .045       0   120.1     .06       0
#XS Ineff= 2 , 0
                          230.88          713.53
Permanent Ineff=
       F       F
Bank Sta=87,120.1
XS Rating Curve= 0 ,0
Exp/Cntr=0.3,0.1

Type RM Length L Ch R = 1 ,28881.5 ,118.6,122.1,126.2
XS GIS Cut Line= 4
     1578269.505      383771.613     1578234.783      383757.508
     1578008.004       383713.02      1577953.75      383689.148
#Sta/Elev= 30
       0  719.69    37.5  711.49    56.7  706.19    66.4  704.13    85.6  700.35
    95.2  698.22   104.9  695.72     106695.5275   114.5  694.04   124.1  693.69
   133.8  694.17   143.4  696.75     153  700.83   162.7  704.52   172.3  706.82
   181.9  707.76   191.6  707.88   201.2  707.66   210.8  707.23   230.1  706.09
   249.3  704.56     259  704.31   268.6   706.7     277  711.65   285.5     717
     294  722.16   302.4     727   310.9  731.41   319.4  736.02   327.8  740.85
#Mann= 3 , 0 , 0
       0     .06       0     106    .045       0   143.4     .06       0
#XS Ineff= 2 , 0
                          190.35          707.91
Permanent Ineff=
       F       F
Bank Sta=106,143.4
XS Rating Curve= 0 ,0
Exp/Cntr=0.3,0.1

Type RM Length L Ch R = 1 ,28759.4 ,140.8,144.1,147.2
XS GIS Cut Line= 3
     1578292.292      383695.659     1578252.144      383656.596
     1578003.663       383561.11
#Sta/Elev= 25
       0  719.43     9.3  717.62      28  714.26    46.7  711.01   122.6  698.34
   132.1  696.53   141.6  694.74   151.1  693.57   160.6  693.36   170.1  694.06
   179.6  696.46   189.1  699.89   198.6  702.74   208.1   705.2   217.6  706.99
   227.1  707.88   236.6  708.07   246.2  707.86   255.7  707.13   265.2  705.71
   274.7  704.55   284.2  709.46   303.2  731.58   312.7   740.7   322.2  748.76
#Mann= 3 , 0 , 0
       0     .07       0   132.1    .045       0   179.6     .08       0
#XS Ineff= 2 , 0
                          236.23          707.98
Permanent Ineff=
       F       F
Bank Sta=132.1,179.6
XS Rating Curve= 0 ,0
Exp/Cntr=0.3,0.1

Type RM Length L Ch R = 1 ,28615.3 ,46,46,46
XS GIS Cut Line= 5
     1578319.419      383669.617     1578290.122      383578.471
     1578276.016      383542.664     1578247.804      383511.197
     1578044.896      383397.264
#Sta/Elev= 30
       0  722.15    47.9  715.14    57.4  714.03    86.2   711.1   105.4  709.62
     115  709.13   134.2  708.58   151.1  707.85   176.5  706.11   195.9  703.25
   205.6  701.35   215.3  698.07     225  694.49   234.7  693.91   244.4  694.75
     254     698   263.8  702.68   273.4  705.93   283.1  707.54   292.8  708.23
   321.9  708.52   331.6  708.38   341.3  707.66     351  706.22   360.7  705.47
   370.4  713.49   380.1  726.26   389.8  737.84   399.5  747.35   409.2  755.88
#Mann= 3 , 0 , 0
       0     .06       0   215.3    .045       0     254     .08       0
#XS Ineff= 2 , 0
                          309.57          708.57
Permanent Ineff=
       F       F
Bank Sta=215.3,254
XS Rating Curve= 0 ,0
Exp/Cntr=0.3,0.1

Type RM Length L Ch R = 1 ,28569.3 ,120.6,118.8,117.1
XS GIS Cut Line= 5
      1578347.63      383632.725     1578318.334      383541.579
     1578304.228      383505.771     1578276.016      383474.304
     1578073.108      383360.372
#Sta/Elev= 30
       0   723.9    28.7  718.12    38.3  716.46      67  712.33    76.6  711.51
    95.7  710.51   134.2  709.58   151.1  708.71   176.5  705.58   195.9  703.91
   205.6  702.37   215.3  699.56     221697.5209     225  696.09   234.7  694.38
   244.4  693.72     254  694.89   263.8  698.32   273.4  701.72   283.1  703.95
   302.5  706.81   321.9  708.57   341.3  709.15     351  708.71   360.7  707.42
   370.4  705.45   380.1  706.44   389.8  717.15   399.5  728.51   409.2  737.53
#Mann= 3 , 0 , 0
       0     .06       0     221    .045       0   263.8     .08       0
#XS Ineff= 2 , 0
                           341.9          709.52
Permanent Ineff=
       F       F
Bank Sta=221,263.8
XS Rating Curve= 0 ,0
Exp/Cntr=0.3,0.1

Type RM Length L Ch R = 1 ,28450.5 ,361.7,351.9,342.2
XS GIS Cut Line= 4
      1578415.99      383434.157     1578384.523      383390.754
     1578207.656      383308.289     1578113.699      383249.214
#Sta/Elev= 30
       0  720.12     8.9  717.19    17.9  714.99    26.8  713.24    44.7   710.2
    53.6  708.79    73.1  705.34    82.9  703.75   131.7  696.47   141.4  694.49
   151.2  693.66   160.9  693.44   170.7   693.9   180.4  695.97   190.2  698.51
     200  700.56   219.5  704.42   229.2  706.18     239   707.6   248.8  708.55
     258  708.91   285.8  709.67     295  709.56   304.2  708.65   313.5  706.71
   322.8  704.94     332  709.12   341.2  716.84   350.5  724.25   359.7  729.99
#Mann= 3 , 0 , 0
       0     .08       0   131.7    .045       0   180.4     .09       0
#XS Ineff= 2 , 0
                          276.35          710.15
Permanent Ineff=
       F       F
Bank Sta=131.7,180.4
XS Rating Curve= 0 ,0
Exp/Cntr=0.3,0.1