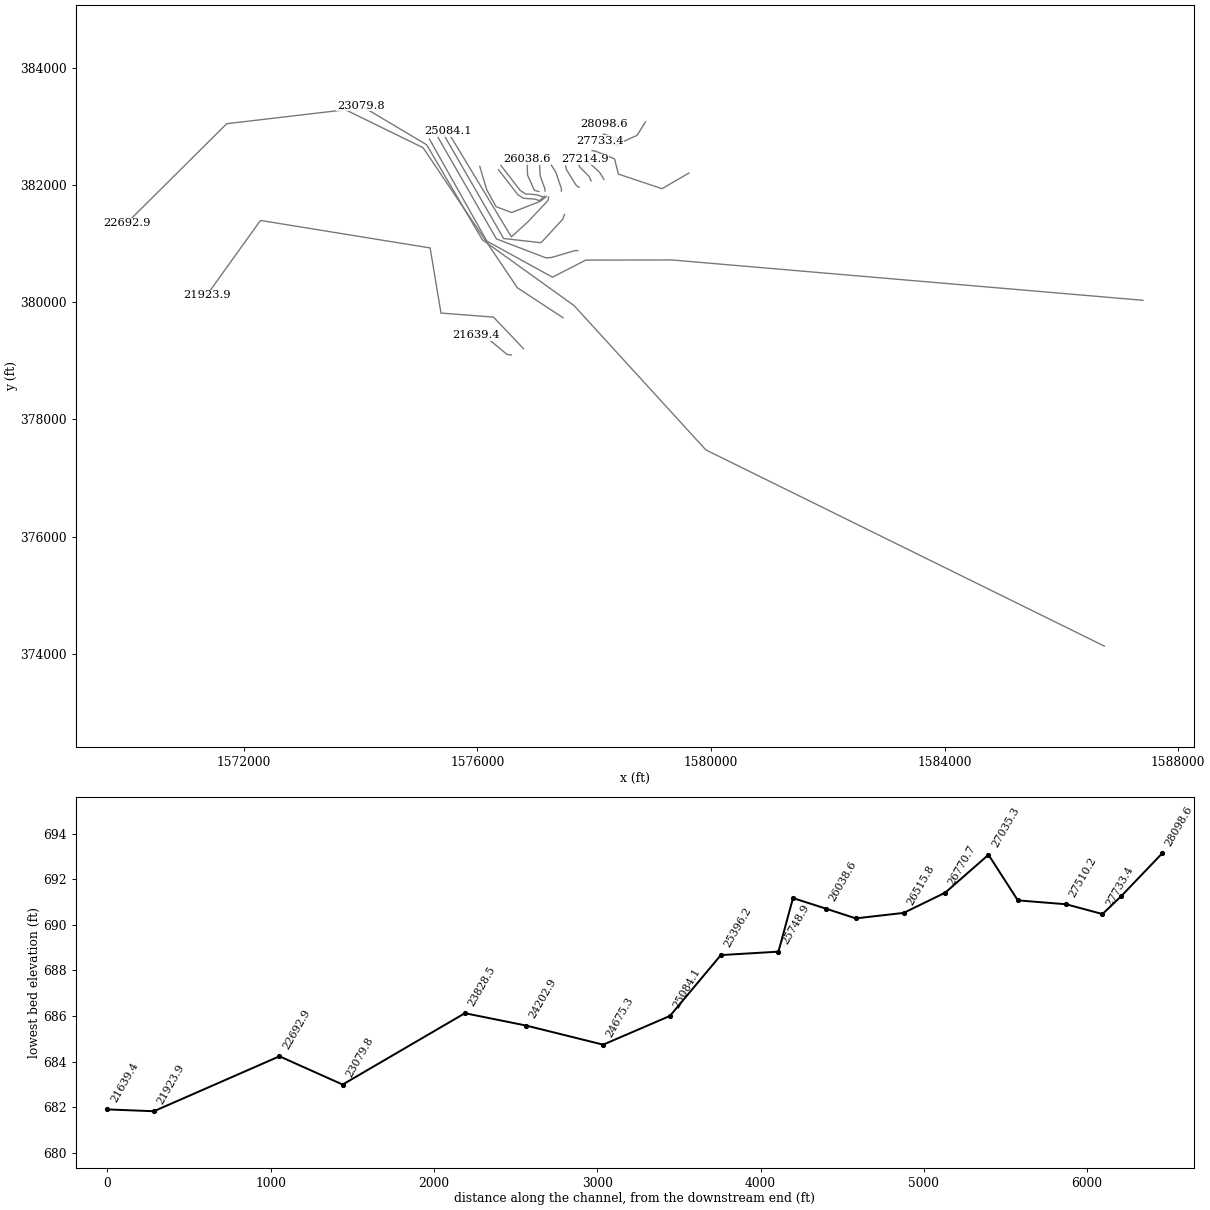
HEC-RAS study PTPLSCRK.prj: PTPLSCRK

--- PTPLSCRK.g01 (geometry) --- (continued)

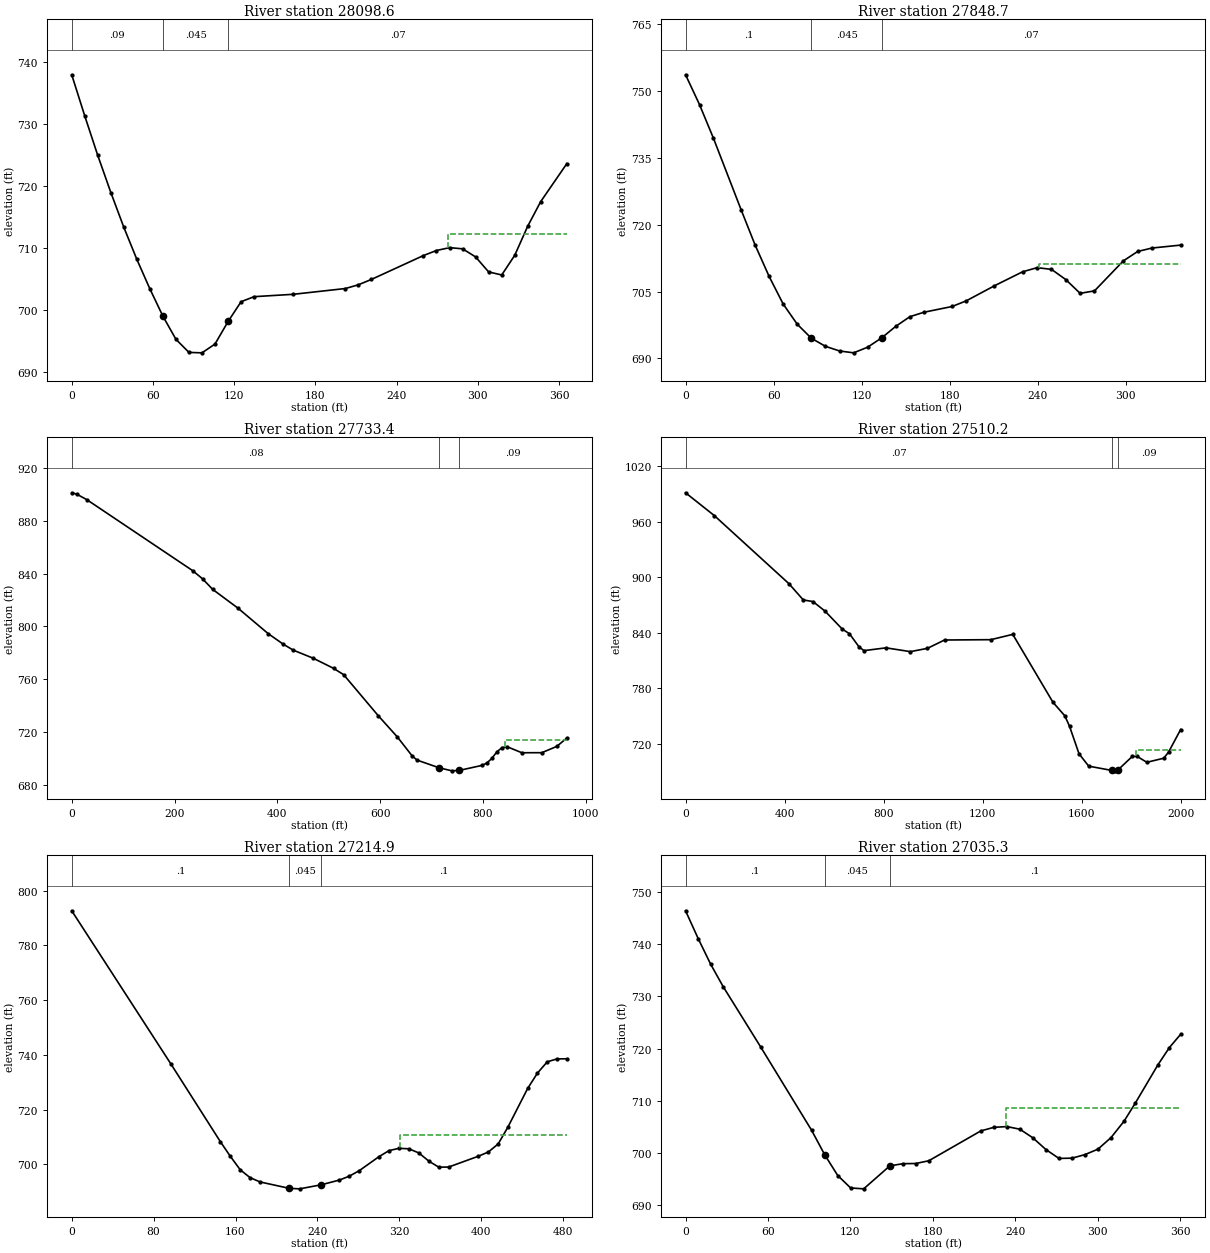
Type RM Length L Ch R = 1 ,28098.6 ,257.4,249.9,242.1
XS GIS Cut Line= 2
     1578526.667      383042.447     1578160.998      383040.277
#Sta/Elev= 30
       0  737.88     9.6  731.27    19.2  724.92    28.9  718.92    38.5  713.32
    48.1  708.17    57.7  703.44    67.4     699      77   695.3    86.6   693.2
    96.2  693.13   105.8  694.54   115.5  698.18   125.1  701.36   134.7  702.17
   163.6  702.55   202.1  703.48   211.7  704.08   221.3  704.94   259.8  708.79
   269.4   709.6   279.1  710.06   288.7  709.87   298.3  708.57   307.9  706.16
   317.6  705.66   327.2  708.82   336.8  713.51   346.4  717.47   365.7  723.58
#Mann= 3 , 0 , 0
       0     .09       0    67.4    .045       0   115.5     .07       0
#XS Ineff= 2 , 0
                          278.19          712.25
Permanent Ineff=
       F       F
Bank Sta=67.4,115.5
XS Rating Curve= 0 ,0
Exp/Cntr=0.3,0.1

Type RM Length L Ch R = 1 ,27848.7 ,113.9,115.4,116.8
XS GIS Cut Line= 4
     1578484.349      382789.626     1578427.926       382782.03
     1578273.846      382835.198     1578162.084      382871.006
#Sta/Elev= 30
       0  753.59     9.5  746.91      19  739.36      38   723.2    47.4  715.42
    56.9  708.41    66.5   702.2    76.1  697.67    85.7  694.53    95.3  692.72
   104.9  691.68   114.5  691.26     124  692.52   133.6  694.61   143.2   697.2
   152.8  699.36   162.4  700.36   181.6  701.65   191.2  702.91   210.3  706.27
   229.7  709.44   239.5  710.35   249.3  709.97     259  707.69   268.8   704.6
   278.6  705.15   298.2  711.86     308  713.98   317.7  714.75   337.3  715.41
#Mann= 3 , 0 , 0
       0      .1       0    85.7    .045       0   133.6     .07       0
#XS Ineff= 2 , 0
                          240.57          711.25
Permanent Ineff=
       F       F
Bank Sta=85.7,133.6
XS Rating Curve= 0 ,0
Exp/Cntr=0.3,0.1

Type RM Length L Ch R = 1 ,27733.4 ,225.5,223.2,220.7
XS GIS Cut Line= 5
     1578880.409      383080.811     1578734.676      382848.499
     1578466.454      382728.417     1578401.884      382674.608
     1578102.405      382758.159
#Sta/Elev= 30
       0  901.37     9.8  900.31    29.4  896.14   235.1  842.34   254.6  836.08
   274.2  828.09   323.2  813.92     382  794.58   411.4  786.54     431     782
   470.2  775.81   509.3  768.21   528.9  763.42   596.1  732.36   633.5  716.12
   661.9  701.95   671.6  698.63     715692.7388   739.6  690.47     754690.8041
   797.9  694.59   807.6   696.4   817.3  699.95   827.1  704.92   836.8  708.02
   846.5  708.83   875.6  704.19   914.5  704.24   943.6  709.02   963.1  715.35
#Mann= 3 , 0 , 0
       0     .08       0     715    .045       0     754     .09       0
#XS Ineff= 2 , 0
                          842.34           713.9
Permanent Ineff=
       F       F
Bank Sta=715,754
XS Rating Curve= 0 ,0
Exp/Cntr=0.3,0.1

Type RM Length L Ch R = 1 ,27510.2 ,303.5,295.3,287.2
XS GIS Cut Line= 6
     1579623.465      382205.811     1579161.659       381938.45
     1578415.131       382188.45     1578349.801      382447.829
     1578023.195      382579.122     1577965.686      382588.888
#Sta/Elev= 30
       0  991.32   116.4  966.61   417.2  893.13   475.4   875.5   514.2  873.81
   563.1  863.45     632  844.18   661.6  839.04   700.9  824.61   720.6  820.79
   809.2  823.79   907.6  819.68   976.5  823.25  1045.4  832.25  1232.3  832.61
  1320.9  838.34  1483.3  764.92  1531.1  750.34  1550.2  738.96  1588.4   709.3
  1627.5  695.97  1719.5   691.4    1735   690.9  1744.8  691.67  1803.5   706.5
    1823  706.48  1862.2  700.12  1930.6  704.56  1950.1  711.25  1998.7  735.56
#Mann= 3 , 0 , 0
       0     .07       0  1719.5    .045       0  1744.8     .09       0
#XS Ineff= 2 , 0
                         1817.54          713.39
Permanent Ineff=
       F       F
Bank Sta=1719.5,1744.8
XS Rating Curve= 0 ,0
Exp/Cntr=0.3,0.1

Type RM Length L Ch R = 1 ,27214.9 ,180.8,179.6,178.4
XS GIS Cut Line= 4
     1578168.603      382095.568     1578093.073       382219.53
     1577898.629      382394.877     1577837.865      382441.752
#Sta/Elev= 30
       0  792.68    96.8  736.75   145.2  708.31   154.9  702.98   164.6  698.04
   174.2  695.17     184  693.59   212.7  691.24   222.7  691.07     244692.5706
   261.5  694.28   271.2   695.7   280.9  697.71   300.3  702.86     310  705.04
   319.7  705.88   329.4   705.7   339.1  704.19   348.8  701.23   358.5     699
   368.2  699.03   397.3  702.99     407  704.53   416.6  707.46   426.2  713.68
   445.4  727.74     455  733.37   464.6   737.5   474.1  738.55   483.7  738.59
#Mann= 3 , 0 , 0
       0      .1       0   212.7    .045       0     244      .1       0
#XS Ineff= 2 , 0
                          321.08          710.61
Permanent Ineff=
       F       F
Bank Sta=212.7,244
XS Rating Curve= 0 ,0
Exp/Cntr=0.3,0.1

Type RM Length L Ch R = 1 ,27035.3 ,269.7,264.6,259.6
XS GIS Cut Line= 4
     1577948.976      382071.961     1577914.254      382146.613
     1577747.587      382315.016      1577737.17      382354.947
#Sta/Elev= 30
       0  746.45     9.2  741.11    18.3  736.18    27.4  731.88    54.9  720.22
    91.8   704.3   101.3  699.62   110.8  695.63   120.2  693.24   129.7  693.07
   148.7  697.47   158.2   697.9   167.6  697.93   177.1  698.46     215  704.19
   224.5  704.88     234  705.02   243.4  704.52   252.9  702.86   262.4  700.61
   271.9  698.91   281.4  698.96   290.8  699.64   300.3  700.69   309.8  702.91
   319.3  706.06   327.5  709.54     344   716.9   352.3  720.19   360.5  722.74
#Mann= 3 , 0 , 0
       0      .1       0   101.3    .045       0   148.7      .1       0
#XS Ineff= 2 , 0
                          233.13          708.52
Permanent Ineff=
       F       F
Bank Sta=101.3,148.7
XS Rating Curve= 0 ,0
Exp/Cntr=0.3,0.1

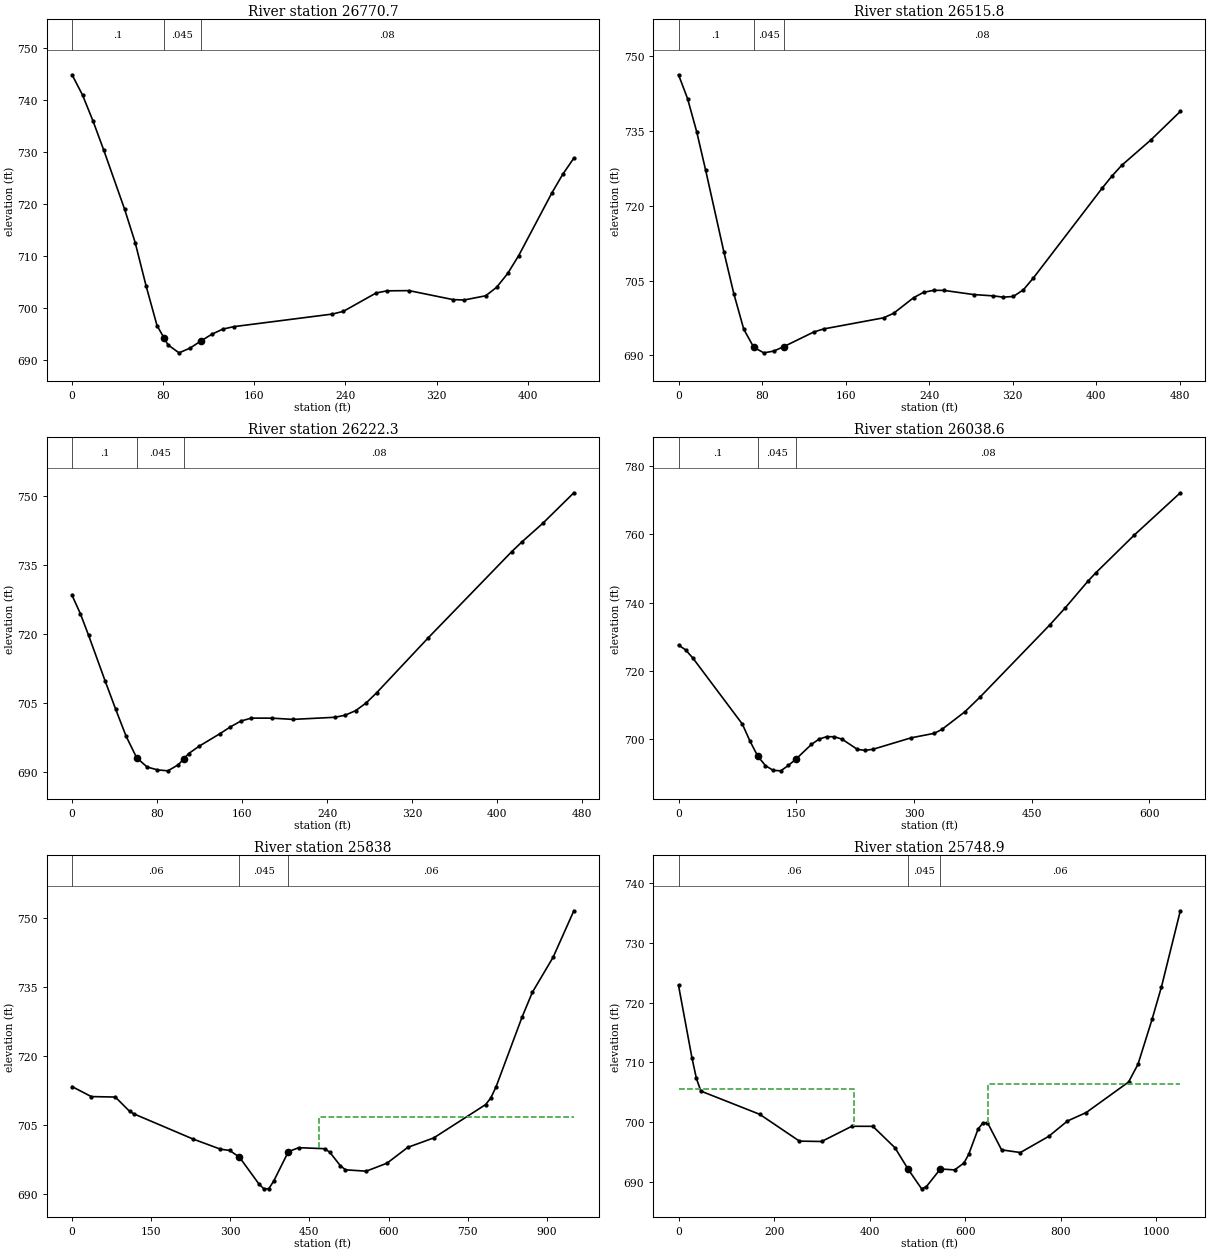
Type RM Length L Ch R = 1 ,26770.7 ,259.8,254.9,249.8
XS GIS Cut Line= 4
     1577742.379      381962.586     1577695.504        381992.1
     1577527.101      382261.197     1577511.476      382327.169
#Sta/Elev= 30
       0  744.82     9.2  740.92    18.5  735.88    27.7  730.42    46.2  718.95
    55.4   712.6      65  704.26    74.6  696.64    80.7   694.3    84.2  692.95
    93.9  691.41   103.5  692.31   113.1  693.68   122.7  694.98   132.4  695.97
     142  696.44   228.6  698.86   238.2  699.38     267  702.91   276.6  703.32
   295.9  703.36   334.4  701.64     344  701.55   363.2  702.37   372.8     704
   382.5  706.66   392.2   710.1   421.3  722.13     431  725.76   440.6  728.81
#Mann= 3 , 0 , 0
       0      .1       0    80.7    .045       0   113.1     .08       0
Bank Sta=80.7,113.1
XS Rating Curve= 0 ,0
Exp/Cntr=0.3,0.1

Type RM Length L Ch R = 1 ,26515.8 ,293.2,293.5,293.7
XS GIS Cut Line= 4
     1577439.599      381897.463     1577439.599      381940.866
     1577343.073      382221.266     1577267.735      382340.186
#Sta/Elev= 30
       0  746.23     8.7  741.42    17.4  734.82      26  727.09    43.4  710.78
      53  702.34    62.5  695.24    72.1  691.62    81.7  690.52    91.2  690.87
   100.8  691.76   129.5  694.69   139.1  695.31   196.5  697.54     206  698.44
   225.2  701.57   234.7  702.64   244.3  703.04   253.9  703.04   282.6   702.2
   301.7  701.93   311.2  701.67   320.8  701.82   330.4  703.16     340  705.54
   405.6  723.45     415  725.89   424.4  728.06   452.6   733.2   480.7  738.89
#Mann= 3 , 0 , 0
       0      .1       0    72.1    .045       0   100.8     .08       0
Bank Sta=72.1,100.8
XS Rating Curve= 0 ,0
Exp/Cntr=0.3,0.1

Type RM Length L Ch R = 1 ,26222.3 ,182,183.7,185.2
XS GIS Cut Line= 4
     1577157.309       381898.35     1577159.045        381929.6
     1577075.712      382160.502     1577065.478      382355.811
#Sta/Elev= 30
       0  728.39     7.8  724.41    15.6  719.68    31.3  709.69    41.1  703.63
    50.9  697.78    60.8  693.13    70.6  691.12    80.4  690.49    90.2  690.28
     100   691.6   105.4  692.94   109.8  694.04   119.7  695.64   139.3  698.36
   149.1  699.83     159   701.1   168.8  701.73   188.4  701.72     208  701.45
   247.3  701.91   257.1  702.36     267  703.36   276.8  705.01   286.6   707.2
   335.4  719.19   413.7  737.83   423.5  739.99     443     744   472.4  750.66
#Mann= 3 , 0 , 0
       0      .1       0    60.8    .045       0   105.4     .08       0
Bank Sta=60.8,105.4
XS Rating Curve= 0 ,0
Exp/Cntr=0.3,0.1

Type RM Length L Ch R = 1 ,26038.6 ,186.7,200.6,214.7
XS GIS Cut Line= 4
     1577054.541      381890.013     1576976.416      381912.582
     1576860.096      382171.263      1576849.68      382445.568
#Sta/Elev= 30
       0  727.59       9  726.17    18.1  723.82    81.3  704.42    91.1   699.4
   100.9  695.03   110.7  692.25   120.4  690.87   130.2  690.71     140   692.3
   149.8  694.19   169.3  698.45   179.1  700.02   188.9  700.74   198.7   700.7
   208.5  699.98     228  696.99   237.8  696.72   247.6  697.02   296.5   700.4
   325.8   701.7   335.6  702.85     365  708.05   384.6  712.43   472.8  733.43
   492.4   738.4   521.8  746.35   531.6  748.74   580.6  759.81   639.4  772.23
#Mann= 3 , 0 , 0
       0      .1       0   100.9    .045       0   149.8     .08       0
Bank Sta=100.9,149.8
XS Rating Curve= 0 ,0
Exp/Cntr=0.3,0.1

Type RM Length L Ch R = 1 ,25838   ,90.4,89.1,81.5
XS GIS Cut Line= 6
      1577121.43      381801.778     1577025.944       381832.16
     1576889.225      381847.351     1576828.461      381847.351
     1576735.145      381908.115     1576403.114      382335.633
#Sta/Elev= 30
       0  713.38    36.4  711.21      82  711.11   109.2  707.99   118.3   707.4
   228.7  702.02   281.4  699.78   298.8  699.51   317.3  698.05   354.4  692.21
   363.7  691.17     373   691.2   382.3  692.85   410.1  699.25   429.8  700.11
     479  699.89   488.8   699.1   508.5  696.22   518.4   695.3   557.7  695.01
   597.1  696.74   636.5  700.18   685.7  702.23   784.1  709.47   793.9  710.92
   803.8   713.3     853  728.42   872.7  733.86     912  741.46   951.4  751.57
#Mann= 3 , 0 , 0
       0     .06       0   317.3    .045       0   410.1     .06       0
#XS Ineff= 2 , 0
                          468.84           706.8
Permanent Ineff=
       F       F
Bank Sta=317.3,410.1
XS Rating Curve= 0 ,0
Exp/Cntr=0.3,0.1

Type RM Length L Ch R = 1 ,25748.9 ,332.4,352.7,380.2
XS GIS Cut Line= 6
     1577149.641      381810.459     1577067.119      381734.325
     1576984.711      381760.546     1576787.228      381775.737
     1576693.912      381836.501     1576361.881      382264.018
#Sta/Elev= 30
       0  722.88    28.1  710.75    37.4   707.3    46.8  705.19   169.9   701.3
     253  696.81   299.4  696.75   362.6   699.3   406.6  699.29     453  695.69
   480.8  692.06   508.7  688.82   518.5  689.18     548  692.15   577.6  691.99
   597.2  693.14   607.1  694.59   626.8  698.83   636.6  699.83   646.4  699.92
     676  695.35   715.3   694.9   774.4   697.6   813.8  700.18   853.1   701.6
   941.7  706.71   961.4  709.68   990.9  717.22  1010.6  722.67    1050  735.39
#Mann= 3 , 0 , 0
       0     .06       0   480.8    .045       0     548     .06       0
#XS Ineff= 2 , 0
          366.29   705.5  646.74           706.3
Permanent Ineff=
       F       F
Bank Sta=480.8,548
XS Rating Curve= 0 ,0
Exp/Cntr=0.3,0.1

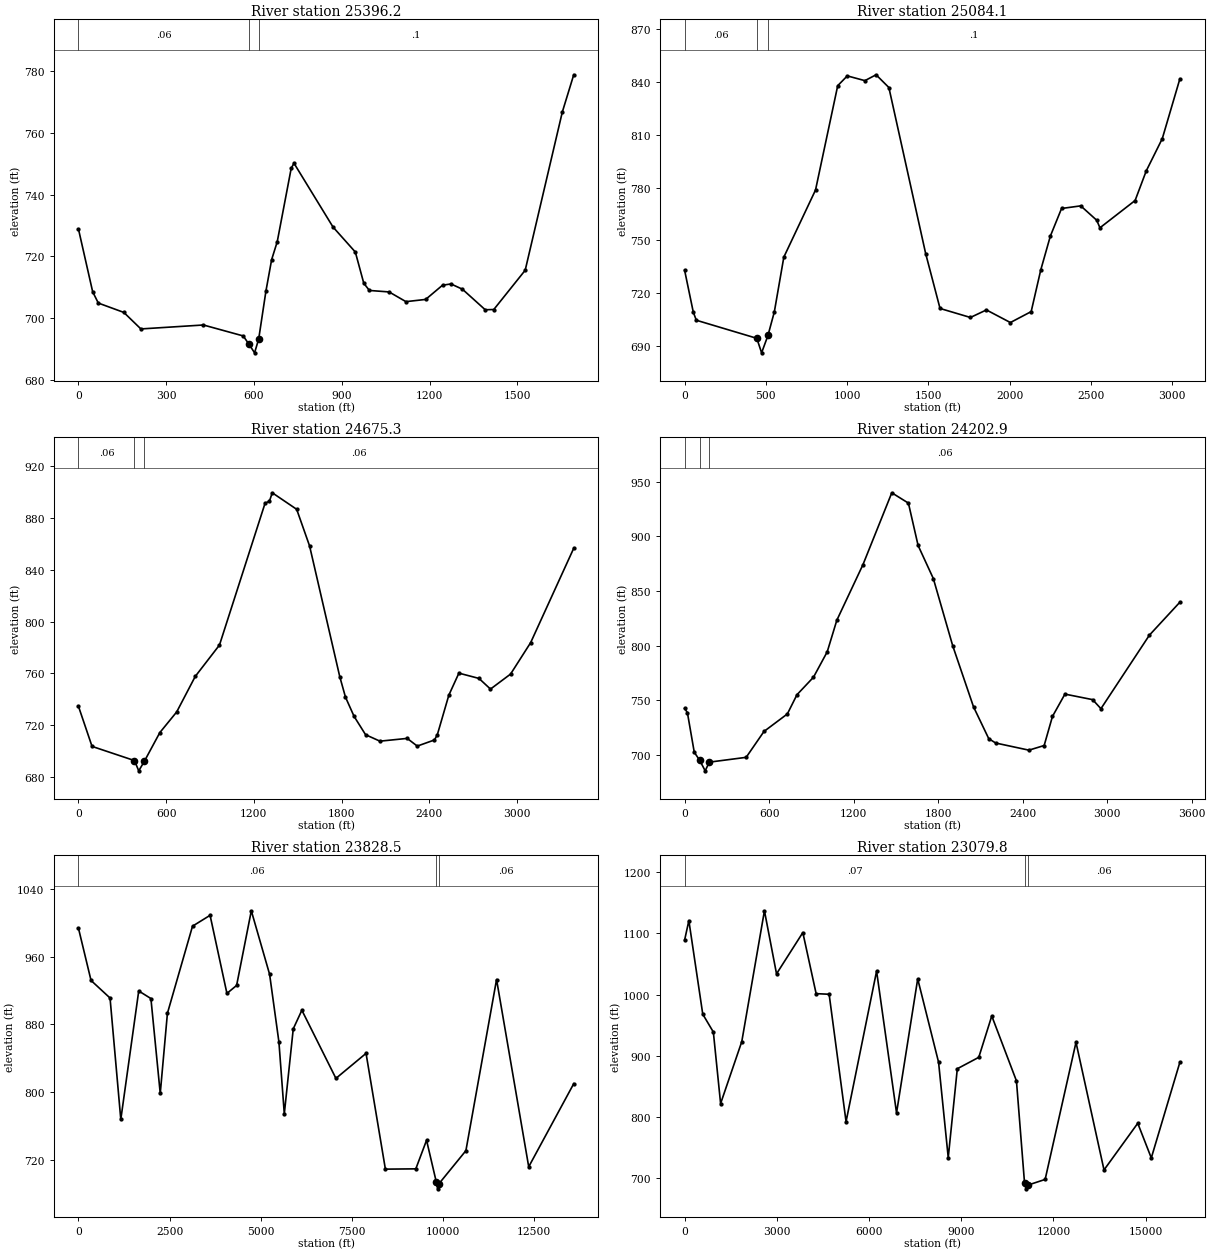
Type RM Length L Ch R = 1 ,25396.2 ,300.5,312,322.3
XS GIS Cut Line= 6
     1577184.364      381806.119     1577077.024      381723.545
     1576588.742      381531.488     1576321.019       381632.11
      1576162.31      381917.772     1576041.506       382319.61
#Sta/Elev= 30
       0  728.76    48.4  708.49    67.7  704.81   154.9  701.78   213.2  696.42
   426.9   697.7     563  694.15   582.4  691.49   601.8  688.67   615.9  693.19
   640.7  708.77   660.1   718.9   679.2   724.7   726.9  748.49   736.4  750.16
   869.9  729.46   946.1  721.36     975  711.23   994.2   708.9  1061.5  708.42
  1119.1  705.27  1186.4  705.99  1244.1   710.6  1272.9  711.01    1312  709.31
    1390  702.64  1419.3  702.72  1526.6  715.45  1653.5  766.77  1692.5  778.84
#Mann= 3 , 0 , 0
       0     .06       0   582.4    .045       0   615.9      .1       0
Bank Sta=582.4,615.9
XS Rating Curve= 0 ,0
Exp/Cntr=0.3,0.1

Type RM Length L Ch R = 1 ,25084.1 ,408.4,408.9,409.2
XS GIS Cut Line= 5
     1577221.256      381795.268     1577208.235      381734.504
     1576871.864      381378.601     1576583.183      381116.509
     1575492.089      382916.723
#Sta/Elev= 30
       0  732.93    53.3  709.15    71.9  704.55   444.1  694.26   473.5     686
   512.7   695.9   551.8  709.28   610.3  740.46   805.3  778.64   941.8     838
  1000.8  843.57    1109  840.86  1177.8   844.2  1256.5  836.96  1482.8  742.51
  1571.3  711.25  1758.2  706.12  1856.6  710.41  2004.1  703.24    2132  709.46
    2191  733.18    2250  752.43  2318.9  768.13  2436.9  769.62  2535.3  761.43
    2555  757.14  2771.4  772.67  2840.2  789.57  2938.6  807.88  3046.8  841.88
#Mann= 3 , 0 , 0
       0     .06       0   444.1    .045       0   512.7      .1       0
Bank Sta=444.1,512.7
XS Rating Curve= 0 ,0
Exp/Cntr=0.3,0.1

Type RM Length L Ch R = 1 ,24675.3 ,484.8,472.4,459.2
XS GIS Cut Line= 6
     1577492.523      381497.959     1577464.312      381419.834
     1577182.194      381113.844     1577090.209       381016.75
     1576450.417      381088.547     1575393.131      382916.723
#Sta/Elev= 30
       0  734.54    92.7  703.63   383.1  692.66   412.2  684.74   450.9  692.16
   556.6   714.3     672  730.27   798.8  757.68   964.7  781.96  1276.8   891.6
  1306.3  893.08  1325.9  899.63  1492.9  886.86  1581.3  858.51  1787.6   757.6
  1826.9  741.68  1885.8  726.82  1964.4  712.67  2062.6  707.67  2249.3  709.81
    2318  703.86  2435.9  708.61  2455.6  712.74  2534.1  743.23  2602.9  760.24
  2740.4  756.16    2819  747.92  2956.5  759.52    3094  783.84  3388.7  856.76
#Mann= 3 , 0 , 0
       0     .06       0   383.1    .045       0   450.9     .06       0
Bank Sta=383.1,450.9
XS Rating Curve= 0 ,0
Exp/Cntr=0.3,0.1

Type RM Length L Ch R = 1 ,24202.9 ,376.2,374.4,373.2
XS GIS Cut Line= 6
     1577720.388       380883.81     1577661.794      380879.469
     1577271.169      380764.452     1577173.856      380758.071
     1576326.139      381082.054     1575304.589      382854.223
#Sta/Elev= 30
       0  742.65    19.6  738.85    68.4   702.6   107.2  695.15     146  685.58
   175.1  693.53   436.9  697.93   563.5  721.62   729.4  737.63   797.7  755.22
   914.8  771.22  1012.4  794.45  1080.7  823.36  1266.1  874.17    1471  939.97
    1589  930.51  1657.8  891.74    1766  861.47  1903.7  799.95  2051.2  744.16
  2159.4  715.02  2208.6  711.03  2444.6   704.5  2552.8  708.74  2611.8  735.35
  2700.3  755.78    2897  750.72    2956  742.45  3300.2  809.72  3516.5  839.86
#Mann= 3 , 0 , 0
       0     .06       0   107.2    .045       0   175.1     .06       0
Bank Sta=107.2,175.1
XS Rating Curve= 0 ,0
Exp/Cntr=0.3,0.1

Type RM Length L Ch R = 1 ,23828.5 ,762.6,748.6,733.8
XS GIS Cut Line= 6
     1587397.669       380033.56     1579330.206      380722.299
     1577857.013      380720.001      1577286.36       380428.08
     1576162.806      381044.821     1575179.589      382786.515
#Sta/Elev= 30
       0  993.35   344.3  931.88   865.8  911.17  1160.9  767.92  1652.8   919.5
  1987.3  910.55  2243.1  798.63  2439.9  893.13  3128.5   995.9  3610.6 1008.72
    4073  916.61  4338.6  926.02    4742 1014.07  5243.7  939.18  5499.5  859.26
  5647.1  774.62  5893.1  874.87  6129.2  896.78  7063.8  816.39  7890.2   845.9
  8420.9  709.35  9255.7   709.7  9550.4  743.43    9815   694.7  9854.3  686.12
  9883.8   691.8 10629.9  731.14 11471.3  932.98 12353.5  712.12 13588.8  810.13
#Mann= 3 , 0 , 0
       0     .06       0    9815    .045       0  9883.8     .06       0
Bank Sta=9815,9883.8
XS Rating Curve= 0 ,0
Exp/Cntr=0.3,0.1

Type RM Length L Ch R = 1 ,23079.8 ,388.4,387,383.8
XS GIS Cut Line= 6
     1586737.947      374130.782     1579913.335       377479.89
     1577655.284      379944.573     1576086.334      381066.577
      1575132.29      382688.786      1574004.28       383357.46
#Sta/Elev= 30
       0 1089.23   137.7 1120.84   590.1  968.06   934.3  938.95  1170.3  822.18
  1858.7  923.22  2596.3 1136.89  2989.7 1033.95  3845.3 1101.33    4278 1001.62
  4700.9 1000.62  5251.6  792.67  6244.9 1038.38    6894  806.92  7582.4 1025.71
    8261  889.74  8575.7  733.96  8870.8  879.04  9569.1  897.67    9992  965.18
 10794.8  859.2211058.78691.8914 11104.6  682.99   11163689.0148 11728.2  698.35
 12732.1  922.14 13643.4  713.84 14741.2  790.02 15181.7  733.42 16111.3  889.56
#Mann= 3 , 0 , 0
       0     .07       011058.78    .045       0   11163     .06       0
Bank Sta=11058.78,11163
XS Rating Curve= 0 ,0
Exp/Cntr=0.3,0.1

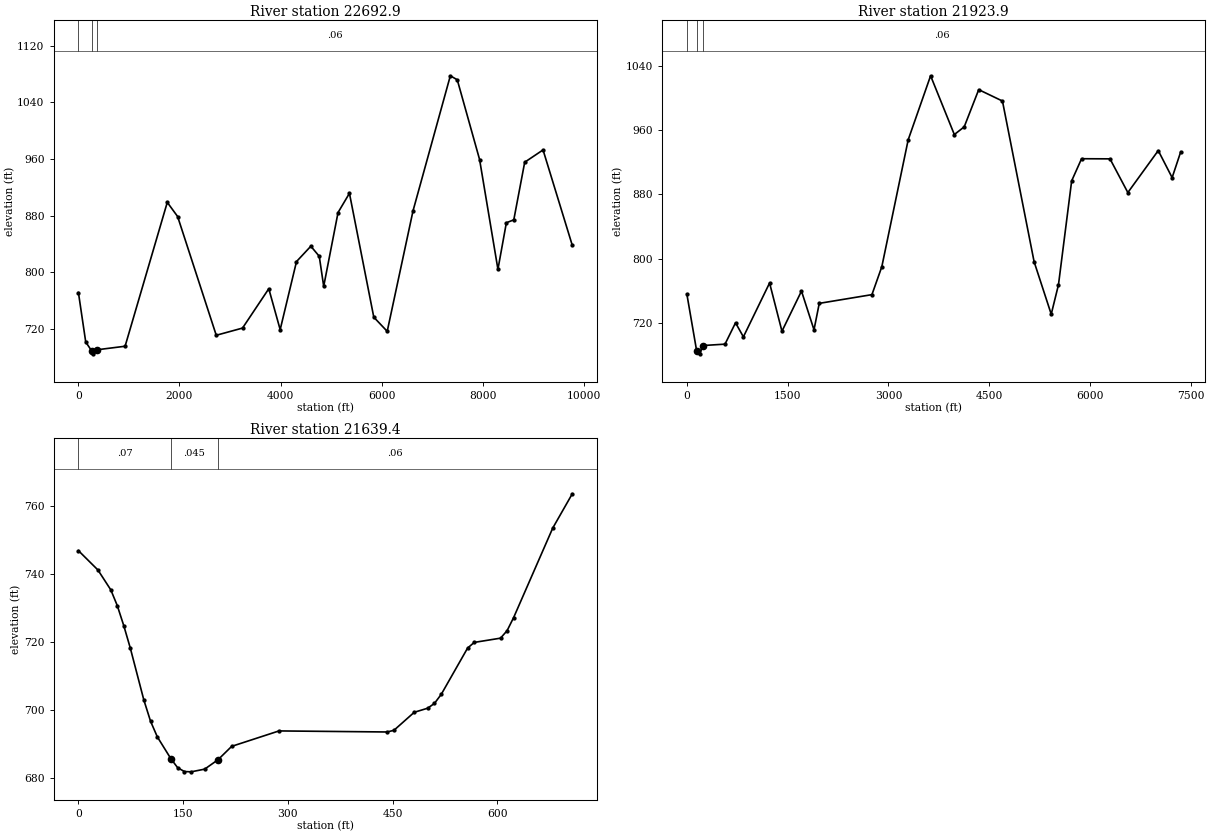
Type RM Length L Ch R = 1 ,22692.9 ,774.7,769,762.7
XS GIS Cut Line= 6
     1577467.784       379736.24     1576686.534      380246.657
     1575070.986      382638.012     1573742.042      383285.709
     1571709.568      383048.183     1569994.602      381349.388
#Sta/Elev= 30
       0  770.97   144.6  701.01   261.4  688.48   290.6  684.23   358.8   689.9
   923.7  694.98  1758.7  898.61  1963.4  878.57    2728  710.51    3248  720.69
  3767.9  776.38  3993.2  718.47  4316.3  814.81  4600.2  836.55  4766.7  822.29
  4854.8  779.81  5138.7  884.23  5364.2  911.41  5846.2   736.1  6111.8  716.06
  6623.4   886.8  7361.3 1077.74  7498.6 1072.04  7940.2  959.23  8303.3  803.85
  8470.1  869.73  8617.3  873.89  8833.2  955.41  9196.2  972.81  9775.2  837.76
#Mann= 3 , 0 , 0
       0     .06       0   261.4    .045       0   358.8     .06       0
Bank Sta=261.4,358.8
XS Rating Curve= 0 ,0
Exp/Cntr=0.3,0.1

Type RM Length L Ch R = 1 ,21923.9 ,281.9,284.5,288.5
XS GIS Cut Line= 6
       1576790.7      379208.462     1576276.812      379746.657
     1575377.506      379816.101     1575191.804      380927.441
     1572286.505      381396.836     1571366.918       380119.57
#Sta/Elev= 30
       0  756.24   146.9  685.04   195.8  681.82     235  692.14   567.9  693.86
   724.6  720.44   841.5  702.91  1231.2  769.93  1415.4  709.93    1706  759.86
  1892.2  711.71  1970.6   744.6  2754.4  755.44  2901.5  790.17  3293.8  947.96
  3627.4 1027.61  3980.6  954.53  4127.7   964.1  4343.5 1010.37  4696.7   996.2
  5167.6  796.41  5422.6  731.09  5530.5  767.79  5726.7  896.96  5874.1  924.46
  6297.1   924.3  6562.7   882.4  7015.2  934.59  7221.8  900.96  7349.6  933.05
#Mann= 3 , 0 , 0
       0     .08       0   146.9    .045       0     235     .06       0
Bank Sta=146.9,235
XS Rating Curve= 0 ,0
Exp/Cntr=0.3,0.1

Type RM Length L Ch R = 1 ,21639.4 ,125.9,128.9,129
XS GIS Cut Line= 5
     1576582.512      379100.968     1576508.727      379109.649
     1576165.845      379393.937      1576079.04      379430.829
     1575985.724       379435.17
#Sta/Elev= 30
       0  746.83    27.9  741.16    46.4  735.31    55.7  730.67      65  724.78
    74.3  718.24    93.7  702.99   103.3  696.76     113  692.17   132.4  685.76
   142.1  683.12   151.8  681.99   161.4   681.9   180.8  682.69     200685.4619
   219.5  689.38   287.3  693.91   442.2   693.6   451.9  694.09     481  699.38
   500.3  700.58     510     702   519.7  704.65   557.4  718.22   566.9  719.89
   604.6  721.14     614  723.34   623.4   727.2   679.4  753.46   707.4  763.52
#Mann= 3 , 0 , 0
       0     .07       0   132.4    .045       0     200     .06       0
Bank Sta=132.4,200
XS Rating Curve= 0 ,0
Exp/Cntr=0.3,0.1