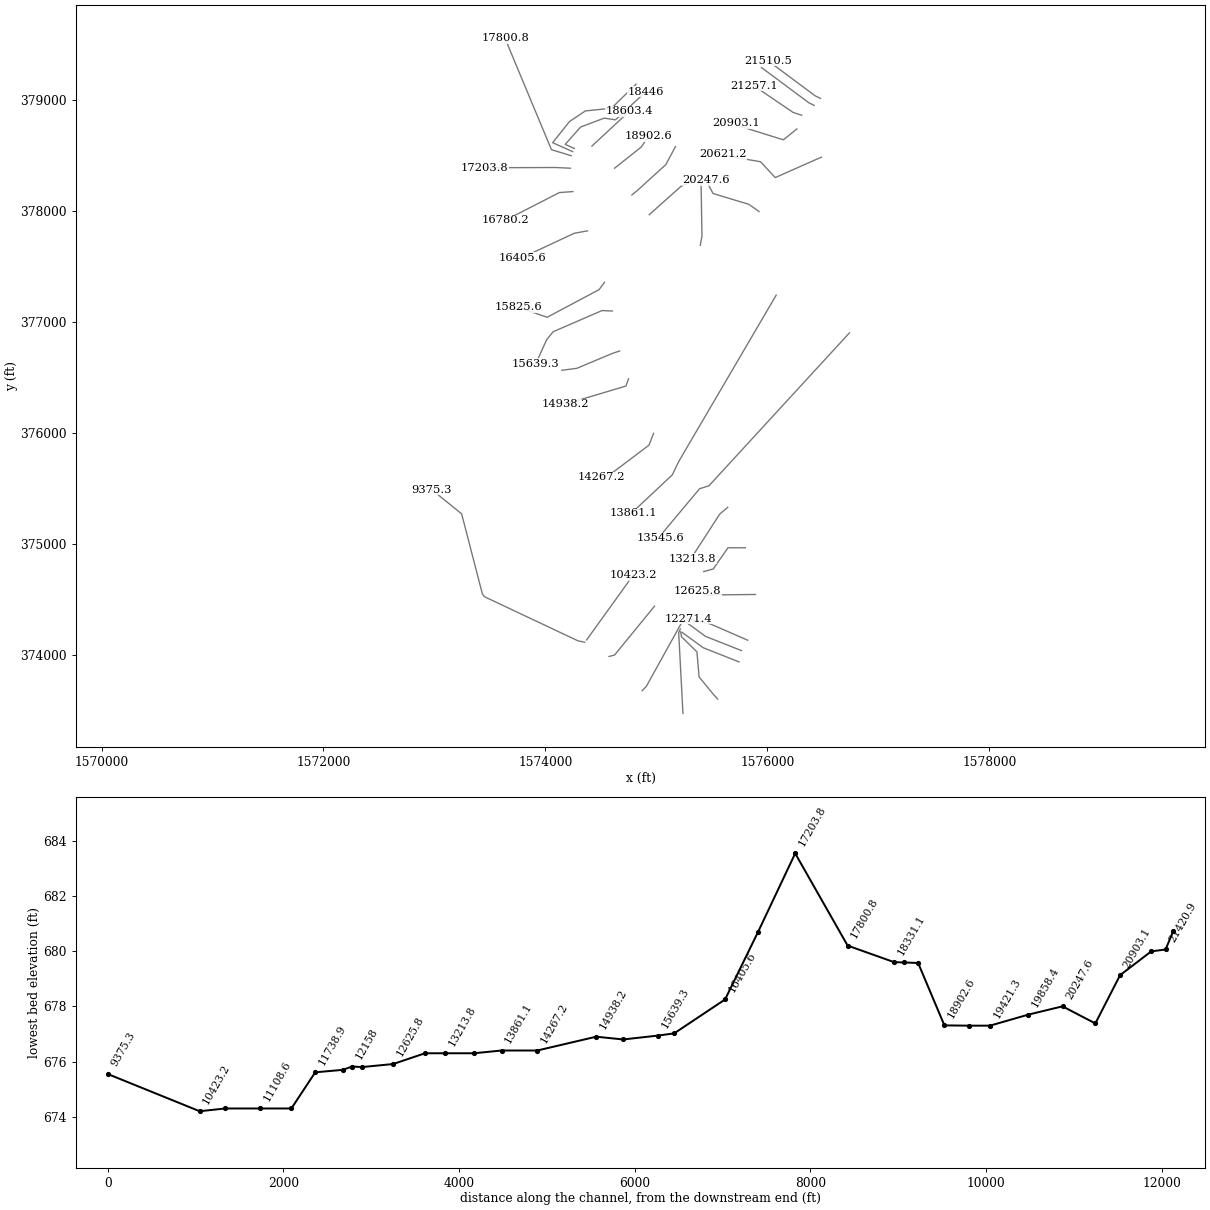
HEC-RAS study PTPLSCRK.prj: PTPLSCRK

--- PTPLSCRK.g01 (geometry) --- (continued)

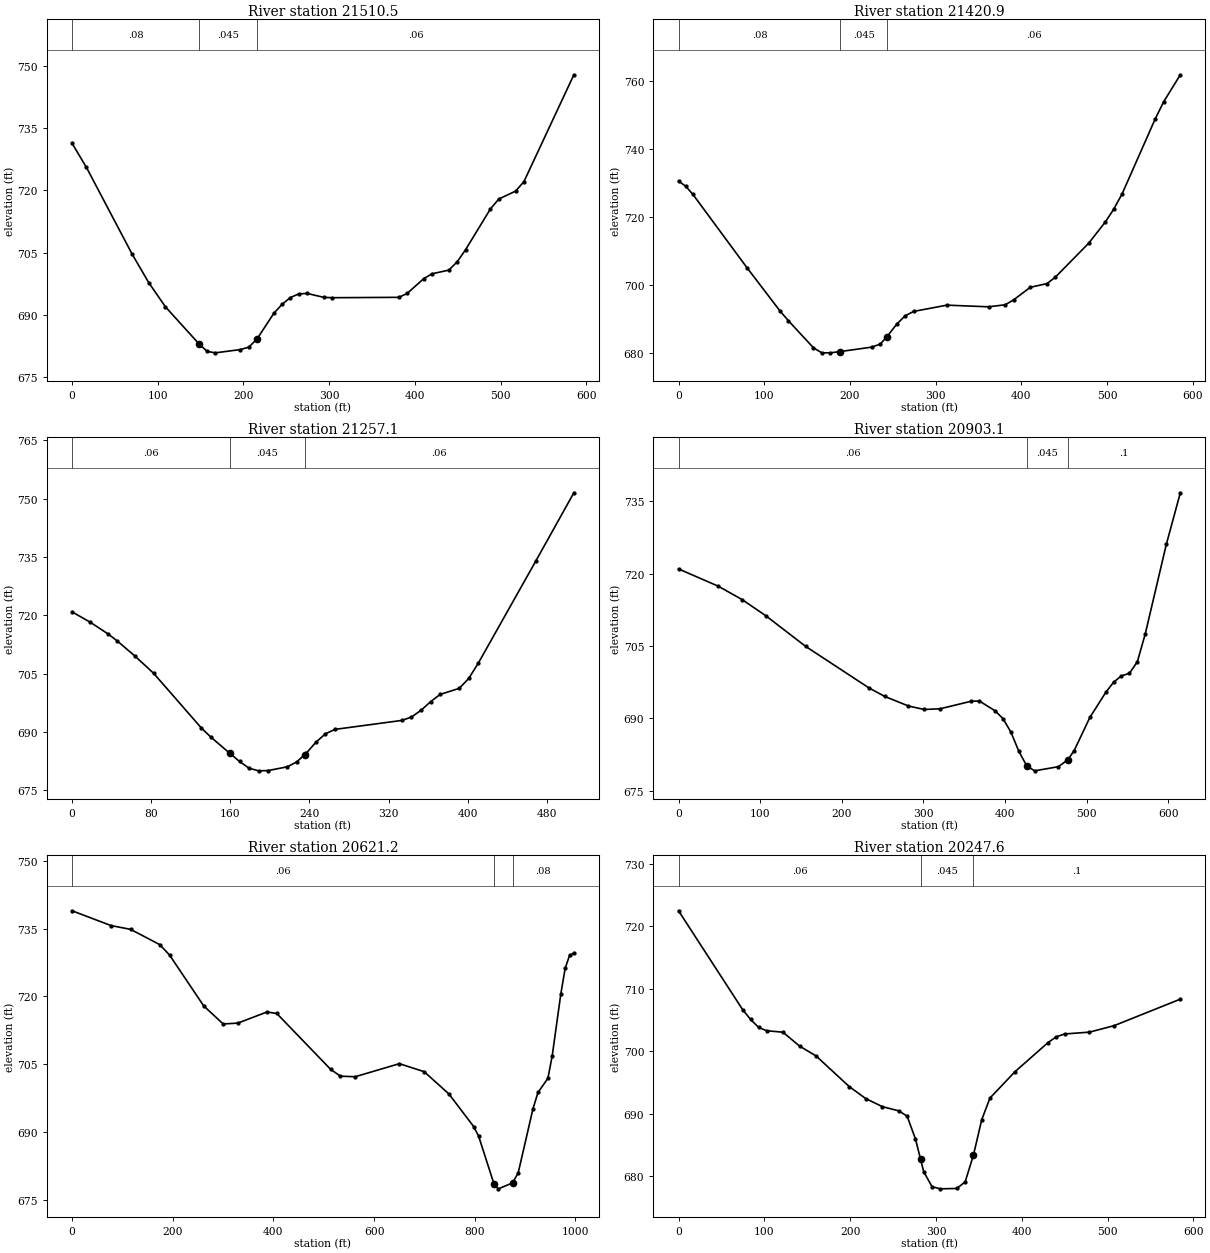
Type RM Length L Ch R = 1 ,21510.5 ,91.3,89.6,89.4
XS GIS Cut Line= 3
     1576478.345      379016.333     1576432.772      379038.034
     1576003.085      379357.045
#Sta/Elev= 30
       0   731.4    16.8  725.56    69.9  704.68    89.4  697.74   108.9  691.88
   147.8  682.98   157.5   681.1   167.2  680.74   196.4  681.53   206.2  682.12
   215.9   684.1   235.4  690.28   245.1  692.47   254.8  694.11   264.5  694.99
   274.3   695.1   293.7  694.16   303.5  694.07   381.3  694.16     391  695.09
   410.5   698.7   420.2  699.86   439.7  700.74   449.4  702.74   459.2  705.67
   488.3  715.56   498.1  717.94   517.5  719.83   527.3  722.12   585.6  747.97
#Mann= 3 , 0 , 0
       0     .08       0   147.8    .045       0   215.9     .06       0
Bank Sta=147.8,215.9
XS Rating Curve= 0 ,0
Exp/Cntr=0.3,0.1

Type RM Length L Ch R = 1 ,21420.9 ,162.9,163.8,164.6
XS GIS Cut Line= 3
     1576421.922      378953.399     1576376.349        378975.1
     1575946.661      379294.111
#Sta/Elev= 30
       0  730.68     8.4  729.14    16.8  726.73    79.7   705.2   118.6  692.34
   128.3   689.5   157.5  681.53   167.2  680.07     177  680.06     189680.4482
   225.6  681.75   235.4  682.64     243684.7476   254.8  688.57   264.5  690.97
   274.3  692.26   313.2  694.11   361.8  693.62   381.3  694.22     391  695.66
   410.5  699.37     430  700.46   439.7  702.35   478.6  712.34   498.1  718.62
   507.8  722.36   517.5  726.81   556.4  749.04   566.2  754.05   585.6  761.98
#Mann= 3 , 0 , 0
       0     .08       0     189    .045       0     243     .06       0
Bank Sta=189,243
XS Rating Curve= 0 ,0
Exp/Cntr=0.3,0.1

Type RM Length L Ch R = 1 ,21257.1 ,346.7,354,361.1
XS GIS Cut Line= 3
     1576309.074      378864.423     1576230.949      378890.465
     1575879.387       379129.18
#Sta/Elev= 30
       0  720.87    18.3  718.22    36.6  715.16    45.8  713.37      64  709.41
    82.4  705.09   130.6  691.04   140.3  688.67   159.6  684.47   169.3   682.4
   178.9  680.67   188.6  679.99   198.2  680.06   217.6  681.03   227.2   682.3
     235684.1173   236.9  684.56   246.5  687.34   256.2  689.52   265.8  690.65
   333.5  692.96   343.1  693.83   352.8  695.55   362.4  697.76   372.1  699.64
   391.4   701.2   401.1  703.78   410.7  707.69   468.7  733.89   507.3   751.5
#Mann= 3 , 0 , 0
       0     .06       0   159.6    .045       0     235     .06       0
Bank Sta=159.6,235
XS Rating Curve= 0 ,0
Exp/Cntr=0.3,0.1

Type RM Length L Ch R = 1 ,20903.1 ,279.4,281.9,284.2
XS GIS Cut Line= 4
     1576265.672      378740.725     1576144.144      378643.069
     1575747.008      378766.767     1575714.456      378794.979
#Sta/Elev= 30
       0  720.95    48.7  717.37      78  714.59   107.2  711.22   155.9  704.89
   233.3  696.31   252.6  694.55   281.7  692.56     301  691.84   320.4  691.98
     359  693.56   368.7  693.58   388.1  691.54   397.7  689.92   407.4  687.11
   417.1  683.14   426.8  680.14   436.4  679.13   465.4  679.99     477681.4062
   484.8  683.32   504.1   690.2   523.5  695.37   533.2   697.5   542.8  698.81
   552.5  699.32   562.2  701.71   571.9  707.47   597.7  726.01   614.9  736.72
#Mann= 3 , 0 , 0
       0     .06       0   426.8    .045       0     477      .1       0
Bank Sta=426.8,477
XS Rating Curve= 0 ,0
Exp/Cntr=0.3,0.1

Type RM Length L Ch R = 1 ,20621.2 ,376.5,373.6,370.8
XS GIS Cut Line= 5
     1576487.026      378486.819     1576070.769      378302.738
     1575937.981      378445.586     1575647.182      378495.499
     1575599.439      378515.031
#Sta/Elev= 30
       0  738.94    77.5  735.66   116.2  734.83   174.3  731.44   193.7  729.13
   261.5  717.88   300.2  713.88   329.2  714.07   387.4  716.54   406.7   716.2
   513.6  703.84   533.2  702.32   562.4   702.2   650.2  705.09   699.4  703.32
   748.5   698.4   797.7  691.18   807.5  689.08     838678.5128   846.9  677.38
     875   678.7   886.2   680.9   915.7  695.16   925.6  698.73   945.2  701.84
   953.8  706.83     971  720.61   979.6  726.23   988.2  729.04   996.8   729.6
#Mann= 3 , 0 , 0
       0     .06       0     838    .045       0     875     .08       0
Bank Sta=838,875
XS Rating Curve= 0 ,0
Exp/Cntr=0.3,0.1

Type RM Length L Ch R = 1 ,20247.6 ,417.7,389.2,360.5
XS GIS Cut Line= 4
      1575924.96      377996.367     1575833.814      378061.472
     1575510.463      378159.128     1575447.529      378278.486
#Sta/Elev= 30
       0  722.49    74.7  706.67      84   705.1    93.3  703.83   102.7   703.3
   121.7  703.06     141  700.84   160.3  699.26   198.9  694.36   218.2  692.44
   237.5  691.15   256.8  690.47   266.4  689.62   276.1  685.96     282682.7519
   285.7  680.74   295.4  678.34     305     678   324.3  678.06     334  679.12
   343.6  683.38   353.3  689.06   362.9  692.53   391.9  696.72   430.5   701.4
   440.1  702.32   449.8  702.78   478.7  703.07   507.6  704.11   584.7  708.35
#Mann= 3 , 0 , 0
       0     .06       0     282    .045       0   343.6      .1       0
Bank Sta=282,343.6
XS Rating Curve= 0 ,0
Exp/Cntr=0.3,0.1

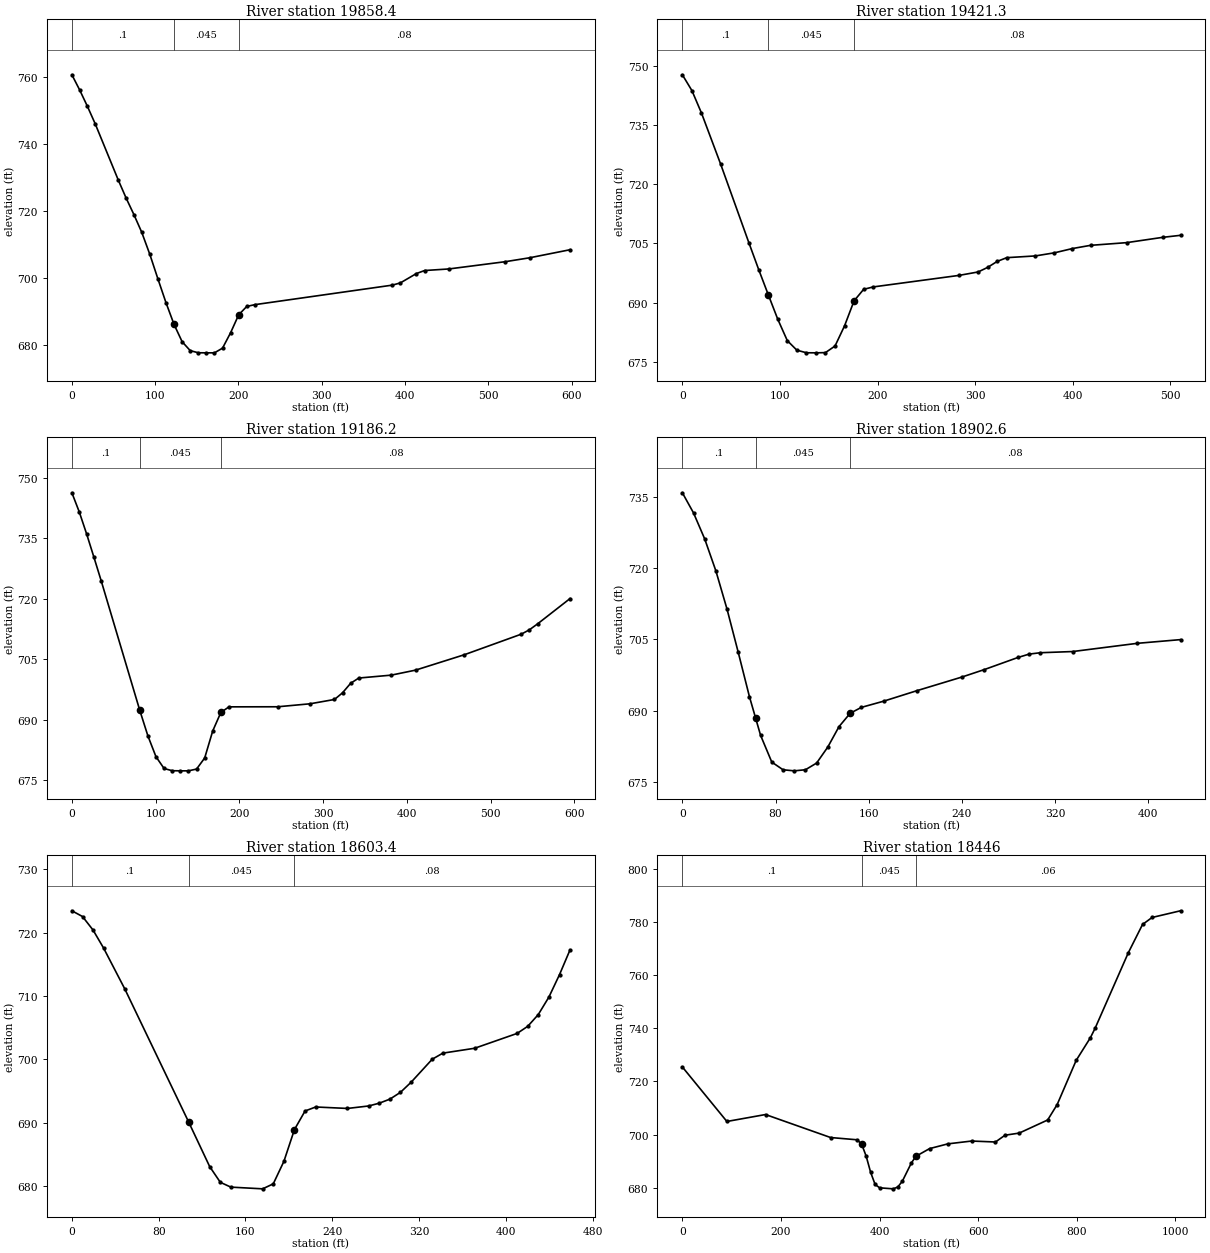
Type RM Length L Ch R = 1 ,19858.4 ,456.5,437.2,417.7
XS GIS Cut Line= 3
     1575395.446      377692.548     1575410.637      377775.013
     1575401.956      378289.336
#Sta/Elev= 30
       0  760.63     9.3  756.12    18.6  751.24      28  746.01    55.9  729.12
    65.2  723.82    74.5  718.92    83.8   713.7    93.6  707.07   103.3  699.76
     113  692.66   122.7  686.16   132.4  681.01   142.1  678.36   151.8  677.72
   161.5   677.7   171.2   677.7   180.9   679.1   190.6   683.7   200.3  689.04
     210  691.54   219.7  692.07   384.7  697.89   394.4  698.55   413.8  701.36
   423.6  702.25   452.7  702.72   520.6  704.89   549.7  706.05   598.2  708.45
#Mann= 3 , 0 , 0
       0      .1       0   122.7    .045       0   200.3     .08       0
Bank Sta=122.7,200.3
XS Rating Curve= 0 ,0
Exp/Cntr=0.3,0.1

Type RM Length L Ch R = 1 ,19421.3 ,235,235,235.3
XS GIS Cut Line= 3
     1574935.376      377968.156     1575219.665      378222.062
     1575336.852      378276.315
#Sta/Elev= 30
       0  747.71     9.8   743.7    19.6  738.01    39.1  725.17    68.4     705
    78.2  698.38      88  692.02    97.7  685.83   107.5  680.39   117.3  677.97
   127.1  677.32   136.8   677.3   146.6  677.36   156.4  679.03   166.2  684.17
   175.9  690.47   185.7  693.38   195.5  693.99   283.4  696.91     303  697.78
   312.8  698.95   322.5  700.45   332.3   701.4   361.6  701.84   381.2  702.63
   399.6  703.71   418.1  704.52     455   705.2   491.9  706.54   510.3  707.06
#Mann= 3 , 0 , 0
       0      .1       0      88    .045       0   175.9     .08       0
Bank Sta=88,175.9
XS Rating Curve= 0 ,0
Exp/Cntr=0.3,0.1

Type RM Length L Ch R = 1 ,19186.2 ,285.1,283.6,281.8
XS GIS Cut Line= 4
     1574779.126      378146.107     1574826.869       378185.17
     1575085.116      378419.545     1575171.922      378582.305
#Sta/Elev= 30
       0  746.22     8.8  741.48    17.6  736.02    26.4  730.19    35.2  724.26
    81.1  692.28    90.8  685.95   100.4  680.81   110.1  677.88   119.8  677.33
   129.5   677.3   139.2   677.3   148.9  677.74   158.6  680.49   168.2  687.19
   177.9  691.77   187.6  693.16   245.8  693.18   284.5  693.92   313.6  694.99
   323.2  696.64   332.9     699   342.6   700.3   381.4  701.02   410.4  702.26
   468.7  706.08   536.6  711.17   546.4  712.26   556.1  713.72   594.9     720
#Mann= 3 , 0 , 0
       0      .1       0    81.1    .045       0   177.9     .08       0
Bank Sta=81.1,177.9
XS Rating Curve= 0 ,0
Exp/Cntr=0.3,0.1

Type RM Length L Ch R = 1 ,18902.6 ,297.5,299.2,301
XS GIS Cut Line= 3
     1574622.876      378386.992     1574863.762      378577.965
     1574931.036      378677.791
#Sta/Elev= 28
       0  735.86     9.6  731.61    19.2  726.13    28.8   719.4    38.4  711.32
      48  702.25    57.6  692.93   62.89688.4335    67.2  684.77    76.8  679.15
    86.5  677.53    96.1  677.31   105.7  677.54   115.3  678.95   124.9  682.32
   134.5  686.61   144.1  689.43   153.7  690.67   172.9  691.98   201.7  694.21
   240.2  697.07   259.4  698.64   288.2  701.18   297.8  701.89   307.4  702.18
   335.2  702.43   390.7  704.16   427.8  704.94
#Mann= 3 , 0 , 0
       0      .1       0   62.89    .045       0   144.1     .08       0
Bank Sta=62.89,144.1
XS Rating Curve= 0 ,0
Exp/Cntr=0.3,0.1

Type RM Length L Ch R = 1 ,18603.4 ,168.3,157.4,146.4
XS GIS Cut Line= 2
     1574418.883      378586.645     1574755.255      378899.145
#Sta/Elev= 30
       0  723.46     9.8  722.55    19.5  720.42    29.3  717.55    48.8  711.11
   107.5  690.16     127  683.08   136.8   680.6   146.5  679.84   175.8  679.57
   185.6  680.36   195.4  683.91   205.1  688.92   214.9  691.86   224.7  692.49
     254  692.26   273.5  692.65   283.3  693.09   293.1  693.73   302.8   694.8
   312.6  696.39   332.1  700.03   341.9  700.99   371.2  701.76   410.3   704.1
   420.1  705.22   429.8  707.07   439.6  709.83   449.4  713.38   459.1  717.29
#Mann= 3 , 0 , 0
       0      .1       0   107.5    .045       0   205.1     .08       0
Bank Sta=107.5,205.1
XS Rating Curve= 0 ,0
Exp/Cntr=0.3,0.1

Type RM Length L Ch R = 1 ,18446   ,111.5,115,115.2
XS GIS Cut Line= 6
     1574260.463      378564.944     1574177.998      378601.836
     1574316.887      378758.086      1574529.56      378838.381
     1574631.557       378823.19     1574906.658       379078.29
#Sta/Elev= 30
       0  725.43    90.3  704.93   168.6  707.54   300.6  698.89   354.8  698.03
   363.8   696.3   372.8  691.85   381.8   685.8   390.9  681.23   400.1  679.97
   427.7  679.59   436.9  680.29   446.1  682.46   464.5  689.36   473.7  691.84
   501.3  694.72   538.5  696.51   586.6  697.57     635  697.21   654.3  699.76
   683.1  700.56   740.8  705.49   760.1   711.3   798.6   727.9   827.4  736.41
     837  739.99   904.4  768.41   933.2  779.03   952.5  781.66  1010.2  784.18
#Mann= 3 , 0 , 0
       0      .1       0   363.8    .045       0   473.7     .06       0
Bank Sta=363.8,473.7
XS Rating Curve= 0 ,0
Exp/Cntr=0.3,0.1

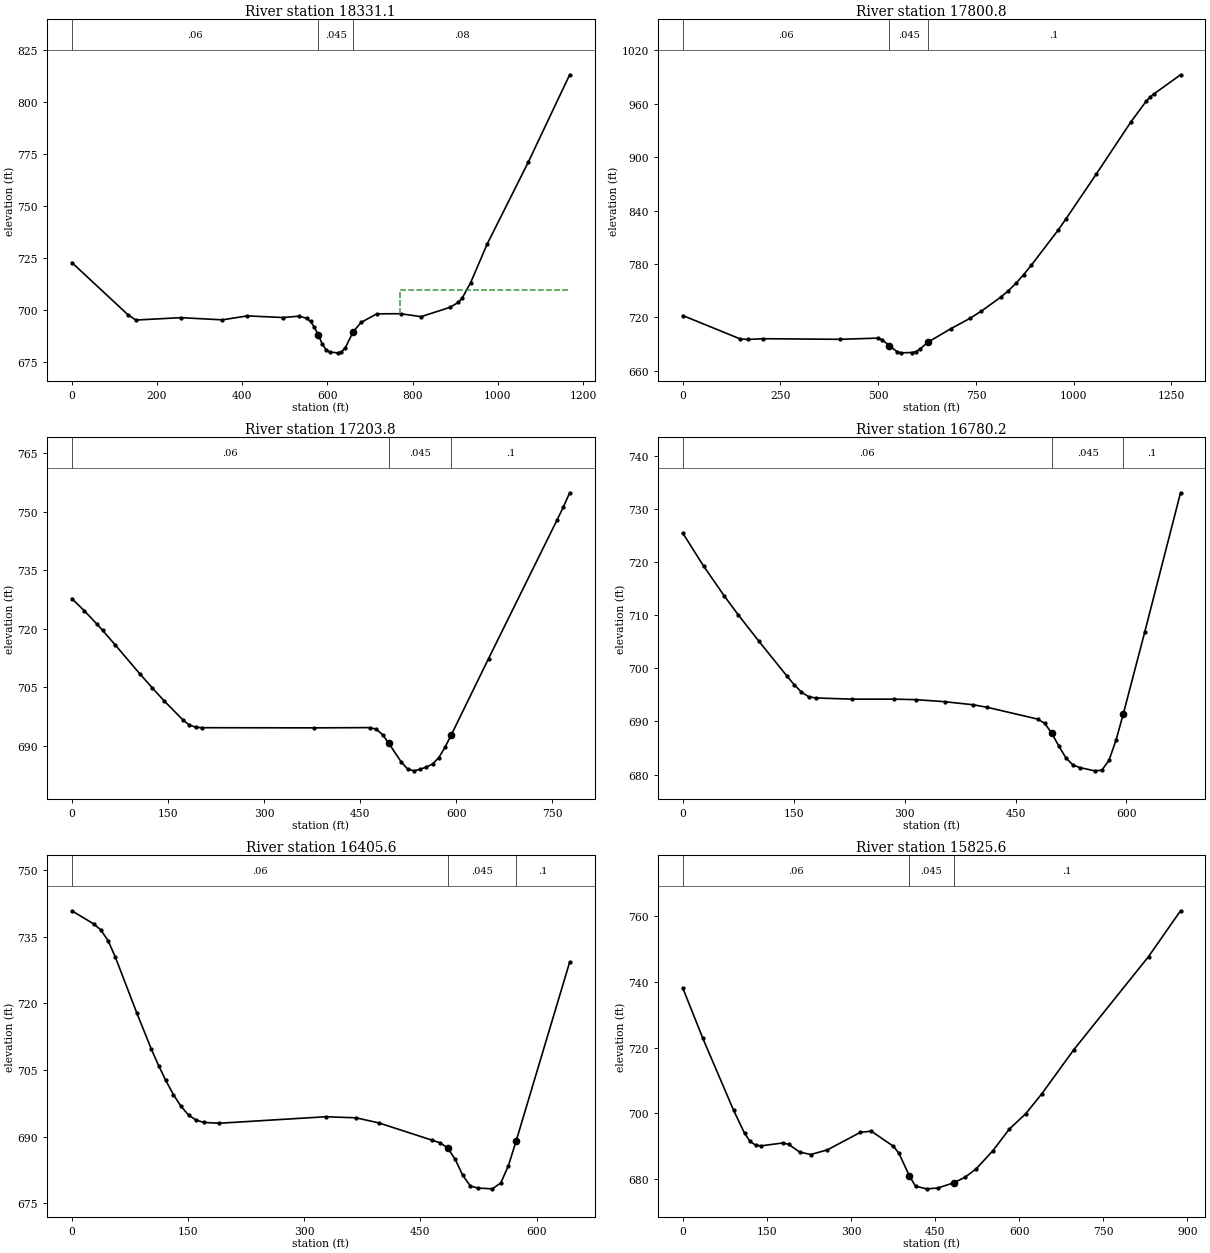
Type RM Length L Ch R = 1 ,18331.1 ,494.9,530.2,568.4
XS GIS Cut Line= 6
     1574245.272      378536.732     1574065.151      378617.027
      1574217.06      378807.999      1574360.29      378903.486
     1574594.665      378927.357      1574816.38      379144.262
#Sta/Elev= 30
       0  722.97   131.5  697.94   150.2  695.36   255.8   696.5   353.4  695.45
     412  697.35   496.6  696.56   533.4  697.23   551.4   696.2   560.4  694.66
   569.4  691.97   578.5  688.21   587.5  684.07   596.5  681.14   605.6  679.99
   623.8   679.6     633  680.04   642.2  682.07   660.6  689.72     679  694.19
   715.8  698.33   771.8   698.4   819.9  696.98   887.8  701.45   907.2   703.8
   916.9  706.04   936.3  713.27     975  731.78    1072  771.33  1168.9  813.19
#Mann= 3 , 0 , 0
       0     .06       0   578.5    .045       0   660.6     .08       0
#XS Ineff= 2 , 0
                          771.67          709.87
Permanent Ineff=
       F       F
Bank Sta=578.5,660.6
XS Rating Curve= 0 ,0
Exp/Cntr=0.3,0.1

Type RM Length L Ch R = 1 ,17800.8 ,570.2,597.1,623.6
XS GIS Cut Line= 3
     1574232.251       378499.84       1574054.3      378554.093
     1573635.825      379557.457
#Sta/Elev= 30
       0  722.14   146.9  695.85   166.5   695.2   205.6  696.08   401.5  695.38
   499.4  696.76   509.2  695.11   528.8  688.22   548.4  681.43   558.2   680.2
   587.6  680.57   597.4   681.7   607.2  684.58   626.8  692.08   685.5  707.27
   734.5   718.9   763.9   727.1   812.8  742.59   832.4  749.77     852  758.21
   871.6  767.94   891.2  778.41   959.8  817.93   979.4  830.23  1057.7  881.06
  1145.8  939.35    1185  962.76  1194.8  967.35  1204.6  970.93  1273.2  992.65
#Mann= 3 , 0 , 0
       0     .06       0   528.8    .045       0   626.8      .1       0
Bank Sta=528.8,626.8
XS Rating Curve= 0 ,0
Exp/Cntr=0.3,0.1

Type RM Length L Ch R = 1 ,17203.8 ,413,423.6,434.2
XS GIS Cut Line= 3
     1574225.741      378386.992     1574091.192      378393.503
     1573448.831      378391.333
#Sta/Elev= 30
       0   727.7    19.2  724.61    38.5  721.27    48.1  719.53    67.4  715.88
   105.8  708.46   125.1  704.89   144.4  701.42   173.6  696.55   183.4   695.3
   193.1  694.72   202.8   694.6     378  694.56   465.6  694.62   475.4  694.19
   485.1   692.8   494.8   690.6   514.3  685.78     524  684.05   533.8  683.54
   543.5  683.92   553.2  684.51     563  685.29   572.7   686.9   582.4  689.54
   592.2  692.72   650.5  712.32   757.6   747.9   767.3  751.18   777.1  754.82
#Mann= 3 , 0 , 0
       0     .06       0   494.8    .045       0   592.2      .1       0
Bank Sta=494.8,592.2
XS Rating Curve= 0 ,0
Exp/Cntr=0.3,0.1

Type RM Length L Ch R = 1 ,16780.2 ,375.4,374.6,373.7
XS GIS Cut Line= 3
     1574247.442      378176.489     1574125.915      378167.808
     1573635.463      377916.072
#Sta/Elev= 30
       0  725.49    28.1   719.3    56.2  713.63      75  710.09   103.1  705.09
   141.2  698.49   150.8  696.91   160.5  695.53   170.2  694.66   179.9  694.42
   228.2   694.2   286.3   694.2   315.3   694.1     354  693.72   392.6  693.14
     412  692.65   479.7  690.45   489.4  689.64     499  687.78   508.7  685.31
   518.4  683.08     528  681.76   537.7  681.28   557.1  680.69   566.7  680.81
   576.4  682.68   586.1  686.57   595.8  691.46   624.8  706.89   673.1  733.08
#Mann= 3 , 0 , 0
       0     .06       0     499    .045       0   595.8      .1       0
Bank Sta=499,595.8
XS Rating Curve= 0 ,0
Exp/Cntr=0.3,0.1

Type RM Length L Ch R = 1 ,16405.6 ,579.2,580,580.8
XS GIS Cut Line= 4
     1574379.821      377822.756     1574260.463      377801.055
     1573832.946      377601.402     1573789.543      377577.531
#Sta/Elev= 30
       0  740.82      28  737.88    37.3  736.53    46.7  734.12      56  730.45
      84  717.75   102.6  709.69     112  705.99   121.3  702.64   131.1  699.45
     141   696.8   150.8  694.83   160.6   693.7   170.5   693.2   190.1  693.01
   327.7  694.47   367.1  694.23   396.6  693.07   465.4  689.18   475.2  688.62
     485   687.5   494.8  684.92   504.7  681.28   514.5   678.9   524.3  678.42
   542.8  678.25   553.8  679.57   563.7   683.5   573.5  688.95   642.7  729.25
#Mann= 3 , 0 , 0
       0     .06       0     485    .045       0   573.5      .1       0
Bank Sta=485,573.5
XS Rating Curve= 0 ,0
Exp/Cntr=0.3,0.1

Type RM Length L Ch R = 1 ,15825.6 ,187.9,186.3,184.6
XS GIS Cut Line= 4
     1574531.731      377358.347     1574483.987      377293.242
     1574015.237      377043.677     1573754.821      377134.822
#Sta/Elev= 30
       0  738.12    35.9  722.76    90.6  700.94   110.2  693.93   120.1  691.45
   129.9  690.31   139.7  690.09   179.1  690.99   188.9  690.54   208.6   688.2
   228.2  687.46   257.8  688.86   316.8   694.2   336.4  694.55   375.8  689.94
   385.6  687.81     404681.0213   415.1  677.82   434.8  677.02   454.4  677.25
     483678.8358   503.6  680.57   523.3  683.11   552.8  688.56   582.3  695.17
   611.8   699.9   640.3  705.92   697.4  719.34   830.6  747.64   887.7  761.58
#Mann= 3 , 0 , 0
       0     .06       0     404    .045       0     483      .1       0
Bank Sta=404,483
XS Rating Curve= 0 ,0
Exp/Cntr=0.3,0.1

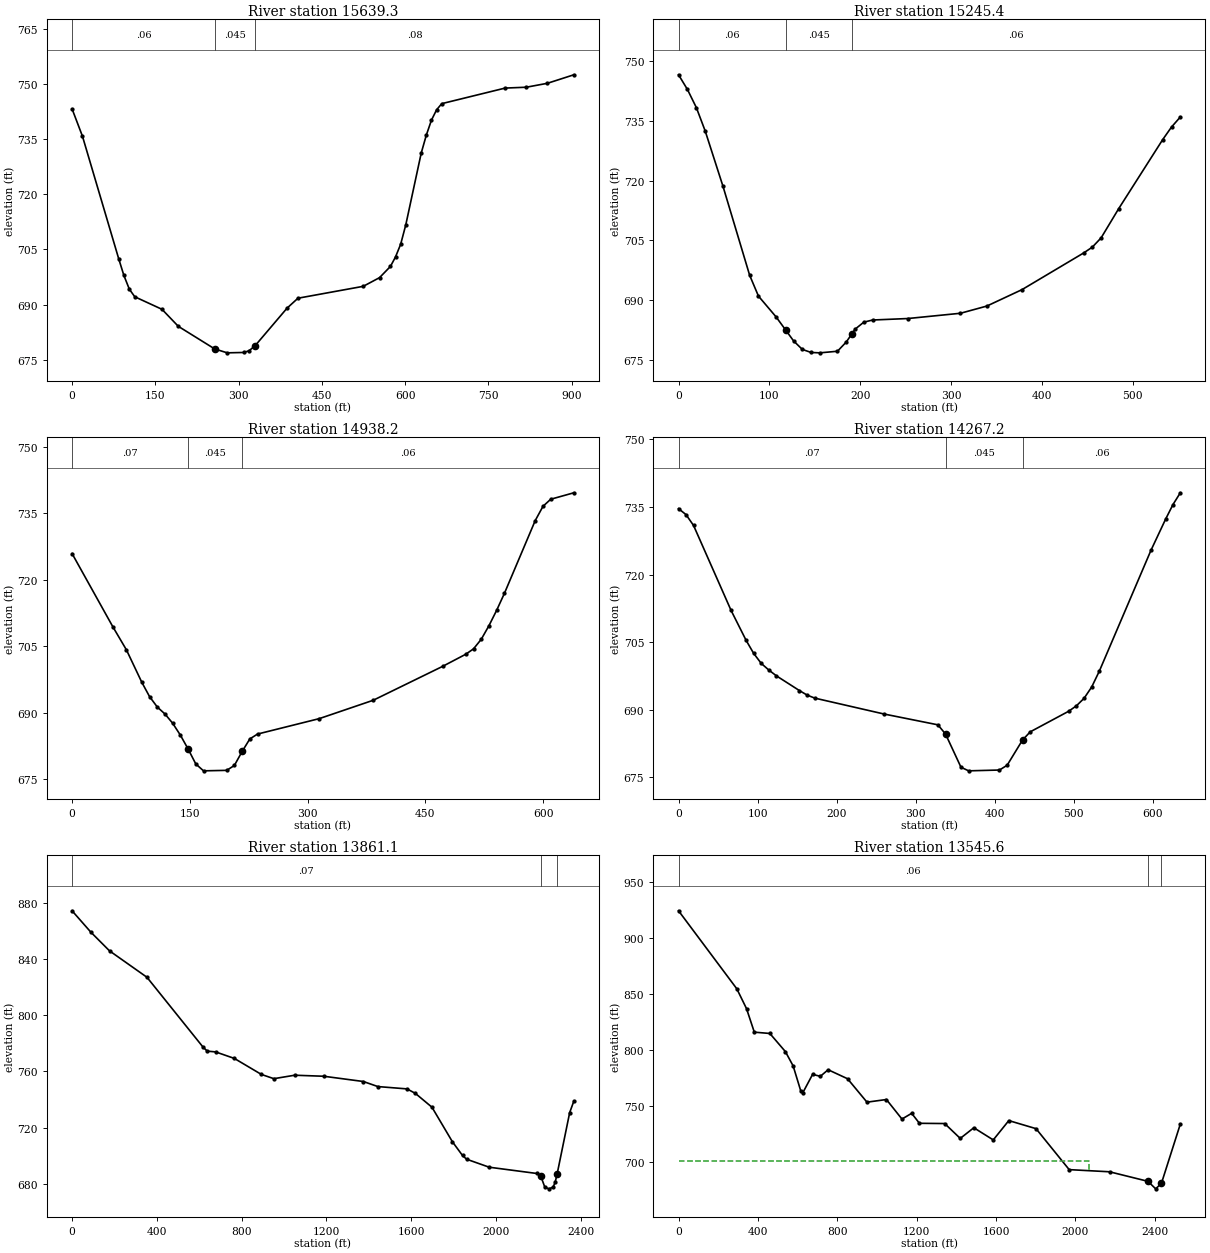
Type RM Length L Ch R = 1 ,15639.3 ,394,393.9,393.8
XS GIS Cut Line= 5
     1574603.345        377100.1     1574510.029       377104.44
     1574069.491      376913.468     1574010.897      376841.854
     1573913.241       376624.84
#Sta/Elev= 30
       0  743.18    18.7  735.76    84.1  702.45    93.4  697.94   103.2  694.22
     113  692.16     162  688.76   191.4  684.14     257677.9992   279.6  676.94
     309  677.04   318.8  677.49     330678.9114   387.4  689.08     407  691.77
   524.6     695     554  697.36   573.6   700.4   582.8  702.99   592.1  706.45
   601.3  711.71   629.1  731.19   638.3  736.07   647.6  740.15   656.8  742.93
   666.1   744.6   780.3  748.83   818.4  749.06   856.5  750.13   904.1  752.44
#Mann= 3 , 0 , 0
       0     .06       0     257    .045       0     330     .08       0
Bank Sta=257,330
XS Rating Curve= 0 ,0
Exp/Cntr=0.3,0.1

Type RM Length L Ch R = 1 ,15245.4 ,309.5,307.2,304.7
XS GIS Cut Line= 4
     1574668.449      376739.857     1574603.345      376718.156
     1574282.165      376583.607     1574147.616      376566.246
#Sta/Elev= 30
       0  746.51     9.8  742.83    19.6  738.29    29.4  732.39      49  718.51
    78.3  696.25      88  691.02   107.3  685.84     118682.5067   126.7  679.78
   136.3  677.66     146  676.89   155.7   676.8     175   677.2   184.7  679.52
     191681.6049   194.4  682.73     204  684.49   213.7  685.03   252.4   685.4
   310.4  686.72   339.5  688.53   378.2  692.65   445.9  701.82   455.6   703.3
   465.3  705.63   484.7  712.97   533.1  730.26   542.8  733.41   552.5  735.93
#Mann= 3 , 0 , 0
       0     .06       0     118    .045       0     191     .06       0
Bank Sta=118,191
XS Rating Curve= 0 ,0
Exp/Cntr=0.3,0.1

Type RM Length L Ch R = 1 ,14938.2 ,662.1,671.1,678.7
XS GIS Cut Line= 3
     1574749.014      376489.227     1574725.476      376424.168
     1574179.434      376261.071
#Sta/Elev= 30
       0  725.93    51.9  709.42    69.2  704.21    88.8  696.89    98.7  693.65
   108.5  691.31   118.3  689.73   128.1  687.65     138  684.94   147.8  681.82
   157.6  678.45   167.4   676.9   196.9  677.01   206.7  678.11   216.6  681.27
   226.4   684.1   236.2   685.2   314.8  688.68   383.6  692.83     472  700.48
   501.5  703.22   511.3  704.43   521.2   706.6     531  709.67   540.8  713.14
   550.6  716.93   589.9  733.38   599.8   736.6   609.6  738.19   639.1  739.65
#Mann= 3 , 0 , 0
       0     .07       0   147.8    .045       0   216.6     .06       0
Bank Sta=147.8,216.6
XS Rating Curve= 0 ,0
Exp/Cntr=0.3,0.1

Type RM Length L Ch R = 1 ,14267.2 ,404.5,406.1,408.8
XS GIS Cut Line= 4
     1574974.439       375997.67     1574933.206      375891.333
     1574599.005      375639.597     1574503.519      375602.704
#Sta/Elev= 30
       0  734.64     9.5   733.3      19   730.9    66.5  712.02    85.5  705.38
      95   702.5   104.6  700.27     114  698.82   123.8   697.5     153  694.22
   162.7  693.22   172.4  692.55     260  689.02   328.1  686.62   337.8  684.57
   357.3   677.2     367   676.4     406  676.58   415.7  677.64   435.2  683.25
   444.9  685.06   493.5  689.63   503.3  690.84     513   692.5   522.7  695.03
   532.4  698.57   597.6  725.36   616.2  732.31   625.5  735.54   634.8  738.16
#Mann= 3 , 0 , 0
       0     .07       0   337.8    .045       0   435.2     .06       0
Bank Sta=337.8,435.2
XS Rating Curve= 0 ,0
Exp/Cntr=0.3,0.1

Type RM Length L Ch R = 1 ,13861.1 ,312.7,315.5,318.1
XS GIS Cut Line= 5
     1576079.401      377243.221     1575201.478      375744.626
      1575143.71      375624.406     1574824.699      375324.927
     1574789.977      375277.183
#Sta/Elev= 30
       0  874.22    88.3  859.06   176.6  845.71   353.2  826.92   618.2  777.15
   637.8  774.36   677.1  773.82   765.4  769.18   892.9   757.8   951.8  754.77
  1049.9  757.23  1187.3   756.5  1373.8  752.76  1442.4  749.16  1579.8   747.5
  1619.1  744.33  1697.6  734.45    1794  709.87  1841.6  700.13  1860.7  697.49
  1967.4  691.79  2191.1  687.35  2210.5  685.55    2230  677.52  2249.4   676.4
  2268.9  677.59  2278.6  681.09  2288.3  687.27  2347.1  730.65  2366.8  738.84
#Mann= 3 , 0 , 0
       0     .07       0  2210.5    .045       0  2288.3      .1       0
Bank Sta=2210.5,2288.3
XS Rating Curve= 0 ,0
Exp/Cntr=0.3,0.1

Type RM Length L Ch R = 1 ,13545.6 ,329.1,331.8,334.6
XS GIS Cut Line= 5
     1576739.123      376902.943     1575473.738      375525.675
     1575388.935      375498.538     1575065.585      375112.253
     1575039.543      375051.489
#Sta/Elev= 30
       0  924.29   293.8  854.69   342.7  837.01   381.9  816.03   460.2  814.87
   538.6  798.69   577.7  785.91   616.9  763.16   626.7  762.08   675.7  778.39
   714.8  776.65     754  782.52   851.9  774.49   949.8   753.6  1047.8  755.96
  1126.1  738.54  1175.1  743.65  1214.2  734.75  1341.5  734.53  1419.9  721.28
  1488.4  730.78  1586.3  719.93  1664.7  737.17  1801.8  729.98    1969  693.43
  2172.5  691.51  2366.2  682.99    2405   676.3    2434  681.21  2529.2  734.08
#Mann= 3 , 0 , 0
       0     .06       0  2366.2    .045       0    2434      .1       0
#XS Ineff= 2 , 0
         2070.02  701.26
Permanent Ineff=
       F       F
Bank Sta=2366.2,2434
XS Rating Curve= 0 ,0
Exp/Cntr=0.3,0.1

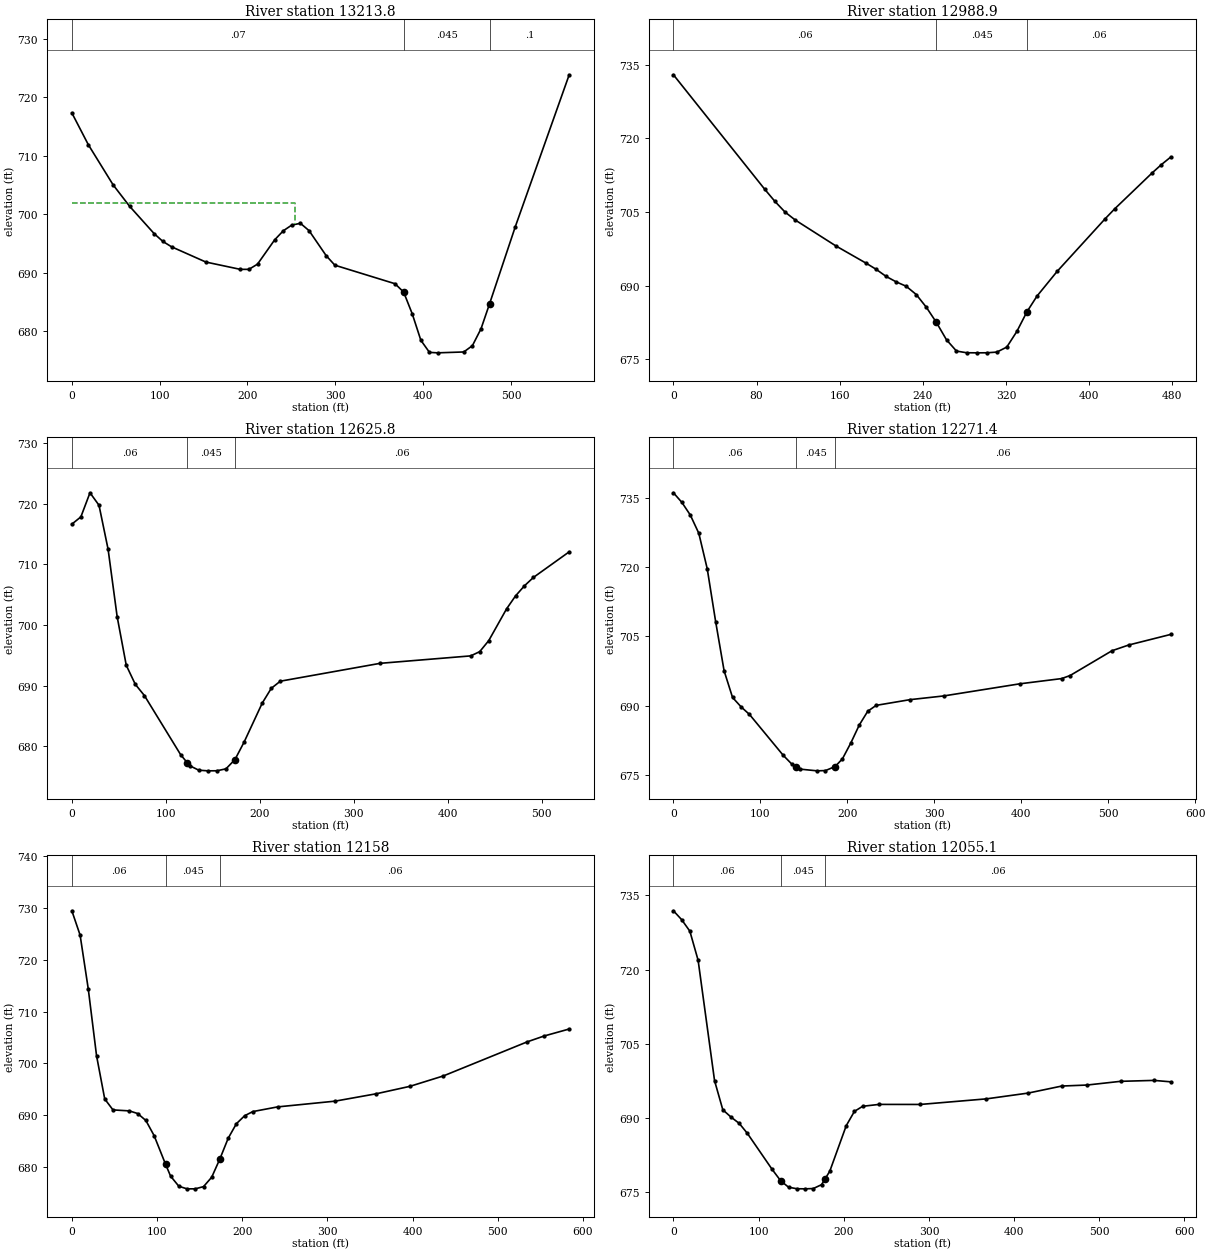
Type RM Length L Ch R = 1 ,13213.8 ,225.7,224.9,224.3
XS GIS Cut Line= 4
     1575642.842      375331.437     1575571.227      375270.673
     1575347.703      374925.621     1575323.831      374869.197
#Sta/Elev= 30
       0  717.34    18.8  711.89      47  705.03    65.7  701.38    93.9  696.66
   103.7  695.35   113.5  694.44   152.6  691.83   191.8  690.58   201.6  690.58
   211.4  691.47     231  695.64   240.8  697.18   250.5  698.16   260.3  698.45
   270.1   697.2   289.7   692.9   299.5  691.29     368  688.12   377.8  686.69
   387.6  682.97   397.4  678.45   407.2  676.38   416.5   676.3   446.3  676.45
   456.1  677.53   465.9  680.41   475.7  684.72     505   697.9   566.3  723.86
#Mann= 3 , 0 , 0
       0     .07       0   377.8    .045       0   475.7      .1       0
#XS Ineff= 2 , 0
          254.56  701.91
Permanent Ineff=
       F       F
Bank Sta=377.8,475.7
XS Rating Curve= 0 ,0
Exp/Cntr=0.3,0.1

Type RM Length L Ch R = 1 ,12988.9 ,384.5,363.1,341.4
XS GIS Cut Line= 4
     1575801.262      374966.854     1575645.012      374966.854
     1575512.633      374775.881     1575425.828       374752.01
#Sta/Elev= 30
       0  732.92    87.9   709.6    97.7  707.13   107.4  704.97   117.2  703.35
   156.2  698.09   185.3  694.57     195  693.32   204.7  691.86   214.3  690.76
     224  689.86   233.7  688.17   243.4  685.58   253.1  682.48   262.8  678.95
   272.4  676.66   282.1  676.32   291.8   676.3   301.5  676.31   311.2  676.45
   320.8  677.47   330.5  680.66   340.2  684.66   349.9  687.86   369.2  692.87
   415.6  703.63   424.6  705.61   460.6  712.92   469.6  714.63   478.6  716.17
#Mann= 3 , 0 , 0
       0     .06       0   253.1    .045       0   340.2     .06       0
Bank Sta=253.1,340.2
XS Rating Curve= 0 ,0
Exp/Cntr=0.3,0.1

Type RM Length L Ch R = 1 ,12625.8 ,363.7,354.3,344.6
XS GIS Cut Line= 3
     1575892.408      374545.847      1575458.38      374541.506
     1575371.574      374580.569
#Sta/Elev= 30
       0  716.64     9.6  717.84    19.3  721.82    28.9  719.76    38.6  712.47
    48.2  701.37    57.9  693.34    67.5   690.2    77.2  688.34   115.8  678.57
     123677.2125   125.4  676.76     135  676.02   144.7  675.91   154.3  675.92
     164  676.24   173.6  677.78   183.3  680.66   202.6   687.1   212.2  689.53
   221.8  690.71     328  693.66   424.4  694.89     434  695.59   443.6  697.41
   462.6  702.66   472.1  704.79   481.6  706.46   491.2  707.85   529.2  712.07
#Mann= 3 , 0 , 0
       0     .06       0     123    .045       0   173.6     .06       0
Bank Sta=123,173.6
XS Rating Curve= 0 ,0
Exp/Cntr=0.3,0.1

Type RM Length L Ch R = 1 ,12271.4 ,112.7,113.4,114.3
XS GIS Cut Line= 3
     1575822.963       374133.52     1575484.422       374281.09
     1575286.939      374326.663
#Sta/Elev= 30
       0  736.23     9.7  734.15    19.4   731.4    29.2  727.43    38.9  719.71
    48.6  708.19    58.3  697.54      68  691.75    77.8  689.71    87.5  688.05
   126.3  679.17   136.1  677.28     141676.7193   145.8  676.17   165.2   675.8
   174.9  675.86     186676.7386   194.4  678.41   204.1  681.88   213.8  685.77
   223.5  688.75   233.2  690.03   272.1  691.27     311  692.08   398.3  694.71
   446.5  695.85   456.2  696.51   504.4   701.9   523.7  703.15     572  705.45
#Mann= 3 , 0 , 0
       0     .06       0     141    .045       0     186     .06       0
Bank Sta=141,186
XS Rating Curve= 0 ,0
Exp/Cntr=0.3,0.1

Type RM Length L Ch R = 1 ,12158   ,102.9,102.9,102.9
XS GIS Cut Line= 3
      1575766.54      374040.204     1575443.189      374168.242
     1575252.217      374307.131
#Sta/Elev= 30
       0  729.44     9.7  724.75    19.3  714.35      29  701.49    38.6  693.15
    48.3  691.04    67.6  690.85    77.3  690.34    86.9     689    96.6  686.08
     110680.5724   115.9  678.28   125.6  676.32   135.2  675.82   144.9  675.82
   154.6  676.25   164.2  678.06   173.9  681.63   183.6  685.59   193.2  688.38
   202.9  689.92   212.5  690.72   241.5  691.62   309.1  692.73   357.6  694.16
     397  695.59   436.3   697.6   534.7  704.17   554.4  705.29   583.9  706.64
#Mann= 3 , 0 , 0
       0     .06       0     110    .045       0   173.9     .06       0
Bank Sta=110,173.9
XS Rating Curve= 0 ,0
Exp/Cntr=0.3,0.1

Type RM Length L Ch R = 1 ,12055.1 ,327.3,316.2,304.1
XS GIS Cut Line= 3
     1575744.838      373938.208     1575421.487      374066.246
     1575230.515      374205.135
#Sta/Elev= 30
       0  731.88     9.7  730.08    19.3  727.76      29  721.88    48.3  697.55
      58  691.67    67.6   690.2    77.3  688.92    86.9  686.89   115.9  679.63
     126677.3142   135.2  676.03   144.9  675.72   154.6   675.7   164.2  675.76
   173.9  676.54     178677.6939   183.6  679.27   202.9  688.46   212.5  691.35
   222.2  692.38   241.5  692.76   289.8  692.75   367.5  693.88   416.6  695.05
     456  696.47   485.5  696.67   524.9  697.42   564.2  697.61   583.9  697.32
#Mann= 3 , 0 , 0
       0     .06       0     126    .045       0     178     .06       0
Bank Sta=126,178
XS Rating Curve= 0 ,0
Exp/Cntr=0.3,0.1

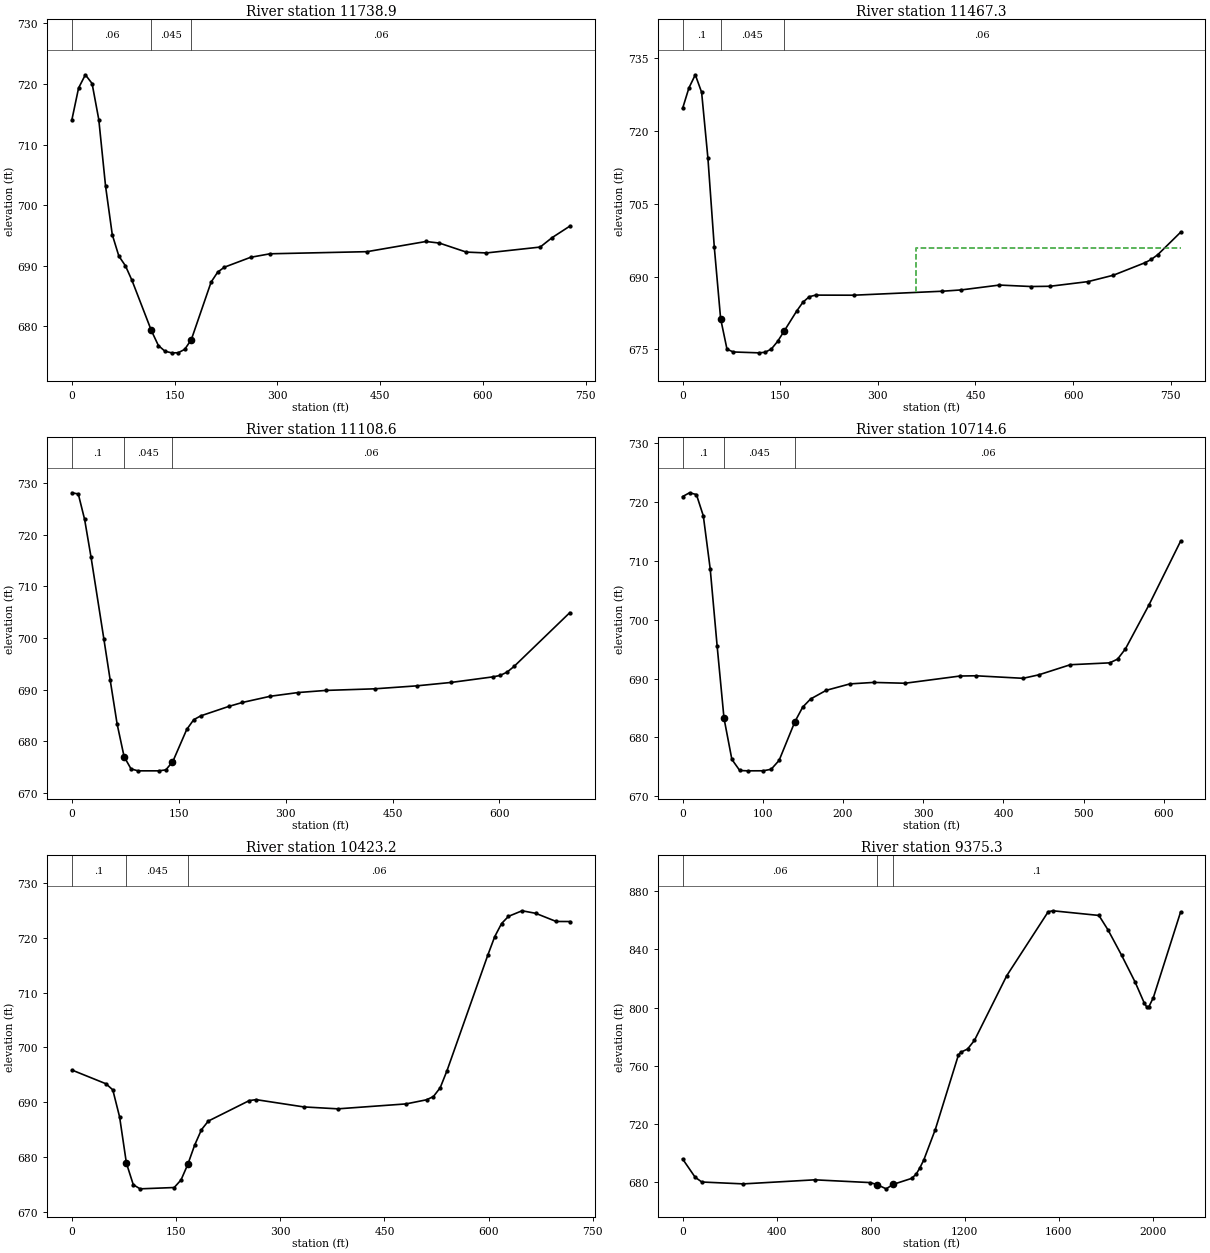
Type RM Length L Ch R = 1 ,11738.9 ,286.2,271.6,257.8
XS GIS Cut Line= 6
      1575553.05      373603.388      1575512.85      373646.541
     1575384.812      373802.791     1575365.281      374028.486
     1575225.415      374166.264     1575219.283      374208.965
#Sta/Elev= 30
       0  714.07     9.8  719.33    19.7  721.51    29.5  720.07    39.3  714.12
    49.2  703.11      59  695.11    68.6  691.58    78.2  689.98    87.8  687.56
     116679.3012   126.3  676.82   135.9  675.88   145.6  675.61   155.2  675.62
   164.8  676.19   174.4  677.79   203.3  687.29   212.9  688.93   222.5  689.74
     261  691.38   289.3  691.96   430.9  692.31     517  693.99   536.6  693.73
   575.9  692.24   605.3   692.1   683.8  693.07   701.1  694.62     727  696.52
#Mann= 3 , 0 , 0
       0     .06       0     116    .045       0   174.4     .06       0
Bank Sta=116,174.4
XS Rating Curve= 0 ,0
Exp/Cntr=0.3,0.1

Type RM Length L Ch R = 1 ,11467.3 ,371.3,358.8,346
XS GIS Cut Line= 3
     1575239.248      373474.482      1575200.73      374203.591
     1575216.028      374235.007
#Sta/Elev= 30
       0  724.65     9.7  728.87    19.5  731.57    29.2  727.96    38.9  714.36
    48.7  696.03    58.4  681.34    68.2  675.05    77.9  674.48   116.8   674.3
   126.6  674.41   136.3  675.08     146  676.66   155.8  678.73   175.2  682.89
     185  684.75   194.7  685.86   204.4  686.19   262.8  686.17   399.1  686.99
   428.3  687.26   486.8  688.26   535.4  687.96   564.6  688.01     623  688.97
     662  690.29   710.7  692.87   720.4  693.56   730.1  694.51   765.1  699.12
#Mann= 3 , 0 , 0
       0      .1       0    58.4    .045       0   155.8     .06       0
#XS Ineff= 2 , 0
                          359.21           695.9
Permanent Ineff=
       F       F
Bank Sta=58.4,155.8
XS Rating Curve= 0 ,0
Exp/Cntr=0.3,0.1

Type RM Length L Ch R = 1 ,11108.6 ,397.8,394,390
XS GIS Cut Line= 3
     1574872.659      373679.093     1574909.552      373718.156
     1575222.052      374282.392
#Sta/Elev= 30
       0  728.13       9   727.9    17.9  722.96    26.9  715.66    44.8  699.91
    53.7  691.93    63.5  683.36    73.3  677.04      83  674.68    92.8   674.3
   122.1   674.3   131.9  674.49     141676.0035   141.7  676.12   161.2  682.32
     171   684.2   180.8  684.94   219.9  686.76   239.4  687.54   278.5  688.74
   317.6  689.46   356.7  689.87   425.1  690.18   483.7  690.75   532.6  691.42
   591.2   692.5     601  692.77   610.8  693.42   620.5  694.51   698.7  704.92
#Mann= 3 , 0 , 0
       0      .1       0    73.3    .045       0     141     .06       0
Bank Sta=73.3,141
XS Rating Curve= 0 ,0
Exp/Cntr=0.3,0.1

Type RM Length L Ch R = 1 ,10714.6 ,290.1,291.4,292.8
XS GIS Cut Line= 3
      1574573.18      373987.253     1574623.093      374000.274
     1574983.336      374440.812
#Sta/Elev= 30
       0  720.96     8.6   721.6    17.2   721.3    25.8  717.68    34.4  708.65
      43  695.58    51.6  683.24    61.4  676.25    71.2  674.36      81   674.3
   100.6  674.31   110.4  674.57   120.3  676.08   139.9  682.64   149.7  685.14
   159.5  686.52   179.1     688   208.6  689.09     238  689.34   277.2   689.2
   345.9  690.43   365.6  690.47   424.4  690.04     444  690.63   483.3  692.35
   532.4  692.67   542.2   693.3     552  695.04   581.4  702.53   620.7  713.34
#Mann= 3 , 0 , 0
       0      .1       0    51.6    .045       0   139.9     .06       0
Bank Sta=51.6,139.9
XS Rating Curve= 0 ,0
Exp/Cntr=0.3,0.1

Type RM Length L Ch R = 1 ,10423.2 ,1007.6,1047.8,1087.5
XS GIS Cut Line= 2
     1574371.357      374136.992     1574790.194       374718.59
#Sta/Elev= 30
       0  695.87    49.1  693.36    58.9  692.25    68.7  687.31    78.5  678.89
    88.4  674.95    98.2   674.2   147.3  674.44   157.1  675.82   166.9  678.67
   176.7  682.16   186.5  684.98   196.4  686.56   255.3  690.29   265.1  690.47
   333.8  689.14   382.9  688.79   481.1  689.69   510.5  690.44   520.4  691.03
   530.2  692.64     540  695.76   598.9  716.89   608.7   720.2   618.5  722.58
   628.4  723.89     648  724.91   667.6  724.45   697.1  722.96   716.7  722.95
#Mann= 3 , 0 , 0
       0      .1       0    78.5    .045       0   166.9     .06       0
Bank Sta=78.5,166.9
XS Rating Curve= 0 ,0
Exp/Cntr=0.3,0.1

Type RM Length L Ch R = 1 ,9375.3  ,235,239.5,244.6
XS GIS Cut Line= 6
     1574353.996      374115.291     1574293.232      374128.312
     1573451.218      374525.447     1573431.687      374551.489
      1573244.89      375272.493     1572975.054      375490.863
#Sta/Elev= 30
       0  696.05    53.3  683.51    81.7  680.24   258.1  678.95   561.9  681.74
   797.1  679.85   826.5  678.51   865.7  675.55   895.1   678.6   973.5   682.7
   993.1  685.56  1009.4  690.09  1025.7  695.38  1074.7   716.3  1172.7  767.31
  1182.5   769.3  1211.9  771.58  1241.3  777.55  1378.5  821.92  1554.9  865.86
  1574.5  866.52  1770.5  863.32    1809  853.44  1866.9  836.02  1924.8  817.46
  1963.3  803.19    1973   800.7  1982.6   800.5  2001.9  806.82  2117.6  865.52
#Mann= 3 , 0 , 0
       0     .06       0   826.5    .045       0   895.1      .1       0
Bank Sta=826.5,895.1
XS Rating Curve= 0 ,0
Exp/Cntr=0.3,0.1