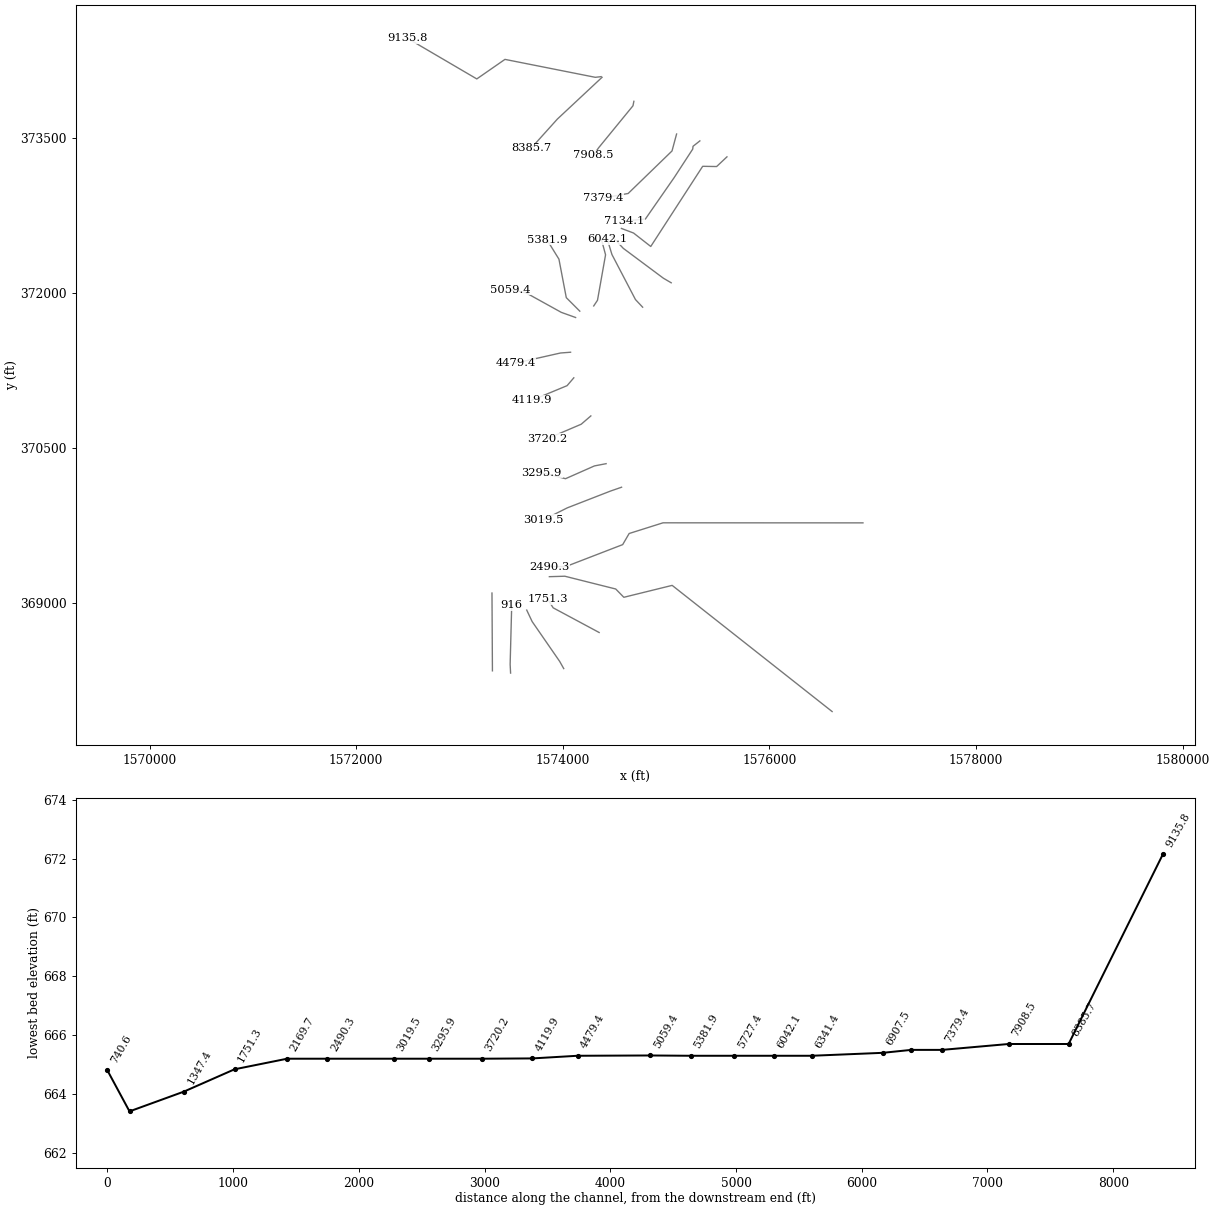
HEC-RAS study PTPLSCRK.prj: PTPLSCRK

--- PTPLSCRK.g01 (geometry) --- (continued)

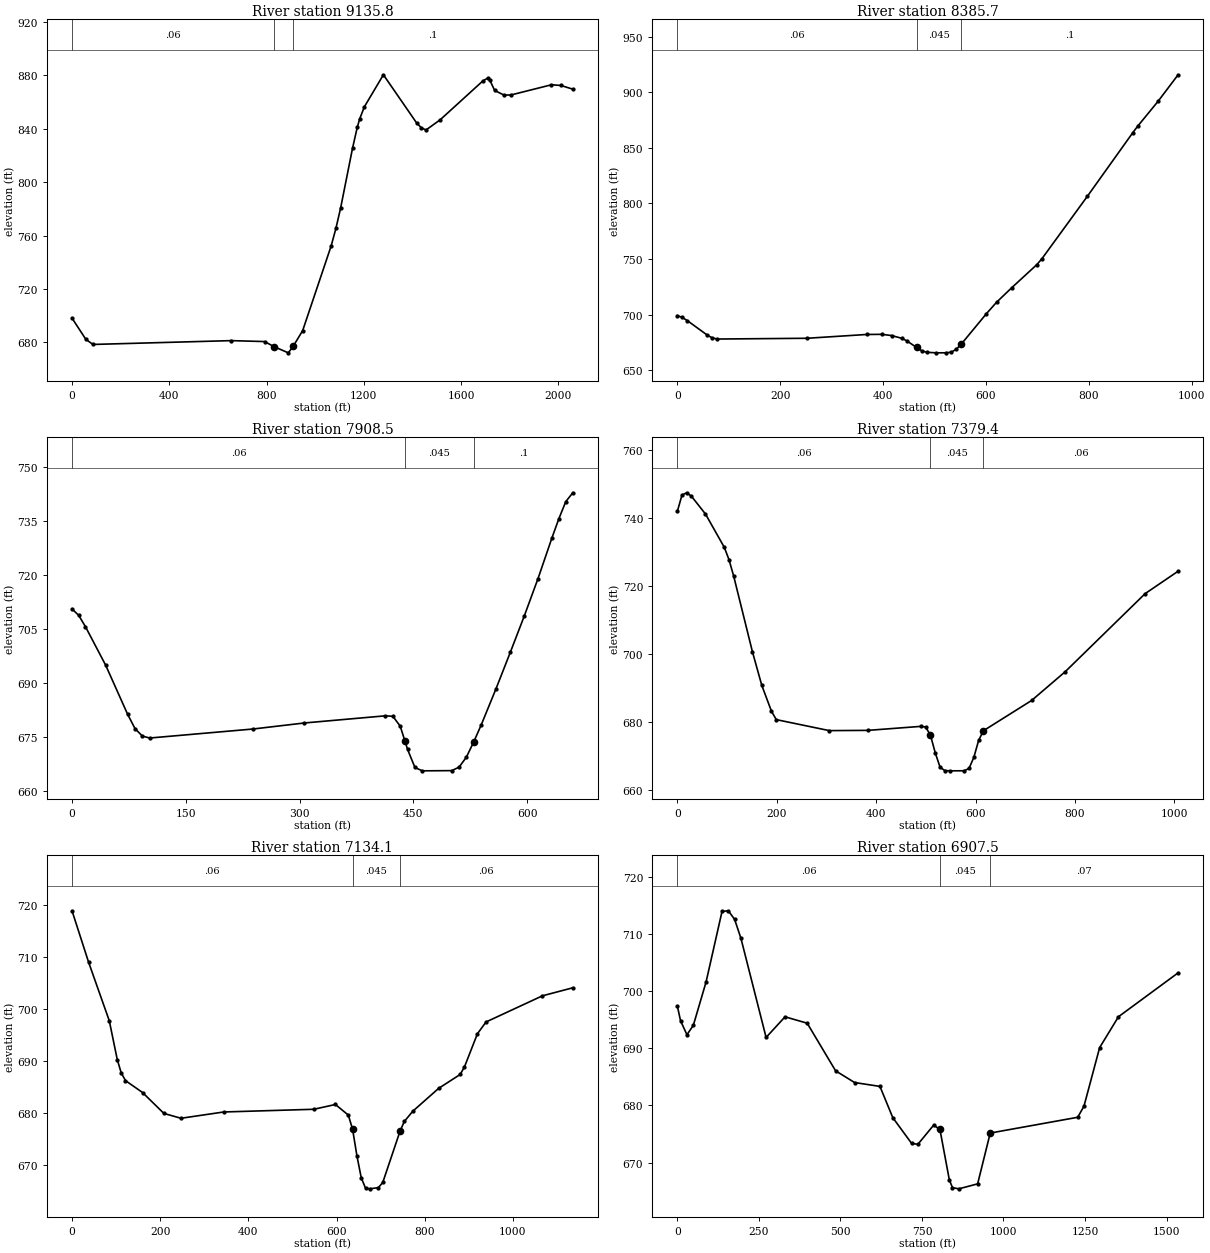
Type RM Length L Ch R = 1 ,9135.8  ,727.9,750.1,771.6
XS GIS Cut Line= 5
     1574371.357       374091.42     1574314.934      374084.909
     1573440.368       374258.52     1573167.715      374069.375
     1572495.887      374463.085
#Sta/Elev= 30
       0  698.16    56.8  682.29    86.2  678.44   654.5   681.3   791.7   680.6
     831676.7659   889.3  672.15   909.2  676.98   948.4  688.83  1065.6  752.32
  1085.1  765.43  1104.6  780.81  1153.4   825.5  1172.9  841.17  1182.7  847.42
  1202.2  856.57  1280.3  880.52  1416.5  844.54    1436  840.83  1455.5  839.14
  1513.9  846.81  1689.1  875.88  1708.6  877.99  1718.3  876.32  1737.8  868.76
  1776.7  865.25  1805.9  865.44  1971.4  873.03  2010.3  872.51    2059  869.74
#Mann= 3 , 0 , 0
       0     .06       0     831    .045       0   909.2      .1       0
Bank Sta=831,909.2
XS Rating Curve= 0 ,0
Exp/Cntr=0.3,0.1

Type RM Length L Ch R = 1 ,8385.7  ,474.1,477.2,480.3
XS GIS Cut Line= 3
     1574380.038      374084.909      1573948.18      373681.263
     1573692.104      373396.975
#Sta/Elev= 30
       0  699.26     9.7  697.49    19.4  694.67    58.1  681.66    67.8  679.17
    77.5  678.11     252   678.8   368.2  682.21   397.3  682.34   416.7  681.25
   436.1   678.8   445.8  676.58   465.2  670.55   474.8  667.68   484.5  666.21
   503.5   665.7   523.3  665.74     533  666.34   542.7  669.08   552.4  673.73
   600.9  700.87   620.6  711.15     650  724.18     699  745.03   708.8  750.28
   797.2  806.44   885.4  863.57   895.3  869.64   934.5  891.77   973.7  915.75
#Mann= 3 , 0 , 0
       0     .06       0   465.2    .045       0   552.4      .1       0
Bank Sta=465.2,552.4
XS Rating Curve= 0 ,0
Exp/Cntr=0.3,0.1

Type RM Length L Ch R = 1 ,7908.5  ,531.7,529.1,526.5
XS GIS Cut Line= 4
     1574688.198      373852.704     1574679.517      373809.302
     1574347.486      373403.486     1574294.751      373328.616
#Sta/Elev= 30
       0  710.69     8.8   708.9    17.7  705.76    44.3  695.08    73.4  681.37
    83.1  677.42    92.8  675.35   102.5  674.82   238.5  677.32   306.4     679
   413.2  680.99     423  680.86   432.7  678.11     439673.9144   442.4  671.65
   452.1  666.63   461.8   665.7   500.6  665.76   510.3  666.72     520  669.53
   529.8  673.83   539.5  678.47   558.9  688.46   577.8  698.61   596.1  708.64
   614.4  719.14   632.7  730.41   641.9  735.78     651  740.51   660.2  742.96
#Mann= 3 , 0 , 0
       0     .06       0     439    .045       0   529.8      .1       0
Bank Sta=439,529.8
XS Rating Curve= 0 ,0
Exp/Cntr=0.3,0.1

Type RM Length L Ch R = 1 ,7379.4  ,240.8,245.3,250.9
XS GIS Cut Line= 4
     1575101.609      373536.081     1575057.338      373372.019
     1574632.859       372960.56     1574390.672      372916.289
#Sta/Elev= 30
       0  741.95     9.4  746.78    18.9  747.42    28.3  746.41    56.6  741.16
    94.4  731.36   103.8  727.75   113.3  722.88     151  700.59   169.9  690.66
   189.3  683.06     199  680.59   305.6  677.35   383.1  677.42   489.7   678.6
   499.4  678.42   509.1  676.02   518.8  670.79   528.5  666.56   538.2  665.56
   547.9   665.5     577  665.52   586.7  666.22   596.4  669.45     606  674.46
   615.7  677.32   712.6  686.23     780  694.68     941  717.71  1007.3  724.31
#Mann= 3 , 0 , 0
       0     .06       0   509.1    .045       0   615.7     .06       0
Bank Sta=509.1,615.7
XS Rating Curve= 0 ,0
Exp/Cntr=0.3,0.1

Type RM Length L Ch R = 1 ,7134.1  ,216.4,226.6,237.7
XS GIS Cut Line= 6
     1575327.009      373469.592     1575260.739      373417.162
     1575257.859      373390.248     1575078.172      373114.206
     1574799.526      372713.164     1574593.797      372694.935
#Sta/Elev= 30
       0  718.97    37.6  709.08    84.5  697.83   102.6  690.37   111.6  687.79
   121.3  686.31     160  684.02   208.4     680   247.2  679.07   344.1  680.28
   548.5   680.8   597.4  681.72   626.7  679.68   636.4  676.95   646.2  671.85
     656  667.63   665.7  665.63   675.5   665.5     695  665.74   704.8  666.72
   743.8  676.54   753.6  678.45   773.1  680.44   831.7  684.83   880.5   687.5
   890.2  688.96   919.5  695.32   939.1  697.59    1067  702.62  1135.8  704.16
#Mann= 3 , 0 , 0
       0     .06       0   636.4    .045       0   743.8     .06       0
Bank Sta=636.4,743.8
XS Rating Curve= 0 ,0
Exp/Cntr=0.3,0.1

Type RM Length L Ch R = 1 ,6907.5  ,612.7,566.1,517.4
XS GIS Cut Line= 6
     1575589.161      373315.078     1575489.264      373221.253
     1575354.213      373223.581     1574851.609      372447.539
     1574684.942      372577.748     1574567.755      372622.019
#Sta/Elev= 30
       0  697.38     9.8  694.81    29.4  692.36      49  694.01    88.1   701.6
     137  713.94   156.4  714.05   175.6  712.54   194.9  709.24   272.1  691.89
   330.2   695.5   398.1  694.38   485.2  686.05   543.4     684   621.2  683.32
   660.5  677.86   718.4  673.34   737.6   673.2   785.8  676.54   805.1  675.79
     834  666.95   843.6  665.61   862.9   665.4   920.7  666.27   959.3  675.16
  1227.5  677.92  1246.7  679.85  1294.8  690.11  1352.5  695.51  1535.4  703.19
#Mann= 3 , 0 , 0
       0     .06       0   805.1    .045       0   959.3     .07       0
Bank Sta=805.1,959.3
XS Rating Curve= 0 ,0
Exp/Cntr=0.3,0.1

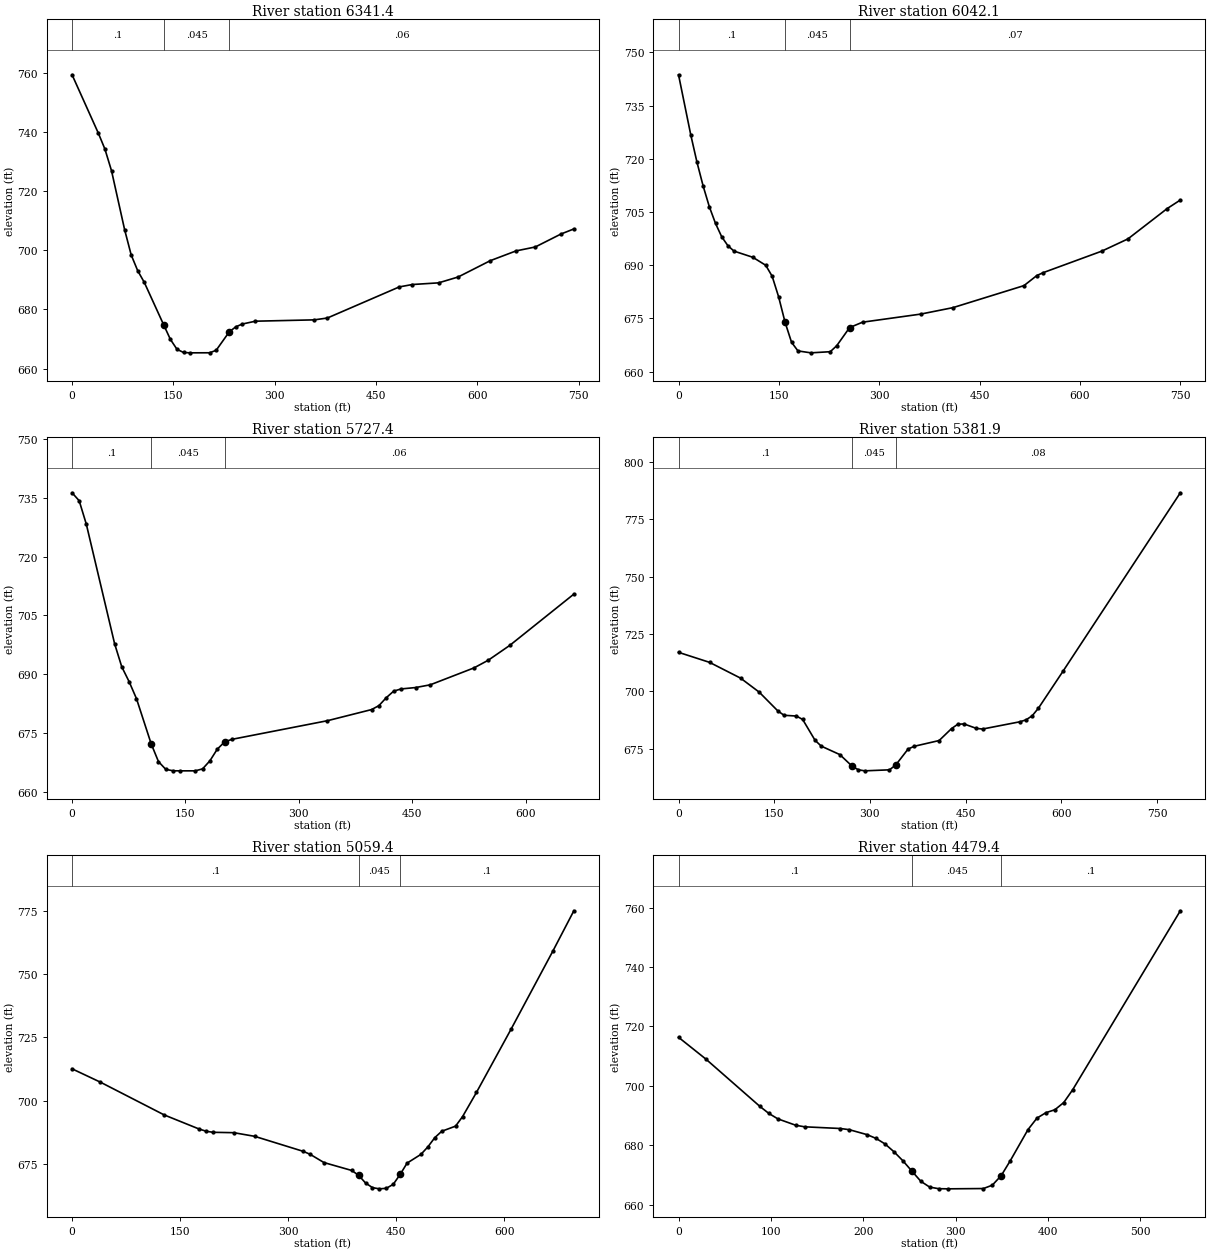
Type RM Length L Ch R = 1 ,6341.4  ,309.4,299.3,289.1
XS GIS Cut Line= 4
     1575049.526      372095.977     1574974.005      372140.248
     1574585.984       372429.31     1574468.797       372554.31
#Sta/Elev= 30
       0  759.31    38.9  739.56    48.6   734.2    58.4  726.85    77.8  706.92
    87.5   698.4    97.2  693.04   106.9  689.12   135.9  674.61   145.6  669.82
   155.3   666.5     165  665.42   174.6   665.3   203.7  665.32   213.3  666.17
   232.7   672.4   242.4  674.11     252  675.04   271.4     676   358.5  676.45
   377.8  677.07   484.3  687.59   503.7   688.4   542.4  688.96   571.4  690.94
     619  696.46   657.1  699.76   685.6  701.09   723.7  705.48   742.7  707.19
#Mann= 3 , 0 , 0
       0      .1       0   135.9    .045       0   232.7     .06       0
Bank Sta=135.9,232.7
XS Rating Curve= 0 ,0
Exp/Cntr=0.3,0.1

Type RM Length L Ch R = 1 ,6042.1  ,329.5,314.7,299.8
XS GIS Cut Line= 4
      1574773.05      371859.866     1574703.606       371933.65
     1574475.741      372369.848     1574430.168      372519.588
#Sta/Elev= 30
       0  743.69    18.4  726.64    27.6  719.01    36.8  712.32    46.1  706.45
    55.3  701.77    64.5  698.03    73.7  695.52    82.9  693.98     111  692.24
   130.3  689.99   139.9  686.91   149.6  681.09   159.2  673.94   168.9  668.28
   178.5  665.84   197.8   665.3   226.8  665.62   236.4   667.3   255.7  672.42
     275  673.94   361.9  676.22   410.1  678.04   516.3  684.25   535.6   687.1
   545.2  687.92   632.6  693.97   671.7  697.42   730.4  705.98     750  708.38
#Mann= 3 , 0 , 0
       0      .1       0   159.2    .045       0   255.7     .07       0
Bank Sta=159.2,255.7
XS Rating Curve= 0 ,0
Exp/Cntr=0.3,0.1

Type RM Length L Ch R = 1 ,5727.4  ,337.1,345.6,354
XS GIS Cut Line= 4
     1574299.526      371872.019     1574335.984      371926.706
     1574414.109       372366.81     1574375.047      372512.644
#Sta/Elev= 30
       0  736.34     9.4  734.31    18.8  728.35    56.3  697.75    65.7  691.89
    75.4  688.11    85.2  683.74   104.6  672.22   114.3  667.65     124  665.67
   133.8  665.31   142.7   665.3   162.9   665.3   172.6   665.8   182.3  667.86
     192  670.82   201.8   672.7   211.5  673.35   337.8  678.11   396.1  680.95
   405.8  681.95   415.5  683.97   425.3  685.65     435  686.22   454.4  686.58
   473.8  687.28   531.6   691.6   550.4  693.55   578.8  697.33   663.7  710.45
#Mann= 3 , 0 , 0
       0      .1       0   104.6    .045       0   201.8     .06       0
Bank Sta=104.6,201.8
XS Rating Curve= 0 ,0
Exp/Cntr=0.3,0.1

Type RM Length L Ch R = 1 ,5381.9  ,302.8,322.4,342
XS GIS Cut Line= 4
     1574164.665      371821.428     1574033.965      371952.128
     1573962.883      372324.737     1573845.941      372513.908
#Sta/Elev= 30
       0  717.01    48.6  712.64    97.3  705.74   126.5  699.63   155.6  691.46
   165.4  689.54   184.8  689.21   194.6  687.71     214  678.63   223.7  676.08
   252.9  672.38   272.4  667.24   282.1  665.74   291.8   665.3   330.7  665.74
   340.5  667.86   359.9  674.83   369.6  676.02   408.5  678.52     428  683.75
   437.7  685.62   447.4  685.77   466.9  683.82   476.6  683.54     535   686.7
   544.7  687.54   554.4  689.32   564.2  692.66   602.8  708.81   786.6  786.63
#Mann= 3 , 0 , 0
       0      .1       0   272.4    .045       0   340.5     .08       0
Bank Sta=272.4,340.5
XS Rating Curve= 0 ,0
Exp/Cntr=0.3,0.1

Type RM Length L Ch R = 1 ,5059.4  ,563.5,580.1,596.5
XS GIS Cut Line= 4
     1574124.178      371760.039      1573985.29      371809.953
     1573640.237      372000.925     1573488.328      372029.137
#Sta/Elev= 30
       0  712.61    39.4  707.34   127.9  694.44   176.4  688.88   186.1  688.02
   195.7  687.59   224.5  687.44   253.4  686.01   320.7   680.1   330.3  678.94
   349.6  675.67   388.1  672.56   397.7  670.66   407.3  667.63   416.9  665.79
   426.5  665.31   436.2  665.52   445.8  667.09   455.4  670.99     465  675.45
   484.2  678.89   493.9  681.86   503.5  685.49   513.1     688   532.3  690.02
     542  693.77   561.3  703.31   609.6  728.37   667.5  759.09   696.5   774.9
#Mann= 3 , 0 , 0
       0      .1       0   397.7    .045       0   455.4      .1       0
Bank Sta=397.7,455.4
XS Rating Curve= 0 ,0
Exp/Cntr=0.3,0.1

Type RM Length L Ch R = 1 ,4479.4  ,355.5,359.5,363.2
XS GIS Cut Line= 4
     1574075.468      371423.859     1573977.894      371416.473
     1573657.111      371344.132      1573543.35      371318.824
#Sta/Elev= 30
       0  716.36    29.4  709.07    88.1  693.07    97.8   690.7   107.5  688.88
   126.9  686.72   136.5   686.2   175.2  685.63   184.9  685.23   204.2  683.55
   213.9  682.28   223.6  680.41   233.3  677.77   242.9  674.75   252.6  671.27
   262.3  667.84   271.9  665.88   281.6  665.35   291.3   665.3     330   665.4
   339.6  666.52   349.3  669.75     359  674.71   378.3  685.26     388  689.13
   397.7  690.96   407.4  691.95     417  694.38   426.7   698.7   543.2  758.99
#Mann= 3 , 0 , 0
       0      .1       0   252.6    .045       0   349.3      .1       0
Bank Sta=252.6,349.3
XS Rating Curve= 0 ,0
Exp/Cntr=0.3,0.1

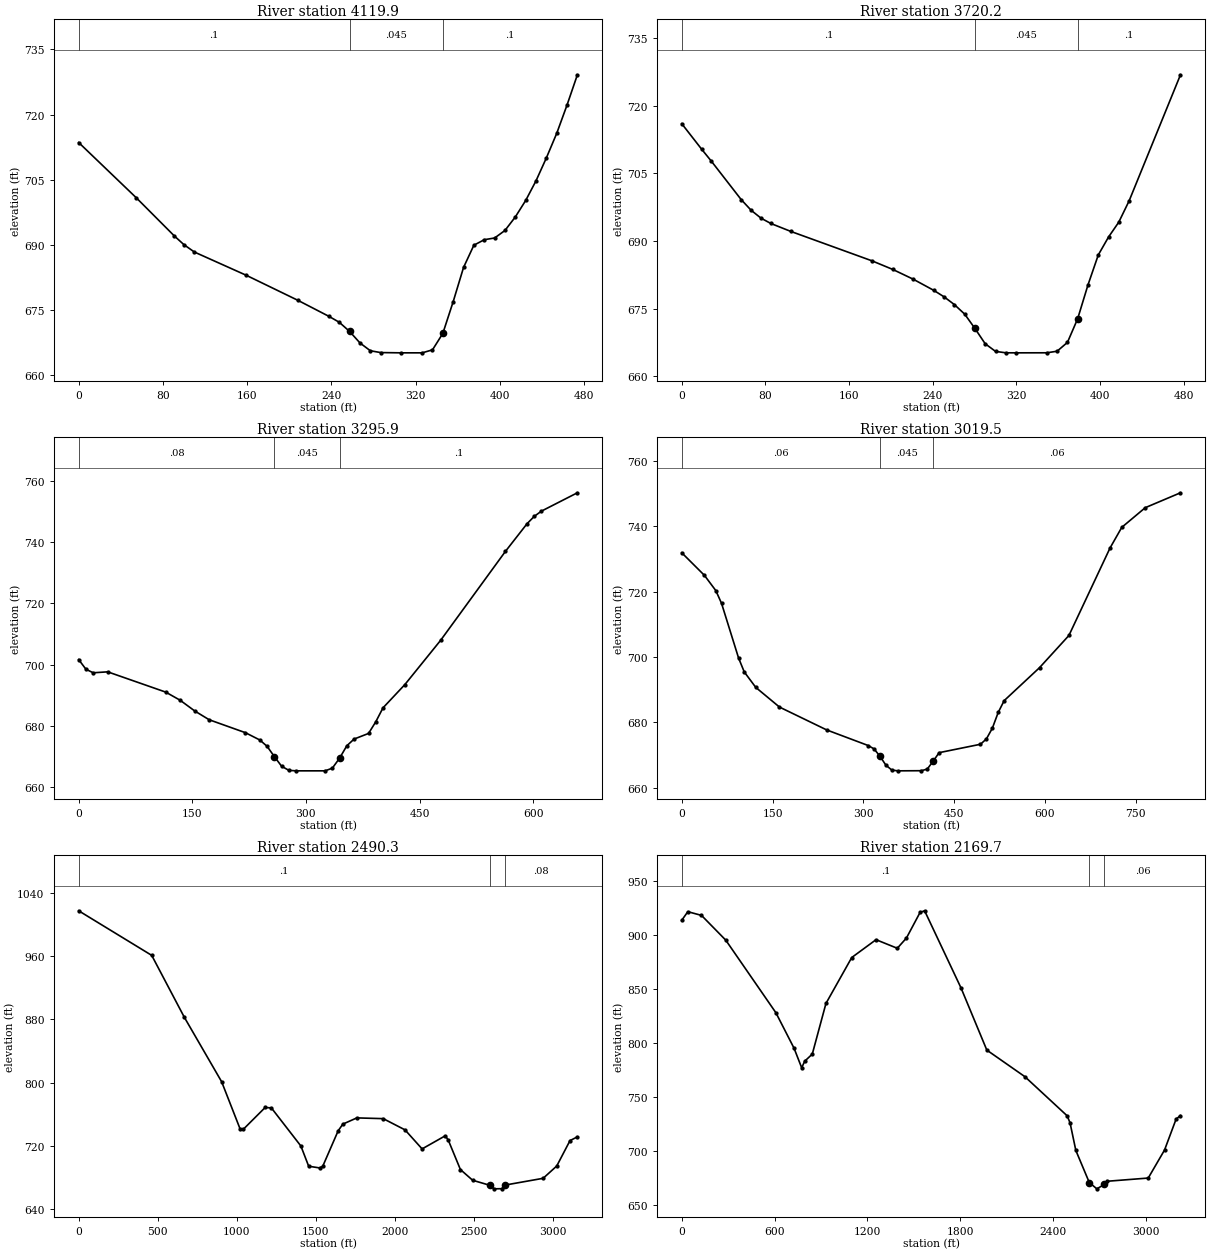
Type RM Length L Ch R = 1 ,4119.9  ,399.5,399.7,399.9
XS GIS Cut Line= 3
     1574106.817      371176.272     1574041.713      371100.317
     1573696.661      370957.088
#Sta/Elev= 30
       0   713.6    54.6  700.91    90.9  692.09     100  690.09   109.9   688.4
     159  683.07   208.2  677.29   237.7   673.6   247.5  672.24   257.3  670.13
   267.2  667.47     277  665.69   286.8  665.27   306.5  665.21   326.2  665.21
     336   665.9   345.8  669.67   355.7  677.02   365.5  684.86   375.3  689.97
   385.2  691.24     395  691.63   404.8  693.36   414.6  696.45   424.5  700.26
   434.3  704.78   444.1  710.03     454  715.72   463.8  722.24   473.6  729.18
#Mann= 3 , 0 , 0
       0      .1       0   257.3    .045       0   345.8      .1       0
Bank Sta=257.3,345.8
XS Rating Curve= 0 ,0
Exp/Cntr=0.3,0.1

Type RM Length L Ch R = 1 ,3720.2  ,424.1,424.4,424.6
XS GIS Cut Line= 3
     1574271.748      370807.348     1574178.432      370727.053
     1573852.911      370588.164
#Sta/Elev= 30
       0  716.02    18.9   710.4    28.4  707.68    56.8   699.2    66.3  696.83
    75.8  695.07    85.2  693.89   104.2  692.14   182.1  685.59   201.8   683.7
   221.4  681.53   241.1  679.05   250.9  677.62   260.7  675.91   270.6  673.79
   280.4  670.61   290.2  667.22   300.1  665.52   309.9  665.21   319.7   665.2
   349.2  665.21     359  665.56   368.9  667.52   378.7  672.79   388.5  680.24
   398.4  686.92   408.2  690.89     418  694.19   427.9  698.92     477  726.87
#Mann= 3 , 0 , 0
       0      .1       0   280.4    .045       0   378.7      .1       0
Bank Sta=280.4,378.7
XS Rating Curve= 0 ,0
Exp/Cntr=0.3,0.1

Type RM Length L Ch R = 1 ,3295.9  ,277.4,276.4,275.4
XS GIS Cut Line= 4
     1574419.317      370345.109      1574306.47      370323.407
     1574026.522      370199.709     1573796.487      370258.303
#Sta/Elev= 30
       0  701.62     9.6  698.45    19.2  697.29    38.3   697.6   114.9  690.97
     134   688.3   153.2   684.8   172.3  681.92   220.1  677.69   239.2  675.29
   248.8  673.21   258.4  669.85   267.9  666.71   277.5  665.36   287.1   665.2
   325.3   665.2   334.9  666.08   344.5  669.36     354   673.4   363.6   675.6
   382.7  677.44   392.3  681.28   401.8  685.82   430.5  693.39   477.9  707.93
   563.4  737.02   591.9  746.06   601.4  748.47   610.9  750.19   658.4   756.2
#Mann= 3 , 0 , 0
       0     .08       0   258.4    .045       0   344.5      .1       0
Bank Sta=258.4,344.5
XS Rating Curve= 0 ,0
Exp/Cntr=0.3,0.1

Type RM Length L Ch R = 1 ,3019.5  ,529.2,529.2,529
XS GIS Cut Line= 4
     1574569.057      370117.244      1574462.72      370080.352
     1574043.883      369917.591     1573809.508      369800.404
#Sta/Elev= 30
       0  731.91    37.5  724.99    56.3  720.33    65.7  716.45    93.8  699.75
   103.2  695.47   122.3  690.72   161.4  684.71   239.5  677.71   307.9  672.95
   317.7  671.91   327.5  669.65   337.2  666.94     347  665.44   356.8   665.2
   395.8  665.24   405.6  665.74   415.4  668.18   425.2  670.76   493.5  673.33
   503.3  674.97   513.1  678.24   522.8  683.07   532.6  686.67     591  696.75
   639.6  706.61   707.5  733.36   726.9  739.68   765.7   745.7   823.9  750.26
#Mann= 3 , 0 , 0
       0     .06       0   327.5    .045       0   415.4     .06       0
Bank Sta=327.5,415.4
XS Rating Curve= 0 ,0
Exp/Cntr=0.3,0.1

Type RM Length L Ch R = 1 ,2490.3  ,334.5,320.6,306.7
XS GIS Cut Line= 6
      1576905.79      369772.156     1574970.312      369772.698
     1574642.425      369669.175     1574579.908      369561.689
     1574028.692      369349.015     1573870.272      369349.015
#Sta/Elev= 30
       0 1017.88   461.8  961.33   668.1  882.76   903.9  801.04  1021.8  740.54
  1041.4  740.82    1179  768.38  1218.3  767.85  1404.9  719.52  1454.1  693.88
  1522.8  691.75  1542.5  693.57  1640.7  738.88  1670.2   747.3  1758.6  755.18
  1925.6  754.23  2063.2  739.99  2171.2  715.85  2317.6  732.47  2336.7  726.98
  2413.4  689.66  2490.8  676.07  2597.4  669.81  2626.4   665.2  2674.9  665.39
  2694.2  669.92  2936.4  678.56  3022.4  694.16  3106.3  726.42  3152.9  731.12
#Mann= 3 , 0 , 0
       0      .1       0  2597.4    .045       0  2694.2     .08       0
Bank Sta=2597.4,2694.2
XS Rating Curve= 0 ,0
Exp/Cntr=0.3,0.1

Type RM Length L Ch R = 1 ,2169.7  ,423.7,418.4,412.7
XS GIS Cut Line= 6
     1576607.179      367945.767     1575058.802      369167.039
     1574590.939      369051.832     1574512.633      369132.001
     1574020.012      369255.699     1573870.272      369251.359
#Sta/Elev= 30
       0  913.42    39.2  921.34   127.6  917.92   284.5  895.03   608.3     828
     726  795.12   775.1   777.1   794.7  783.14   843.8  789.76   932.1  836.55
  1098.8  878.98  1255.8  895.46  1393.2  887.53  1452.1  896.95  1540.4  920.65
  1569.8  922.18  1805.3  850.82    1972  793.41  2217.9  768.87  2491.2  732.69
  2509.9   726.2  2547.3  700.69  2634.3  671.03  2683.2   665.2    2732  669.32
  2751.5  672.22  3015.3  675.18  3120.7  701.08  3195.6  729.74  3223.7  732.86
#Mann= 3 , 0 , 0
       0      .1       0  2634.3    .045       0    2732     .06       0
Bank Sta=2634.3,2732
XS Rating Curve= 0 ,0
Exp/Cntr=0.3,0.1

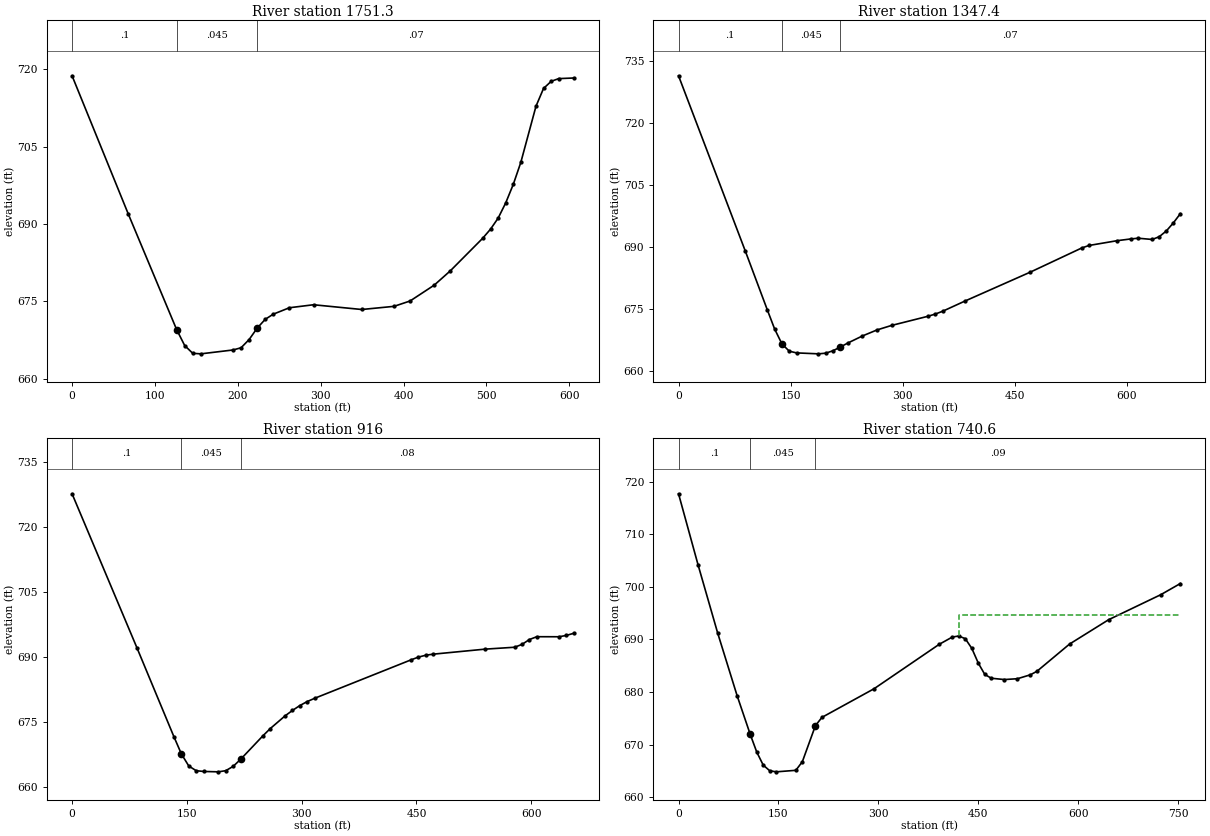
Type RM Length L Ch R = 1 ,1751.3  ,414.7,403.8,393.2
XS GIS Cut Line= 3
     1574352.043      368710.994     1573907.165      368949.709
     1573852.911      369034.345
#Sta/Elev= 30
       0  718.77      68  691.89   126.2  669.53   135.9  666.44   145.6  664.94
   155.4  664.84   194.2  665.59   203.9  666.02   213.6  667.61   223.3  669.82
     233  671.53   242.7  672.53   262.2  673.78   291.3  674.36   349.5  673.44
   388.4  674.05   407.8  675.09   436.9  678.16   456.3  680.93   495.2  687.22
   504.9  689.03     514  691.15   523.2  694.12   532.3   697.7   541.4  701.97
   559.7  712.86   568.8  716.31     578  717.69   587.1  718.22   605.4  718.34
#Mann= 3 , 0 , 0
       0      .1       0   126.2    .045       0   223.3     .07       0
Bank Sta=126.2,223.3
XS Rating Curve= 0 ,0
Exp/Cntr=0.3,0.1

Type RM Length L Ch R = 1 ,1347.4  ,445.7,431.5,417.2
XS GIS Cut Line= 4
     1574009.161      368361.602     1573970.099      368431.046
     1573703.172      368817.331     1573651.088      368928.008
#Sta/Elev= 30
       0  731.52    89.5  688.94   118.8  674.75   128.6   670.1   138.4  666.48
   148.2  664.72   157.9  664.31   187.3  664.08   197.1  664.24   206.8  664.84
   216.6  665.74   226.4  666.69     246  668.41   265.5  669.87   285.1  670.97
     334   673.2   343.8  673.74   353.6  674.42   382.9  676.85     471  683.92
   539.4  689.74   549.2  690.36   586.8  691.52   605.7  691.96   615.1  692.12
   633.9  691.82   643.3  692.49   652.7  693.87   662.1  695.82   671.5  698.07
#Mann= 3 , 0 , 0
       0      .1       0   138.4    .045       0   216.6     .07       0
Bank Sta=138.4,216.6
XS Rating Curve= 0 ,0
Exp/Cntr=0.3,0.1

Type RM Length L Ch R = 1 ,916     ,174.7,175.4,176.1
XS GIS Cut Line= 3
     1573494.838      368318.199     1573490.498      368402.834
     1573505.689      368973.581
#Sta/Elev= 30
       0  727.57    84.8  692.02   133.1  671.51   142.8  667.56   152.5  664.76
   162.2  663.67   171.8   663.5   191.2  663.41   200.9  663.68   210.6  664.69
   220.2  666.29   249.3  671.71   258.9  673.38   278.3  676.32     288  677.58
   297.6   678.7   307.3  679.63     317  680.38   442.8  689.24   452.5  689.88
   462.2  690.32   471.8  690.56   539.6  691.72   578.3  692.16     588  692.82
   597.6  693.94   607.3  694.59   636.3  694.58     646  694.89   655.7  695.39
#Mann= 3 , 0 , 0
       0      .1       0   142.8    .045       0   220.2     .08       0
Bank Sta=142.8,220.2
XS Rating Curve= 0 ,0
Exp/Cntr=0.3,0.1

Type RM Length L Ch R = 1 ,740.6   ,420.1,401.3,382.3
XS GIS Cut Line= 2
     1573319.057        368339.9     1573314.717      369092.939
#Sta/Elev= 30
       0  717.74    29.3  704.21    58.7  691.24      88  679.26   107.6  671.93
   117.4  668.56   127.1  666.08   136.9     665   146.7   664.8     176  665.09
   185.8  666.73   205.4  673.59   215.2  675.17   293.4  680.62   391.2  689.08
   410.8  690.46   420.5  690.66   430.3  690.15   440.1  688.31   449.9  685.48
   459.6  683.34   469.4  682.62     489  682.37   508.6  682.53   528.1  683.28
   537.9  683.95   586.8  689.13   645.5  693.77   723.7  698.53     753  700.65
#Mann= 3 , 0 , 0
       0      .1       0   107.6    .045       0   205.4     .09       0
#XS Ineff= 2 , 0
                           420.4           694.6
Permanent Ineff=
       F       F
Bank Sta=107.6,205.4
XS Rating Curve= 0 ,0
Exp/Cntr=0.3,0.1