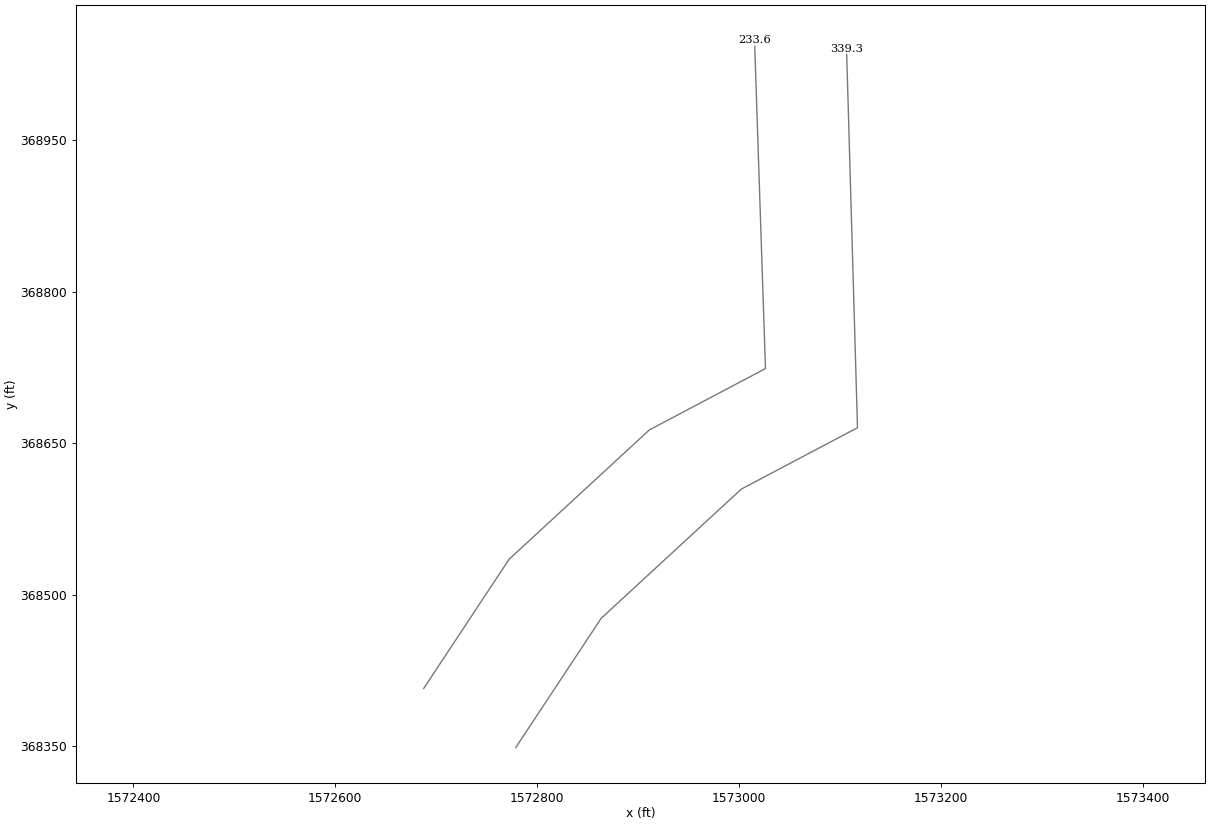
HEC-RAS study PTPLSCRK.prj: PTPLSCRK

--- PTPLSCRK.g01 (geometry) --- (continued)

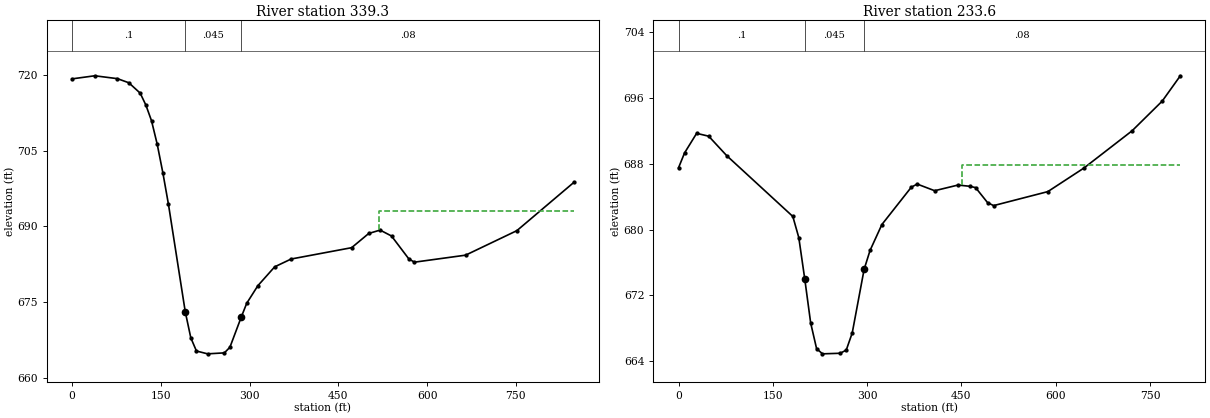
Type RM Length L Ch R = 1 ,339.3   ,105.7,105.7,105.9
XS GIS Cut Line= 5
     1572778.692      368348.581     1572863.328      368476.619
     1573002.217      368604.657     1573117.234      368665.421
     1573106.383      369040.855
#Sta/Elev= 30
       0  719.17    38.4  719.78    76.7  719.21    95.9   718.4   115.1  716.35
   124.7     714   134.3  710.88   143.9  706.25   153.5  700.57   162.9  694.37
   191.3  673.12   200.7  667.96   210.2  665.36     229   664.8   257.4  664.99
   266.8  666.11   285.7  671.99   295.2   674.8     314  678.27   342.4     682
   370.3  683.55   472.5  685.79   501.4   688.6   520.6  689.27   539.9   688.1
   568.8  683.63   578.4  682.92   665.1  684.31   751.8  689.16   848.1   698.7
#Mann= 3 , 0 , 0
       0      .1       0   191.3    .045       0   285.7     .08       0
#XS Ineff= 2 , 0
                          519.12             693
Permanent Ineff=
       F       F
Bank Sta=191.3,285.7
XS Rating Curve= 0 ,0
Exp/Cntr=0.3,0.1

Type RM Length L Ch R = 1 ,233.6   ,224.5,233.6,242.4
XS GIS Cut Line= 5
     1572687.547      368407.175     1572772.182      368535.213
     1572911.071      368663.251     1573026.088      368724.015
     1573015.237      369049.536
#Sta/Elev= 30
       0  687.51     9.6  689.32    28.8   691.7      48  691.35    76.7  688.98
   181.8  681.59   191.3  679.02   200.7  674.03   210.2  668.63   219.6  665.51
     229  664.88   257.2  664.95   266.8  665.34   276.3  667.42   295.2  675.15
   304.6  677.45   323.5  680.61   370.3  685.15   379.6  685.53   407.4  684.72
   444.6  685.41   463.2  685.26   472.5   685.1   491.6  683.27   501.2  682.91
   587.4  684.61   644.9  687.48   721.5  692.01   769.4  695.62   798.2   698.7
#Mann= 3 , 0 , 0
       0      .1       0   200.7    .045       0   295.2     .08       0
#XS Ineff= 2 , 0
                          450.99           687.8
Permanent Ineff=
       F       F
Bank Sta=200.7,295.2
XS Rating Curve= 0 ,0
Exp/Cntr=0.3,0.1

Chan Stop Cuts=-1
Use User Specified Reach Order=0
Composite Channel Slope=5

--- PTPLSCRK.g02 (geometry) ---

Geom Title=USGS 10m DEM_copy
Program Version=4.10

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
River Reach=PTPLSCRK        ,Main

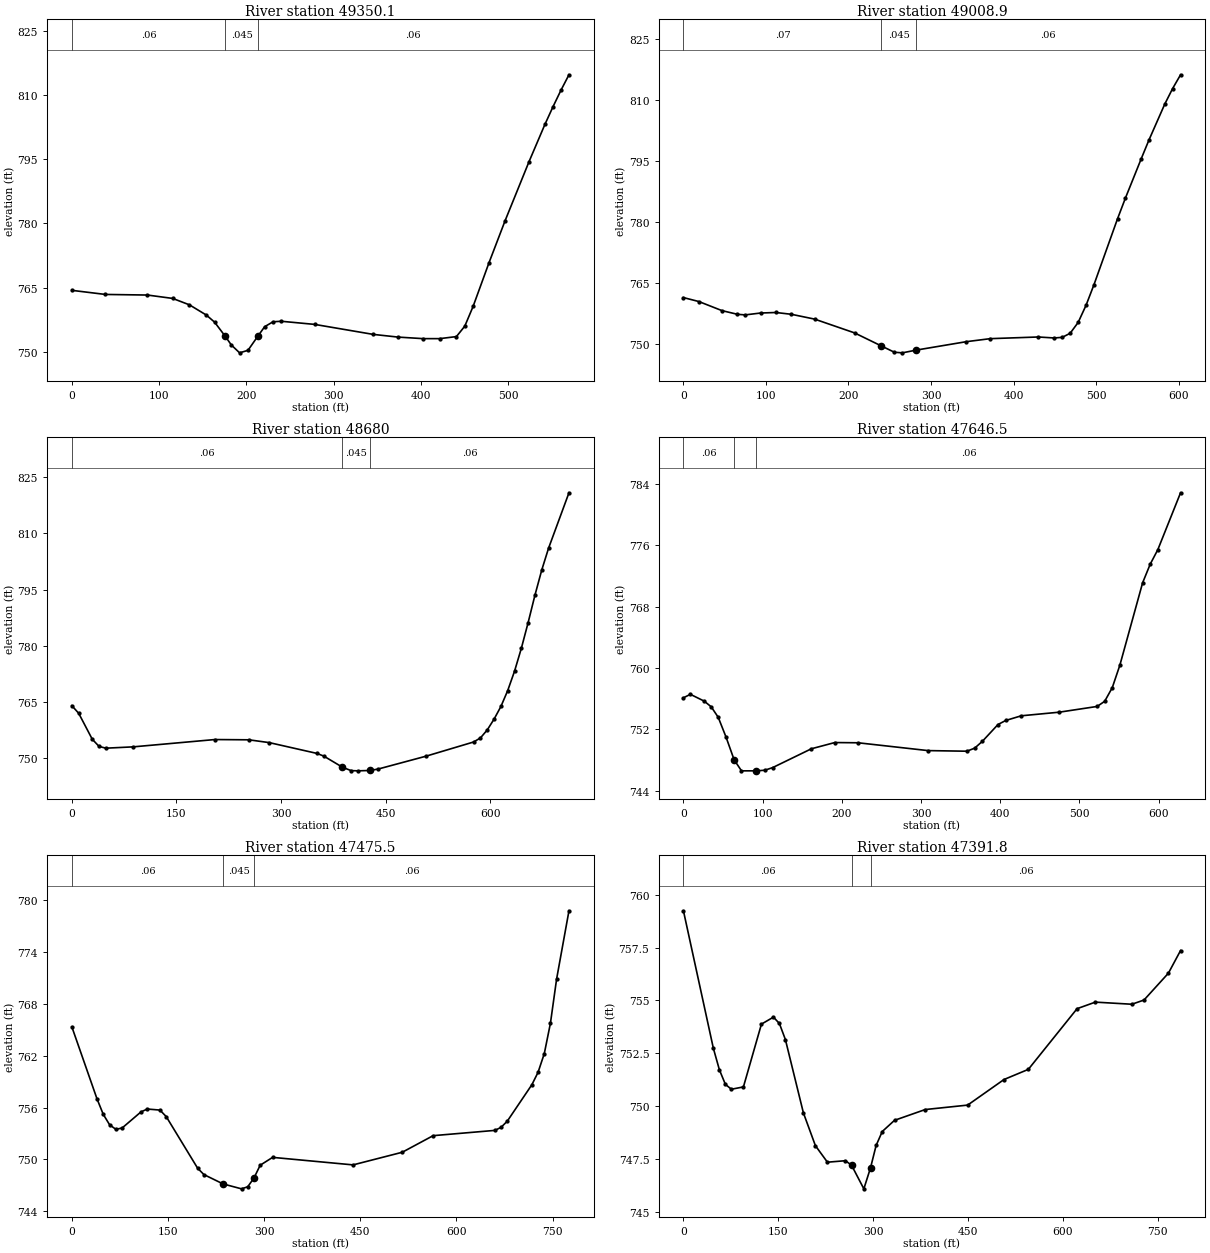
Type RM Length L Ch R = 1 ,49350.1 ,337.2,341.2,343.8
XS GIS Cut Line= 4
     1575064.344      397412.296     1574986.219      397545.109
     1574746.636      397735.213     1574652.886      397792.505
#Sta/Elev= 30
       0  764.35    38.5  763.39    86.7  763.25   115.6  762.46   134.8  760.96
   154.1  758.58   163.6  756.92     176 753.563   182.8  751.58   192.3  749.74
   201.9  750.33     213 753.575     221  755.85   230.6     757   240.1  757.12
   278.3  756.39   345.2  754.06   373.9  753.42   402.6  753.06   421.7  753.06
   440.8  753.54   450.4  755.98   459.9  760.58   478.2  770.83   496.6  780.63
     524  794.42   542.3  803.17   551.5  807.27   560.6  811.12   569.8  814.74
#Mann= 3 , 0 , 0
       0     .06       0     176    .045       0     213     .06       0
Bank Sta=176,213
XS Rating Curve= 0 ,0
Exp/Cntr=0.3,0.1

Type RM Length L Ch R = 1 ,49008.9 ,327.8,328.9,329.2
XS GIS Cut Line= 4
     1574928.927      397344.588     1574770.073      397344.588
     1574491.427      397500.838     1574413.302      397597.192
#Sta/Elev= 30
       0  761.44    18.7  760.47    46.7  758.24    65.4  757.34    74.8  757.19
    93.4  757.65   112.1  757.78   130.8  757.34   158.9  756.16   207.3  752.78
     240 749.554   255.7  748.02   265.3  747.88     282  748.55   342.8  750.62
   371.8  751.36   429.9  751.77   449.3  751.53     459  751.68   468.6  752.68
   478.3  755.34   487.9  759.56   497.4  764.56     526  780.77   535.6  785.87
   554.7  795.49   564.2  800.16   583.3  808.94   592.8  812.75   602.4  816.12
#Mann= 3 , 0 , 0
       0     .07       0     240    .045       0     282     .06       0
Bank Sta=240,282
XS Rating Curve= 0 ,0
Exp/Cntr=0.3,0.1

Type RM Length L Ch R = 1 ,48680   ,565.4,558.6,560
XS GIS Cut Line= 2
     1574798.719       396995.63     1574168.511      397328.963
#Sta/Elev= 30
       0  764.07     9.8  762.05    29.3  755.12    39.1   753.2    48.8  752.74
    87.9  753.09   205.1  755.04   253.9  754.97   283.2  754.22   351.6  751.34
   361.4  750.62     388 747.673   400.4  746.76   410.2   746.7     428 746.798
   439.5  747.19   507.8   750.6   576.2  754.39     586  755.48   595.7   757.6
   605.5  760.48   615.3  763.85     625  768.07   634.8  773.23   644.6  779.35
   654.3  786.18   664.1  793.51   673.9  800.24   683.6  806.02   712.9  820.81
#Mann= 3 , 0 , 0
       0     .06       0     388    .045       0     428     .06       0
Bank Sta=388,428
XS Rating Curve= 0 ,0
Exp/Cntr=0.3,0.1

Type RM Length L Ch R = 1 ,47646.5 ,132.1,171,175.5
XS GIS Cut Line= 4
     1574632.921      396415.769     1574589.518      396409.258
     1574218.424      396502.574     1574049.153      396611.081
#Sta/Elev= 30
       0  756.13     8.8  756.58    26.3  755.69    35.1  754.95    43.9  753.59
    53.7  751.03      64 748.043    73.3   746.6      92   746.6   102.8  746.68
   112.6  747.02   161.6  749.48   191.1  750.29   220.5  750.26   308.8  749.24
   357.8  749.16   367.7  749.56   377.5  750.46   397.1  752.64   406.9  753.17
   426.5  753.78   474.4  754.25   522.3     755   531.8  755.67   541.4  757.45
     551  760.39   579.7  771.13   589.3  773.56   598.9  775.45   627.6  782.87
#Mann= 3 , 0 , 0
       0     .06       0      64    .045       0      92     .06       0
Bank Sta=64,92
XS Rating Curve= 0 ,0
Exp/Cntr=0.3,0.1

Type RM Length L Ch R = 1 ,47475.5 ,117.6,83.6,81.2
XS GIS Cut Line= 5
     1574726.236       396287.73     1574481.011      396292.071
     1574346.462      396311.602     1574233.615      396333.303
     1574040.473      396535.126
#Sta/Elev= 30
       0  765.34    39.2  757.02      49  755.22    58.9  754.01    68.7  753.48
    78.5  753.64   107.9   755.5   117.7  755.83   137.4  755.71   147.2  754.96
   196.2  748.99     206  748.25     236 747.166   264.7   746.6   274.4  746.84
   284.1  747.85   293.8  749.33   313.2  750.24   438.7  749.37   515.4  750.83
   563.6  752.75   659.9  753.36   669.5  753.71   679.2  754.42   717.7  758.65
   727.3  760.08     737  762.24   746.6  765.76   756.2  770.86   775.5  778.76
#Mann= 3 , 0 , 0
       0     .06       0     236    .045       0   284.1     .06       0
Bank Sta=236,284.1
XS Rating Curve= 0 ,0
Exp/Cntr=0.3,0.1

Type RM Length L Ch R = 1 ,47391.8 ,156.3,166.8,174.9
XS GIS Cut Line= 5
     1574728.407      396203.095      1574472.33      396211.775
     1574337.782      396231.307     1574224.934      396253.008
     1574031.792      396454.831
#Sta/Elev= 30
       0  759.24    47.4  752.73    56.9  751.72    66.4  751.03    75.9   750.8
    94.9  750.91   123.4  753.88   142.4  754.21   151.8  753.91   161.3  753.15
   189.8  749.68   208.8  748.13   227.8  747.35   256.2  747.42   265.9  747.21
   285.4  746.09     296 747.088   304.8  748.14   314.5   748.8   333.9  749.33
   382.5  749.84   449.6  750.05   507.1  751.26   545.6  751.74   622.7  754.61
   651.6  754.92   709.4  754.82   728.6  755.02   767.2  756.29   786.4  757.36
#Mann= 3 , 0 , 0
       0     .06       0   265.9    .045       0     296     .06       0
Bank Sta=265.9,296
XS Rating Curve= 0 ,0
Exp/Cntr=0.3,0.1

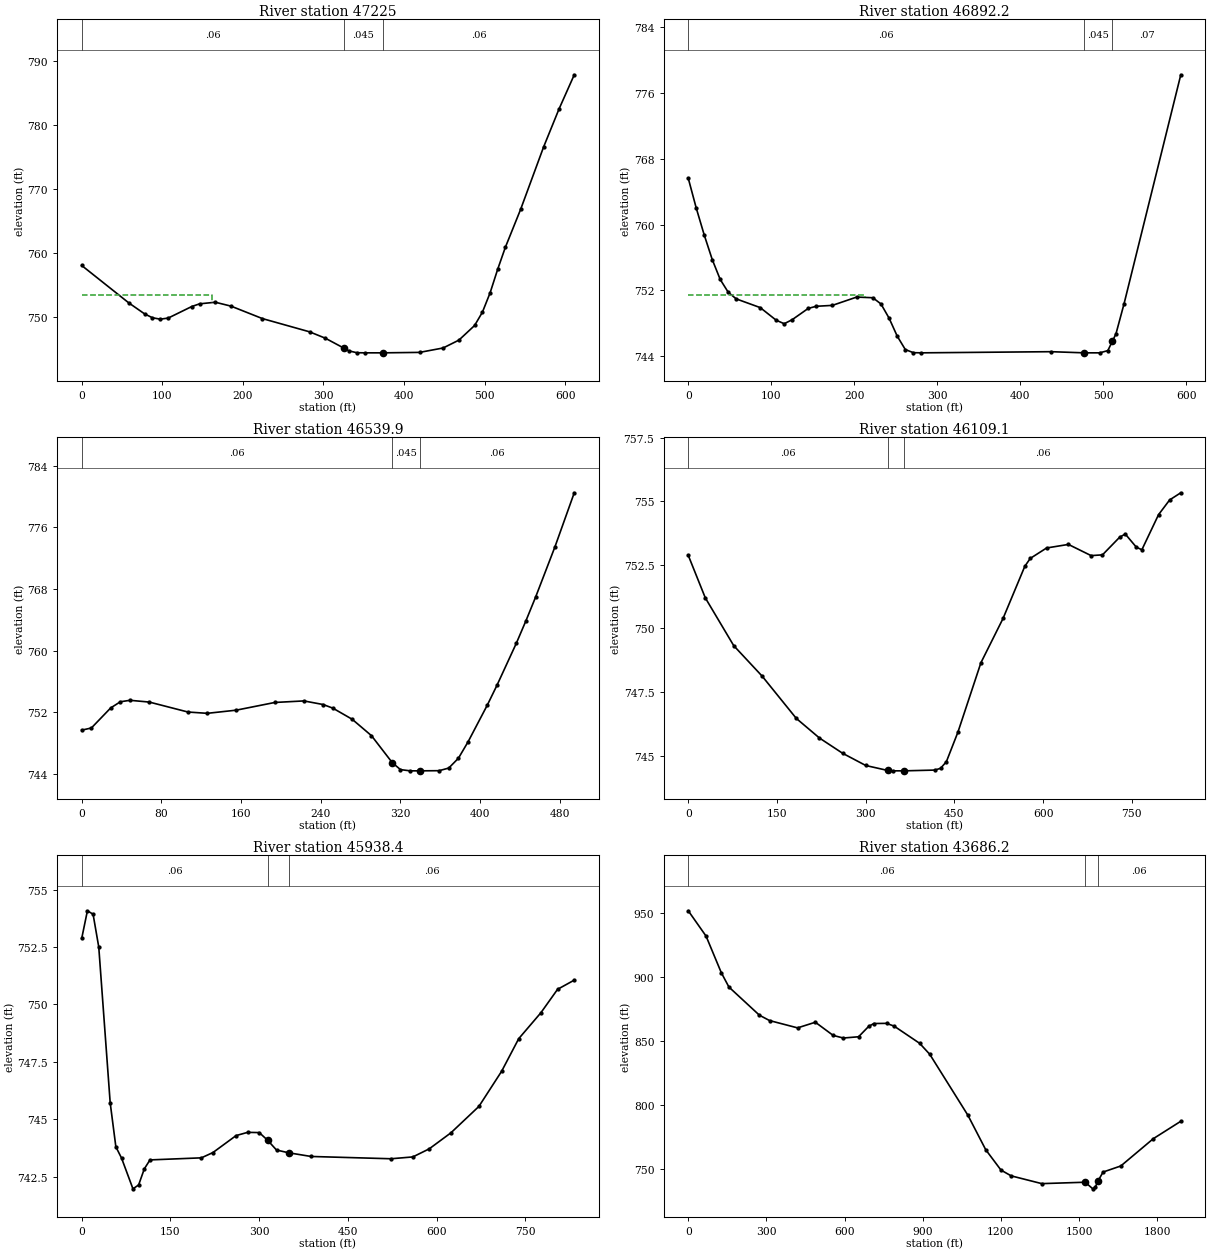
Type RM Length L Ch R = 1 ,47225   ,330.7,332.9,334.7
XS GIS Cut Line= 3
     1574745.768      396146.671     1574261.827      396031.654
     1574188.042      395944.848
#Sta/Elev= 30
       0  758.07    58.5  752.21      78   750.5    87.8  749.89    97.5  749.67
   107.3  749.84   136.6  751.65   146.3  752.07   165.8  752.32   185.3  751.71
   224.3  749.76   282.8  747.69   302.4  746.69     325 745.166   331.6  744.71
   341.4  744.42   351.1   744.4     374   744.4   419.4  744.47   448.6  745.16
   468.2  746.39   487.7  748.68   497.4  750.77   506.9  753.78   516.4   757.5
   525.9  760.93   544.9  766.88   573.4  776.64   592.4  782.54   611.4  787.92
#Mann= 3 , 0 , 0
       0     .06       0     325    .045       0     374     .06       0
#XS Ineff= 2 , 0
           161.2  753.52
Permanent Ineff=
       F       F
Bank Sta=325,374
XS Rating Curve= 0 ,0
Exp/Cntr=0.3,0.1

Type RM Length L Ch R = 1 ,46892.2 ,176.7,177,177.2
XS GIS Cut Line= 3
     1574821.723      395892.765     1574667.643      395894.935
     1574253.146      395749.536
#Sta/Elev= 30
       0  765.63     9.6  762.01    19.3  758.71    28.9  755.74    38.5  753.32
    48.2  751.76    57.8  750.96    86.7   749.9   105.9  748.37   115.6  747.94
   125.2  748.43   144.5   749.8   154.1  750.06   173.6  750.17   202.9  751.18
   222.4   751.1   232.2  750.34     242  748.61   251.7  746.44   261.5   744.8
   271.2  744.42     281   744.4   437.2  744.54     477   744.4   495.7   744.4
   505.5  744.67     511 745.815   515.3  746.71     525  750.35   593.4  778.21
#Mann= 3 , 0 , 0
       0     .06       0     477    .045       0     511     .07       0
#XS Ineff= 2 , 0
          212.58  751.38
Permanent Ineff=
       F       F
Bank Sta=477,511
XS Rating Curve= 0 ,0
Exp/Cntr=0.3,0.1

Type RM Length L Ch R = 1 ,46539.9 ,309.5,325.6,340.7
XS GIS Cut Line= 2
     1574771.809      395465.248     1574277.018      395460.907
#Sta/Elev= 30
       0  749.68     9.7  749.96    29.1  752.56    38.8  753.36    48.5  753.55
    67.9  753.32   106.7  752.03   126.1  751.86   155.2  752.27     194  753.27
   223.2  753.47   242.6     753   252.3  752.53   271.7  751.09   291.1  748.96
     312 745.457   320.2  744.56   329.9   744.4     340   744.4     359  744.42
   368.7  744.76   378.4  746.03   388.1  748.16   407.5  752.94   417.2  755.51
   436.6  760.95   446.3  763.88     456  766.95   475.4  773.46   494.8  780.47
#Mann= 3 , 0 , 0
       0     .06       0     312    .045       0     340     .06       0
Bank Sta=312,340
XS Rating Curve= 0 ,0
Exp/Cntr=0.3,0.1

Type RM Length L Ch R = 1 ,46109.1 ,170.3,170.6,170.9
XS GIS Cut Line= 6
     1574767.469      395306.828      1574622.07       395196.15
     1574376.844      394987.817     1574279.188      394890.161
     1574237.955      394803.355     1574227.105      394710.039
#Sta/Elev= 30
       0  752.87    28.8   751.2    76.9  749.32     125  748.12   182.7  746.46
   221.8  745.69     261  745.09   300.1  744.61     337 744.416   346.7   744.4
     365   744.4   416.9  744.43   426.6   744.5   436.4  744.76   455.9  745.92
   494.8  748.65   532.2  750.39     569  752.44   578.2  752.75   605.8  753.16
   642.7   753.3   681.1  752.86   700.3  752.89   729.2  753.58   738.8  753.71
   757.6  753.19   766.9  753.09   795.1  754.47   813.9  755.05   832.7  755.33
#Mann= 3 , 0 , 0
       0     .06       0     337    .045       0     365     .06       0
Bank Sta=337,365
XS Rating Curve= 0 ,0
Exp/Cntr=0.3,0.1

Type RM Length L Ch R = 1 ,45938.4 ,196.2,200.6,203.5
XS GIS Cut Line= 6
     1574884.657       395191.81     1574739.257      395081.133
     1574494.032        394872.8     1574396.375      394775.144
     1574355.143      394688.338     1574344.292      394595.022
#Sta/Elev= 30
       0  752.88     9.6  754.08    19.2  753.93    28.8   752.5    48.1  745.72
    57.7   743.8    67.3  743.31    86.6  741.97    96.2  742.14   105.8  742.84
   115.4  743.23   202.3  743.32   221.8  743.55     261  744.29   280.5  744.43
   300.1  744.42   314.3 744.086   329.3  743.66     350 743.539   387.7  743.38
     523  743.28   559.8  743.36   587.4  743.71   624.2  744.41   671.5  745.56
   709.9  747.09   738.8  748.51   776.3  749.64   804.5  750.66   832.7  751.06
#Mann= 3 , 0 , 0
       0     .06       0   314.3    .045       0     350     .06       0
Bank Sta=314.3,350
XS Rating Curve= 0 ,0
Exp/Cntr=0.3,0.1

Type RM Length L Ch R = 1 ,43686.2 ,127.4,125.5,124.2
XS GIS Cut Line= 5
     1575691.742      395729.513     1576113.653      394849.543
     1576294.379      394657.522     1576143.337      394285.126
     1576112.087       394037.73
#Sta/Elev= 30
       0  952.02    68.3   932.2   126.9  903.51   156.1  892.31   273.2  870.25
   312.3  866.05   419.6  860.34   487.9  864.75   556.3  854.44   595.3  852.39
   653.8  853.38   692.9  861.56   712.4  863.74   761.2  863.88   790.5  861.69
   888.1  848.27   927.1  839.65  1073.6   791.9  1141.9  764.96  1200.5     749
  1239.6  744.47  1357.2  738.39  1523.8  739.49  1553.2  734.31    1563  735.76
  1572.8  740.38  1592.4  747.45  1660.6  752.22  1785.3  773.58  1890.8  787.21
#Mann= 3 , 0 , 0
       0     .06       0  1523.8    .045       0  1572.8     .06       0
Bank Sta=1523.8,1572.8
XS Rating Curve= 0 ,0
Exp/Cntr=0.3,0.1

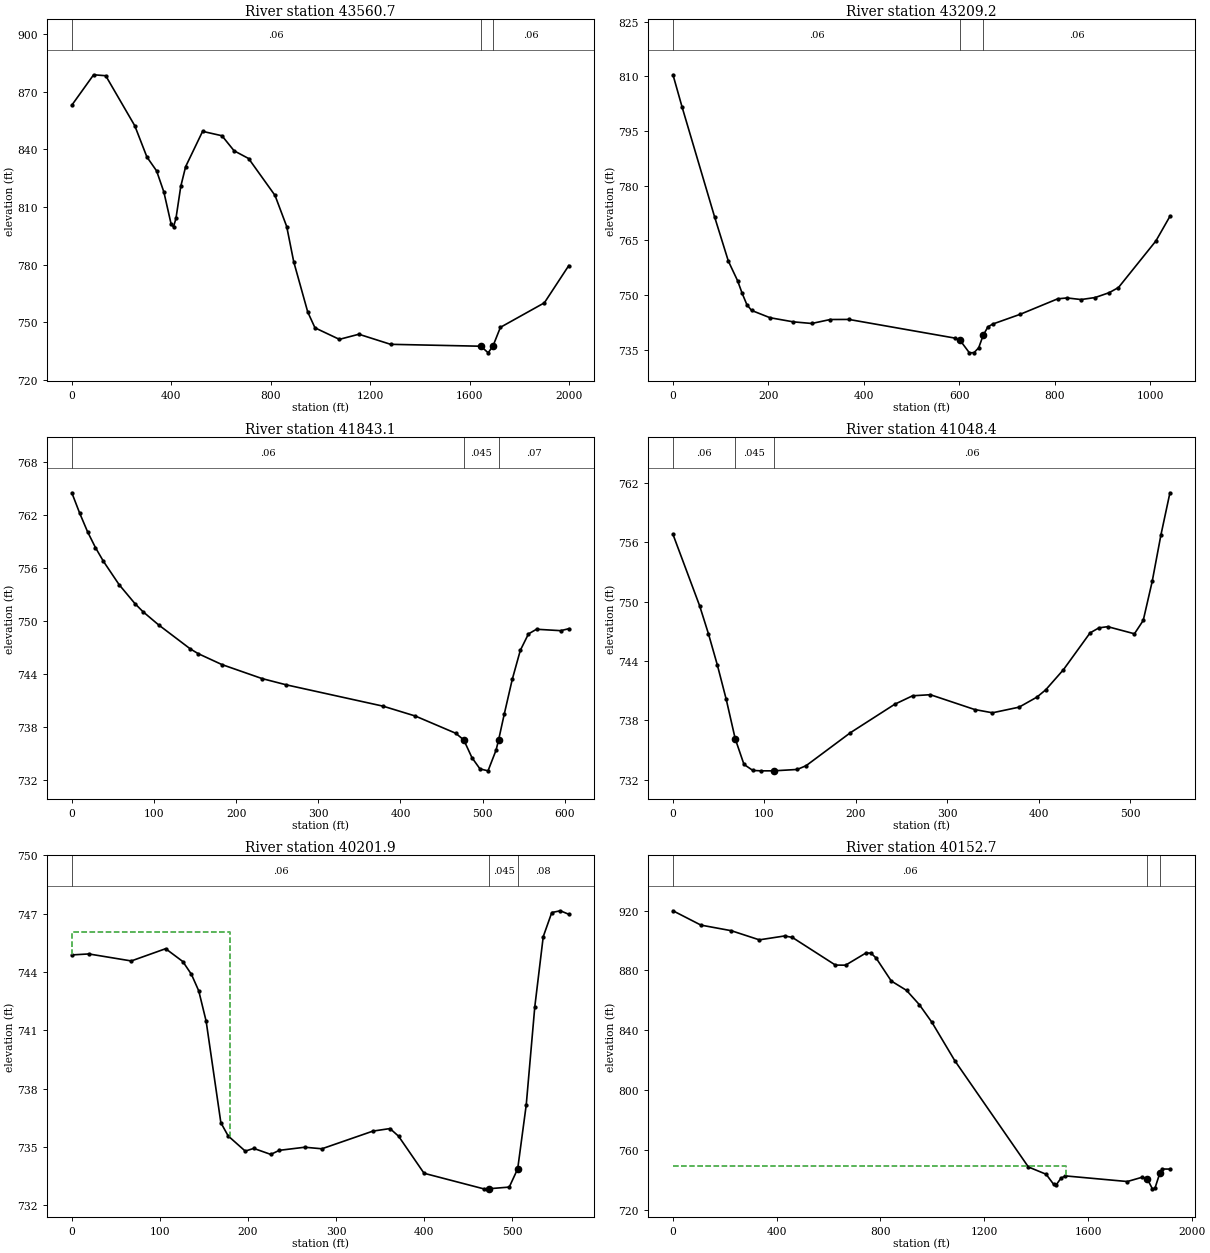
Type RM Length L Ch R = 1 ,43560.7 ,349.9,351.4,352.5
XS GIS Cut Line= 5
     1576980.805       395838.02     1576730.267      395090.022
     1576599.066      394983.043     1576263.834      394262.376
     1576229.112       394019.32
#Sta/Elev= 30
       0   862.9    87.6   878.7   136.3  878.21   253.2  852.19   301.9  835.97
   340.9  828.74   370.1  817.77   399.3   801.1     409  799.66   418.8  804.06
   438.2  820.73   457.7  830.95   525.9  849.29   603.8     847   652.5  839.19
   710.9  835.17   817.1  815.99   864.1  799.82   892.3  781.52   948.7  755.38
   977.8  747.15  1075.9  741.16  1154.4  743.82  1281.9  738.58    1645  737.59
  1674.4  734.15  1694.1  737.84  1723.5  747.41  1900.3  760.15  1998.5  779.52
#Mann= 3 , 0 , 0
       0     .06       0    1645    .045       0  1694.1     .06       0
Bank Sta=1645,1694.1
XS Rating Curve= 0 ,0
Exp/Cntr=0.3,0.1

Type RM Length L Ch R = 1 ,43209.2 ,549.7,550.3,549.2
XS GIS Cut Line= 4
     1576928.468       394887.39     1576831.246      394779.751
     1576598.607      394213.779     1576445.829      393974.196
#Sta/Elev= 30
       0  810.46    19.3   801.5      87  771.53     116  759.31   135.4  753.91
     145  750.44   154.8  747.36   164.5  745.78   203.3  743.77   251.9  742.64
   290.7  742.19   329.6  743.28   368.4   743.3   591.8  738.15   601.6  737.54
     621  734.13   630.7  734.19   640.4   735.5   650.1  739.03   659.8  741.26
   669.6  742.02   727.8  744.73     806  748.96   825.6   749.2     855  748.76
   884.3  749.31   913.7  750.64   933.3  752.06  1011.7  764.85  1041.1  771.61
#Mann= 3 , 0 , 0
       0     .06       0   601.6    .045       0   650.1     .06       0
Bank Sta=601.6,650.1
XS Rating Curve= 0 ,0
Exp/Cntr=0.3,0.1

Type RM Length L Ch R = 1 ,41843.1 ,213.1,209.7,206.1
XS GIS Cut Line= 3
     1577690.212      394305.959     1577604.275      394134.084
      1577463.65      393746.064
#Sta/Elev= 30
       0  764.53     9.6  762.21    19.2   760.1    28.8  758.31    38.4  756.77
    57.6  754.11    76.9  751.96    86.5  751.06   105.7  749.55   144.1  746.84
   153.7   746.3   182.6  745.06   231.5  743.47     261  742.76   378.9  740.34
   418.2  739.22   467.3  737.27   477.1  736.51     487  734.51   496.8  733.23
   506.6  733.01   516.4  735.36  519.57  736.56   526.3  739.42   536.1  743.38
   545.9  746.67   555.8  748.53   565.6  749.06     595   748.9   604.9  749.12
#Mann= 3 , 0 , 0
       0     .06       0   477.1    .045       0  519.57     .07       0
Bank Sta=477.1,519.57
XS Rating Curve= 0 ,0
Exp/Cntr=0.3,0.1

Type RM Length L Ch R = 1 ,41048.4 ,466.1,465.3,464.1
XS GIS Cut Line= 2
     1578281.358      393738.251     1577828.233      393438.772
#Sta/Elev= 30
       0  756.81    29.1   749.6    38.8  746.75    48.5   743.6    58.2  740.13
      68 736.153    77.6  733.55    87.3  732.94    96.3   732.9     110   732.9
   135.8  733.04   145.5  733.42     194  736.76   242.5  739.64   261.9  740.49
   281.3   740.6   329.8   739.1   349.2  738.77   378.3  739.34   397.7  740.35
   407.4  741.09   426.8  743.13   455.9  746.85   465.6  747.36   475.2  747.48
   504.4  746.76     514  748.11   523.8  752.05   533.4  756.78   543.2  761.02
#Mann= 3 , 0 , 0
       0     .06       0      68    .045       0     110     .06       0
Bank Sta=68,110
XS Rating Curve= 0 ,0
Exp/Cntr=0.3,0.1

Type RM Length L Ch R = 1 ,40201.9 ,49.3,49.3,49.3
XS GIS Cut Line= 5
     1578496.202      393247.366     1578524.848      393175.751
     1578522.243      393117.157     1578519.639      393075.491
     1578155.056      392946.584
#Sta/Elev= 30
       0  744.87    19.3  744.92    67.5  744.56   106.5  745.19     126  744.53
   135.8  743.87   144.1  743.02   152.5  741.46   169.2  736.24   177.5  735.56
   196.9  734.78   206.5  734.92   225.9  734.61   235.5  734.82   264.5  734.98
   283.9   734.9   341.9  735.81   361.2  735.94   370.9  735.55   399.9  733.64
   467.6  732.84     474 732.847   496.6  732.93   506.2  733.87   515.9  737.16
   525.6   742.2   535.2  745.81   544.9  747.05   554.6  747.14   564.2  746.96
#Mann= 3 , 0 , 0
       0     .06       0     474    .045       0   506.2     .08       0
#XS Ineff= 2 , 0
          179.75  746.05
Permanent Ineff=
       F       F
Bank Sta=474,506.2
XS Rating Curve= 0 ,0
Exp/Cntr=0.3,0.1

Type RM Length L Ch R = 1 ,40152.7 ,124,126.5,128.5
XS GIS Cut Line= 5
     1578860.145      394527.256     1578548.285      393132.782
     1578545.681      393074.189     1578543.077      393032.522
     1578178.493      392903.616
#Sta/Elev= 30
       0   919.9   107.7  910.32   225.1  906.56   332.8  900.46   430.6  903.06
     460   902.1   626.4  883.57   665.5  883.52   743.8  891.66   763.4  891.59
     783  888.31   841.7  872.92   900.4  866.67   949.4   857.2   998.3  845.31
  1086.4  819.66  1370.2  748.55  1438.7  743.66    1468  736.84  1477.8  736.66
  1495.9  741.03  1512.6  742.57  1751.7   738.8  1809.7  741.71    1829  740.45
  1848.4  733.91    1858  734.19  1877.4  744.62    1887  747.18    1916  747.12
#Mann= 3 , 0 , 0
       0     .06       0    1829    .045       0  1877.4     .08       0
#XS Ineff= 2 , 0
         1515.57  749.31
Permanent Ineff=
       F       F
Bank Sta=1829,1877.4
XS Rating Curve= 0 ,0
Exp/Cntr=0.3,0.1

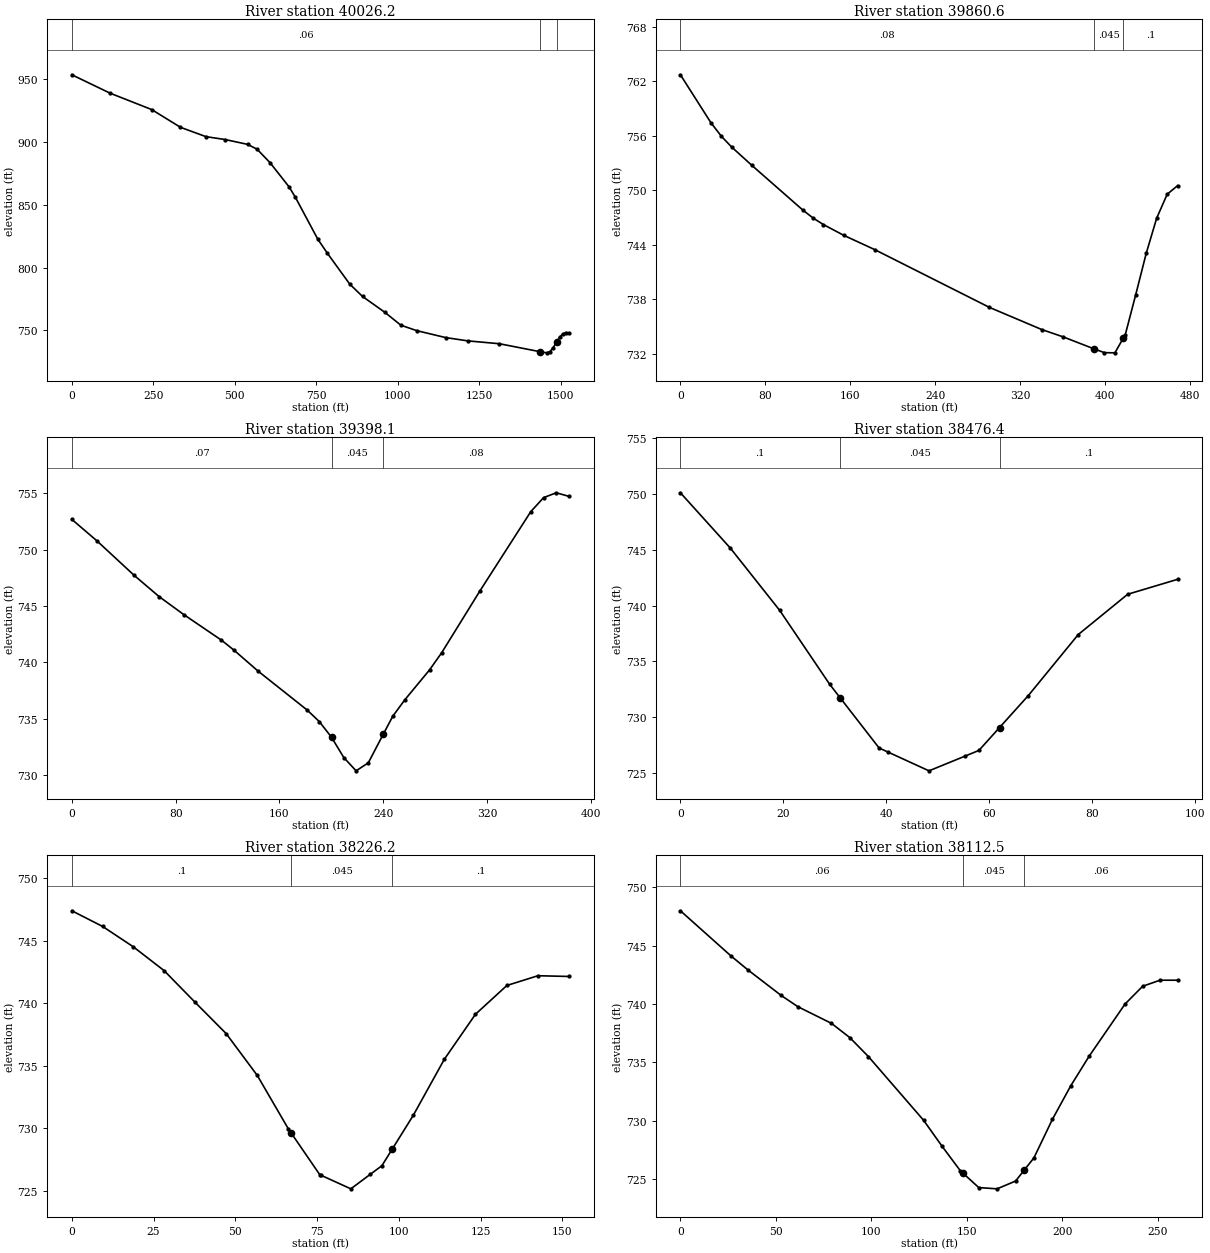
Type RM Length L Ch R = 1 ,40026.2 ,164.8,165.6,166.5
XS GIS Cut Line= 3
     1579736.881      392951.735     1578580.512      392946.584
      1578246.31      392790.334
#Sta/Elev= 30
       0  953.42   117.6  938.75     245  925.74   333.2  911.63   411.6  904.18
   470.4  901.89     539  898.06   568.4  894.18   607.6   883.6   666.4  864.27
     686  855.84   754.6  822.59     784   811.4   852.6  786.85   891.8  777.03
   960.4  764.38  1009.4  754.15  1058.4   749.8  1146.6  744.32  1214.6  741.69
  1311.7  739.41  1437.8 732.996  1457.3  732.16    1467  733.12  1476.8  736.28
  1487.8 741.135  1496.2  744.46  1505.9  747.16  1515.6  748.21  1525.3   748.1
#Mann= 3 , 0 , 0
       0     .06       0  1437.8    .045       0  1487.8      .1       0
Bank Sta=1437.8,1487.8
XS Rating Curve= 0 ,0
Exp/Cntr=0.3,0.1

Type RM Length L Ch R = 1 ,39860.6 ,460.4,462.5,464.6
XS GIS Cut Line= 3
     1578764.973      392744.762     1578584.852      392775.144
     1578330.946      392644.935
#Sta/Elev= 23
       0  762.74    28.8  757.44    38.5  755.97    48.1  754.79    67.3  752.75
   115.4  747.81     125  746.94   134.6  746.23   153.8  745.04   182.7  743.48
   290.9   737.1   340.1  734.66   359.8  733.87     389 732.544   399.1  732.11
     409  732.09     417 733.739   418.8  734.11   428.6   738.5   438.5  743.07
   448.3  746.93   458.2  749.57     468  750.52
#Mann= 3 , 0 , 0
       0     .08       0     389    .045       0     417      .1       0
Bank Sta=389,417
XS Rating Curve= 0 ,0
Exp/Cntr=0.3,0.1

Type RM Length L Ch R = 1 ,39398.1 ,435.2,423.1,411
XS GIS Cut Line= 4
     1578797.526      392473.494     1578758.463      392364.987
     1578615.234      392273.841     1578526.258      392232.609
#Sta/Elev= 24
       0  752.68    19.2  750.79      48  747.72    67.3  745.83    86.5  744.22
   115.3  741.97   124.8   741.1   143.6  739.22   181.4  735.77   190.8  734.74
   200.2  733.35   209.6  731.56   219.1  730.38   228.5  731.09     240 733.618
   247.4  735.23   256.8   736.7   275.7  739.33   285.1  740.86   314.5  746.33
   353.7  753.36   363.6  754.61   373.4  755.04   383.2  754.72
#Mann= 3 , 0 , 0
       0     .07       0   200.2    .045       0     240     .08       0
Bank Sta=200.2,240
XS Rating Curve= 0 ,0
Exp/Cntr=0.3,0.1

Type RM Length L Ch R = 1 ,38476.4 ,251,250.2,249.5
XS GIS Cut Line= 2
     1578733.959      391459.316     1578637.387      391458.231
#Sta/Elev= 15
       0  750.12     9.7  745.16    19.3  739.57      29  732.95      31  731.76
    38.6  727.24    40.3  726.88    48.3  725.19    55.3  726.51      58  727.02
      62  729.07    67.6  731.94    77.3  737.41    86.9  741.02    96.6  742.36
#Mann= 3 , 0 , 0
       0      .1       0      31    .045       0      62      .1       0
Bank Sta=31,62
XS Rating Curve= 0 ,0
Exp/Cntr=0.3,0.1

Type RM Length L Ch R = 1 ,38226.2 ,92.6,113.7,132.1
XS GIS Cut Line= 3
     1578752.405      391239.047     1578731.788       391207.58
     1578617.406      391210.108
#Sta/Elev= 21
       0  747.39     9.4  746.14    18.8  744.51    28.2  742.61    37.6   740.1
    47.2  737.57    56.7  734.23    66.2  729.96      67 729.655    75.8   726.3
    76.3  726.24    85.3  725.17    91.3  726.34    94.8  727.02      98 728.363
   104.4  731.05   113.9  735.53   123.4  739.12     133  741.42   142.5   742.2
     152  742.14
#Mann= 3 , 0 , 0
       0      .1       0      67    .045       0      98      .1       0
Bank Sta=67,98
XS Rating Curve= 0 ,0
Exp/Cntr=0.3,0.1

Type RM Length L Ch R = 1 ,38112.5 ,102.4,97.3,94.2
XS GIS Cut Line= 4
      1578793.74      391222.434     1578750.772      391156.028
     1578650.511      391051.862     1578613.934      391050.386
#Sta/Elev= 24
       0  747.99    26.4  744.13    35.2  742.94    52.7  740.74    61.5  739.77
    79.1  738.34    88.7  737.12    98.4   735.5   127.3  730.04   136.9  727.83
   146.6   725.7     148 725.492   156.2  724.27   165.8  724.16   175.5  724.83
     180 725.763   185.1  726.82   194.8  730.13   204.4     733     214  735.53
   232.8     740     242  741.52   251.1  742.04   260.3  742.04
#Mann= 3 , 0 , 0
       0     .06       0     148    .045       0     180     .06       0
Bank Sta=148,180
XS Rating Curve= 0 ,0
Exp/Cntr=0.3,0.1

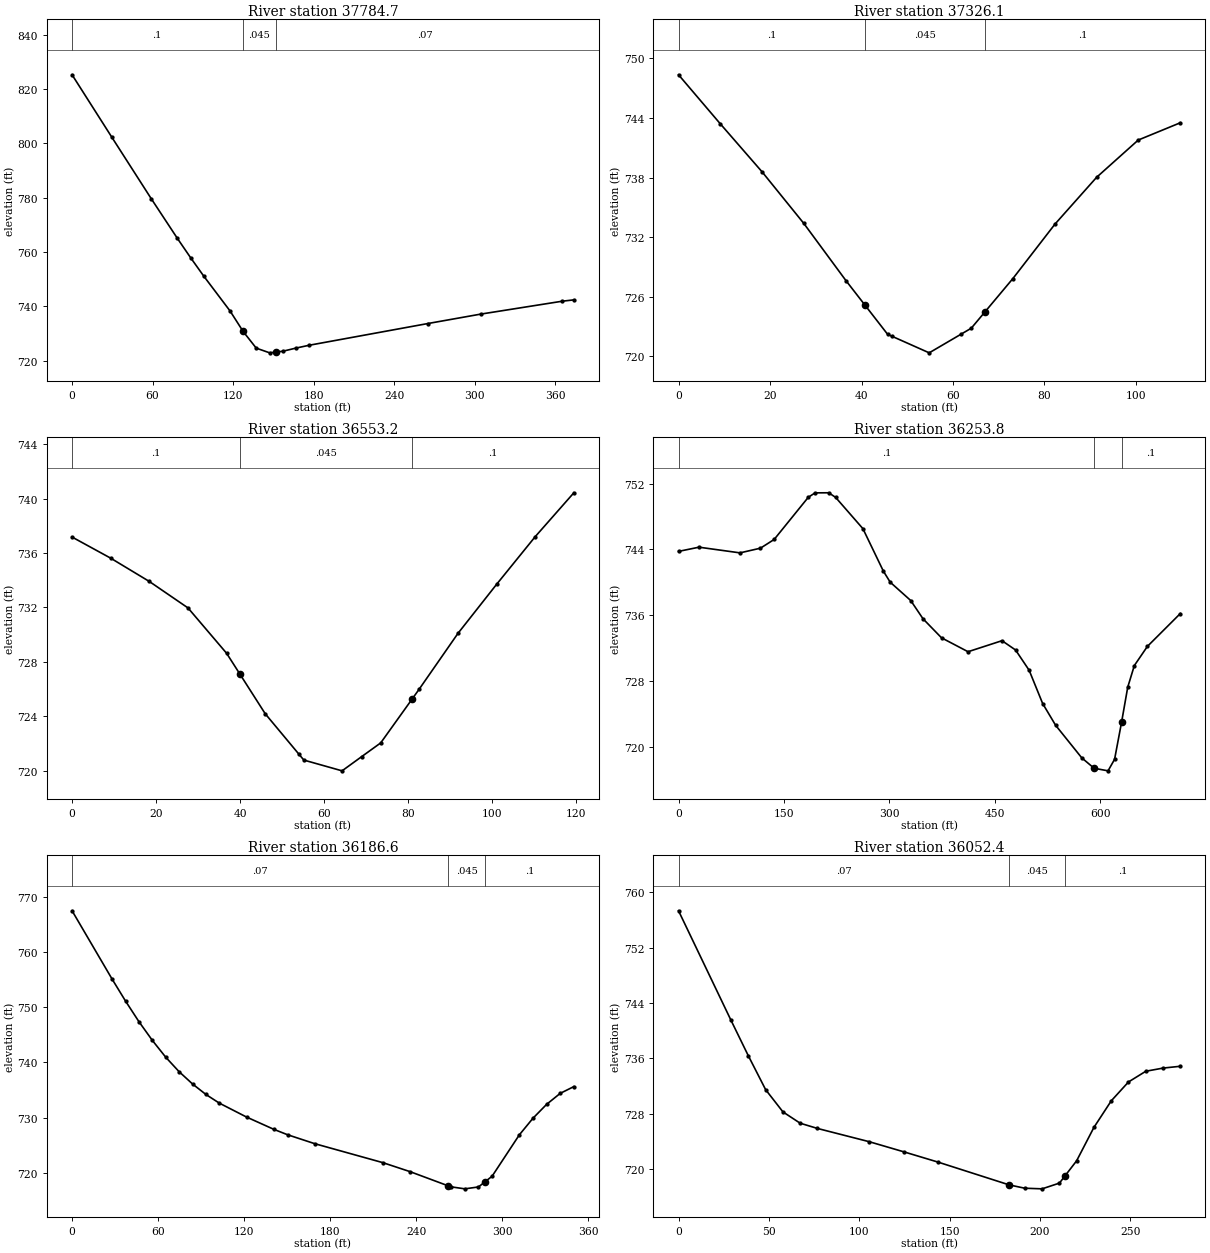
Type RM Length L Ch R = 1 ,37784.7 ,256.7,262.4,266.6
XS GIS Cut Line= 4
     1578987.194      390765.707     1578885.868      390825.635
     1578692.726      390861.443     1578633.047      390861.443
#Sta/Elev= 19
       0  825.26    29.4  802.45    58.9  779.72    78.5  765.02    88.3  757.95
    98.1  751.17   117.7  738.34     127 731.147   127.5  730.76   137.2  724.67
   147.2  722.94   152.2  723.24     157  723.53   166.8  724.69   176.6  725.73
     265  733.72   304.3  737.18   365.3  741.95   373.8  742.43
#Mann= 3 , 0 , 0
       0      .1       0     127    .045       0   152.2     .07       0
Bank Sta=127,152.2
XS Rating Curve= 0 ,0
Exp/Cntr=0.3,0.1

Type RM Length L Ch R = 1 ,37326.1 ,373.3,375.6,378.1
XS GIS Cut Line= 2
     1578817.509      390450.201     1578718.768      390402.458
#Sta/Elev= 17
       0  748.35     9.1  743.43    18.3  738.56    27.4  733.38    36.6  727.63
    40.7 725.197    45.7  722.23    46.7  722.02    54.8  720.36    61.7  722.22
      64  722.84      67 724.488    73.1  727.84    82.3  733.32    91.4  738.03
   100.5  741.78   109.7  743.52
#Mann= 3 , 0 , 0
       0      .1       0    40.7    .045       0      67      .1       0
Bank Sta=40.7,67
XS Rating Curve= 0 ,0
Exp/Cntr=0.3,0.1

Type RM Length L Ch R = 1 ,36553.2 ,52.5,221.1,244.3
XS GIS Cut Line= 2
     1579193.377      389786.139     1579094.636      389718.865
#Sta/Elev= 18
       0  737.17     9.2  735.62    18.4  733.91    27.6  731.97    36.8  728.64
      40 727.096      46   724.2      54  721.24    55.2   720.8    64.3  720.01
      69  721.06    73.5  722.06      81 725.288    82.7  726.02    91.9   730.1
   101.1   733.7   110.3   737.2   119.5  740.42
#Mann= 3 , 0 , 0
       0      .1       0      40    .045       0      81      .1       0
Bank Sta=40,81
XS Rating Curve= 0 ,0
Exp/Cntr=0.3,0.1

Type RM Length L Ch R = 1 ,36253.8 ,81.5,67.2,53.5
XS GIS Cut Line= 6
     1579546.025      389916.347     1579254.115      389762.076
     1579244.739      389710.283     1579280.183      389579.976
     1579280.183      389543.083     1579258.481      389385.748
#Sta/Elev= 30
       0  743.76    29.1  744.27    87.4  743.58   116.5  744.15     136  745.21
   184.5  750.33   194.2  750.87   213.6  750.88   223.4  750.32   262.2  746.52
   291.3  741.36     301  740.02   330.2  737.79   347.7  735.57     374  733.26
   411.7  731.57     460  732.91   479.3  731.78   498.6  729.32   517.8  725.28
   536.3  722.63   573.4  718.68     591 717.414   610.8   717.1   620.1   718.5
     630 722.983   638.8  727.26   648.2  729.89   666.8  732.22   713.6  736.21
#Mann= 3 , 0 , 0
       0      .1       0     591    .045       0     630      .1       0
Bank Sta=591,630
XS Rating Curve= 0 ,0
Exp/Cntr=0.3,0.1

Type RM Length L Ch R = 1 ,36186.6 ,134.3,134.2,134.7
XS GIS Cut Line= 3
     1579530.834      389599.507     1579431.007      389575.635
     1579271.502      389386.833
#Sta/Elev= 27
       0  767.42      28  755.03    37.3  751.09    46.6  747.38      56  743.98
    65.3  740.95    74.6  738.34      84  736.11    93.3  734.22   102.6  732.66
   121.6  730.14   140.7  727.91   150.2  726.94   169.2  725.32   216.7  721.89
   235.7  720.26     262 717.722   264.2  717.52   273.8  717.16   283.3   717.5
     288 718.459   292.8  719.44   311.8  726.92   321.3  729.92   330.8  732.43
   340.3  734.42   349.8  735.64
#Mann= 3 , 0 , 0
       0     .07       0     262    .045       0     288      .1       0
Bank Sta=262,288
XS Rating Curve= 0 ,0
Exp/Cntr=0.3,0.1

Type RM Length L Ch R = 1 ,36052.4 ,213.5,190.8,167.6
XS GIS Cut Line= 3
     1579544.939      389482.319     1579503.707      389457.363
     1579356.137      389281.582
#Sta/Elev= 22
       0  757.33    28.9  741.57    38.6  736.38    48.2  731.47    57.8  728.25
    67.3  726.62    76.9  725.86   105.6  723.94   124.7  722.48   143.8  720.98
     183   717.7   191.6  717.22   201.2  717.13   210.8  717.96     214 719.045
   220.3  721.18   229.9  726.02   239.5  729.86     249  732.58   258.6  734.13
   268.2  734.59   277.7  734.85
#Mann= 3 , 0 , 0
       0     .07       0     183    .045       0     214      .1       0
Bank Sta=183,214
XS Rating Curve= 0 ,0
Exp/Cntr=0.3,0.1

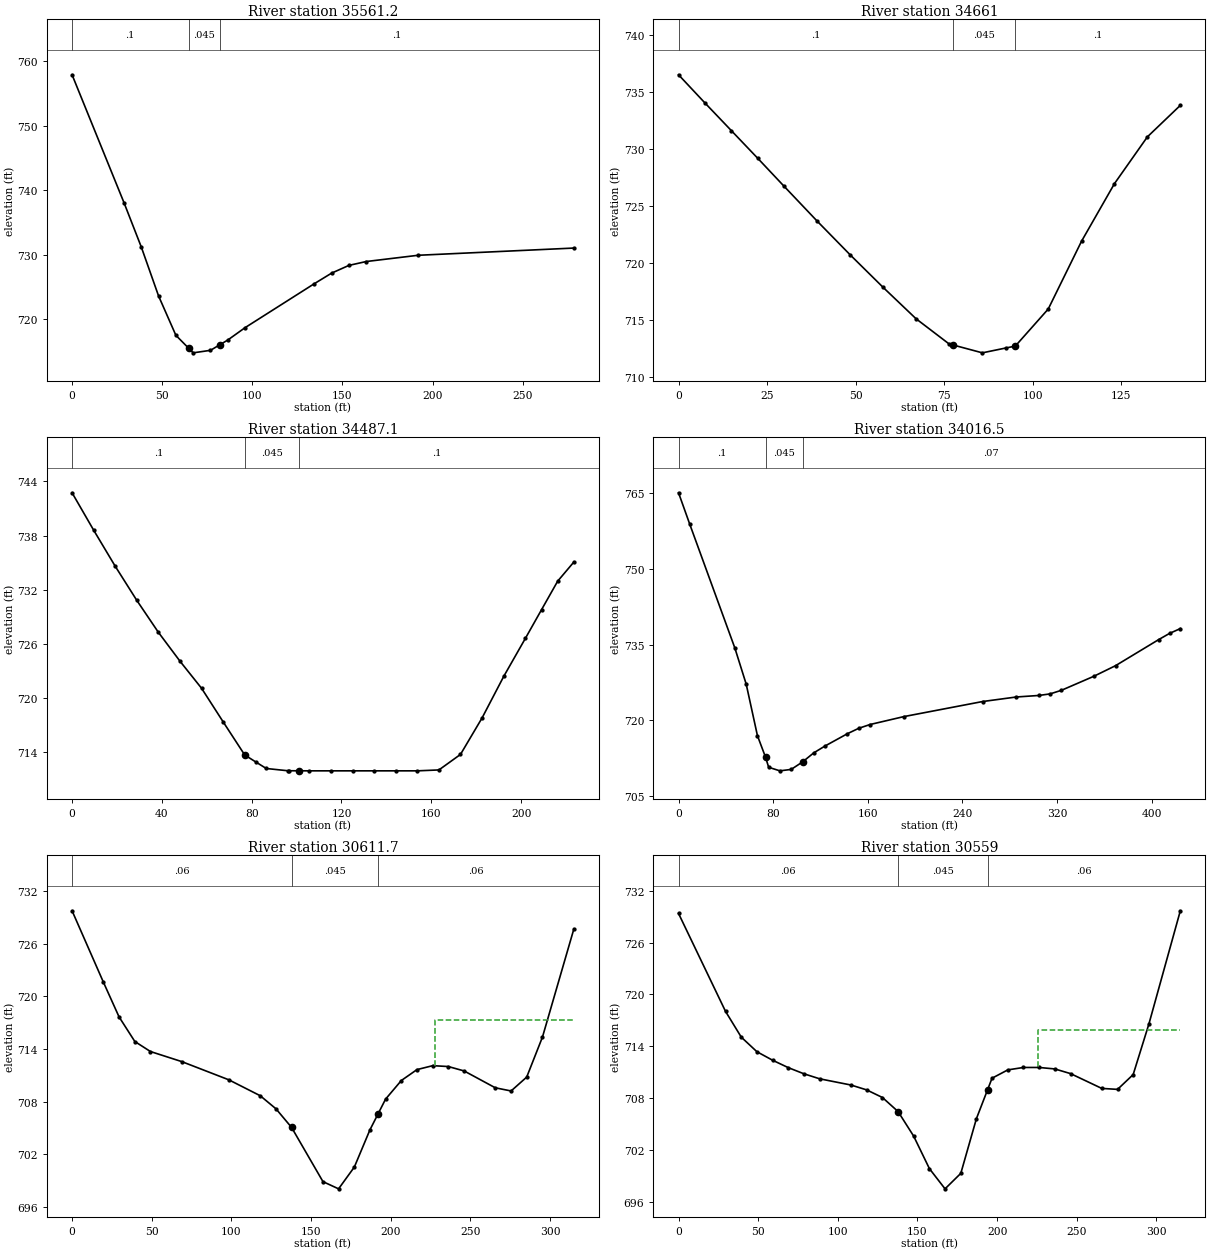
Type RM Length L Ch R = 1 ,35561.2 ,212,209.4,206.9
XS GIS Cut Line= 2
     1579383.264      388876.851     1579187.572      389074.919
#Sta/Elev= 17
       0  757.89    28.8  738.05    38.4  731.17      48  723.56    57.6  717.46
    64.6  715.48    67.2  714.74    76.8  715.13      82 715.999    86.4  716.73
      96  718.65   134.4  725.47     144  727.11   153.6  728.31   163.2  728.91
     192  729.88   278.4     731
#Mann= 3 , 0 , 0
       0      .1       0    64.6    .045       0      82      .1       0
Bank Sta=64.6,82
XS Rating Curve= 0 ,0
Exp/Cntr=0.3,0.1

Type RM Length L Ch R = 1 ,34661   ,169.1,173.9,178.2
XS GIS Cut Line= 3
     1579105.486      388105.366     1579076.189      388099.941
     1578966.597      388122.727
#Sta/Elev= 20
       0  736.51     7.4  734.06    14.9  731.62    22.4  729.18    29.8  726.74
    39.1   723.7    48.4  720.75    57.8  717.87    67.1  715.12    76.4  712.92
    77.5  712.83    85.8  712.14    92.5  712.57      95 712.724    95.1  712.73
   104.4  715.98   113.8  721.92   123.1  726.97   132.4  731.07   141.7  733.83
#Mann= 3 , 0 , 0
       0      .1       0    77.5    .045       0      95      .1       0
Bank Sta=77.5,95
XS Rating Curve= 0 ,0
Exp/Cntr=0.3,0.1

Type RM Length L Ch R = 1 ,34487.1 ,232.8,232.6,232.3
XS GIS Cut Line= 3
     1579141.294      387942.606     1578939.471      387946.946
     1578918.854      387953.457
#Sta/Elev= 29
       0  742.74     9.6   738.6    19.2   734.6    28.8  730.82    38.4  727.28
    48.1  724.05    57.7  721.05    67.3  717.33    76.9  713.66      77 713.644
    81.8  712.89    86.5  712.16    96.1  711.91    96.8  711.91     101 711.905
   105.7   711.9   115.4   711.9     125   711.9   134.6   711.9   144.2   711.9
   153.8   711.9   163.4     712     173  713.72   182.6  717.76   192.3  722.39
   201.9  726.59   209.1  729.77   216.3  732.94   223.5  735.06
#Mann= 3 , 0 , 0
       0      .1       0      77    .045       0     101      .1       0
Bank Sta=77,101
XS Rating Curve= 0 ,0
Exp/Cntr=0.3,0.1

Type RM Length L Ch R = 1 ,34016.5 ,238.4,230,221.3
XS GIS Cut Line= 4
     1579131.528      387465.175     1579090.295      387489.047
     1578820.113       387545.47     1578725.712      387580.193
#Sta/Elev= 26
       0  764.98     9.5  758.76    47.6  734.32    57.2  727.18    66.7     717
   73.52  712.76    76.2  710.75    85.7  710.05    95.2  710.33   104.8   711.8
   114.3   713.6   123.8  714.95   142.8  717.39   152.3  718.45   161.9   719.2
   190.4  720.76     257  723.74   285.6  724.64   304.6  724.94   314.1  725.25
   323.7  725.96   351.1  728.73   369.4  730.82     406  735.99   415.1   737.2
   424.2  738.15
#Mann= 3 , 0 , 0
       0      .1       0   73.52    .045       0   104.8     .07       0
Bank Sta=73.52,104.8
XS Rating Curve= 0 ,0
Exp/Cntr=0.3,0.1

Type RM Length L Ch R = 1 ,30611.7 ,52.7,52.6,52.6
XS GIS Cut Line= 2
      1579272.11      385012.933     1578992.162      385157.247
#Sta/Elev= 26
       0  729.73    19.7  721.59    29.5  717.65    39.4  714.85    49.2  713.71
    68.9  712.56    98.4  710.49   118.1  708.68     128  707.19   137.8  705.07
   157.5   698.9   167.3  698.08   177.2  700.56     187   704.8     192 706.581
   196.8  708.29   206.7  710.41   216.5  711.65   226.4   712.1   236.2     712
   246.1   711.5   265.7  709.58   275.6  709.22   285.4   710.8   295.3  715.36
     315  727.66
#Mann= 3 , 0 , 0
       0     .06       0   137.8    .045       0     192     .06       0
#XS Ineff= 2 , 0
                          228.05          717.34
Permanent Ineff=
       F       F
Bank Sta=137.8,192
XS Rating Curve= 0 ,0
Exp/Cntr=0.3,0.1

Type RM Length L Ch R = 1 ,30559   ,112.2,111.6,110.9
XS GIS Cut Line= 2
     1579247.153       384967.36     1578967.205      385111.674
#Sta/Elev= 29
       0  729.36    29.5  718.05    39.4  715.07    49.2  713.39      59  712.41
    68.9  711.55    78.7  710.84    88.6  710.26   108.3  709.54   118.1  708.98
     128   708.1   137.8  706.48   147.6  703.64   157.5  699.88   167.3  697.55
   177.2  699.34     187  705.66     194 708.996   196.8  710.33   206.7  711.29
   216.5  711.57   226.4  711.57   236.2   711.4   246.1  710.86   265.7  709.15
   275.6  709.04   285.4  710.75   295.3  716.61     315  729.67
#Mann= 3 , 0 , 0
       0     .06       0   137.8    .045       0     194     .06       0
#XS Ineff= 2 , 0
                          225.81          715.88
Permanent Ineff=
       F       F
Bank Sta=137.8,194
XS Rating Curve= 0 ,0
Exp/Cntr=0.3,0.1