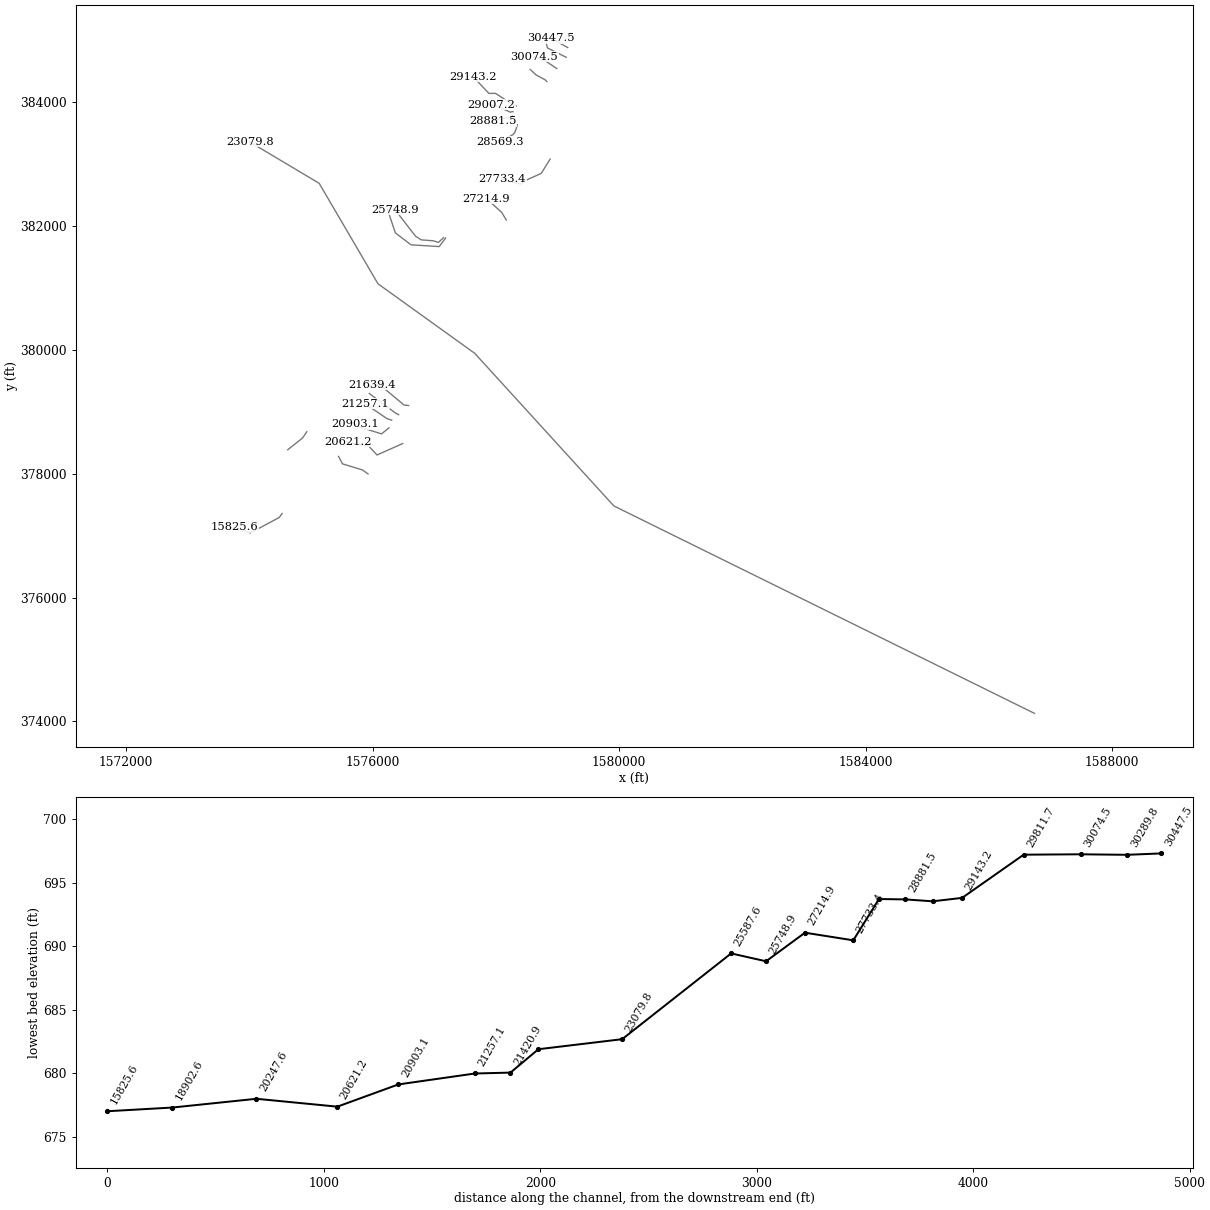
HEC-RAS study PTPLSCRK.prj: PTPLSCRK

--- PTPLSCRK.g02 (geometry) --- (continued)

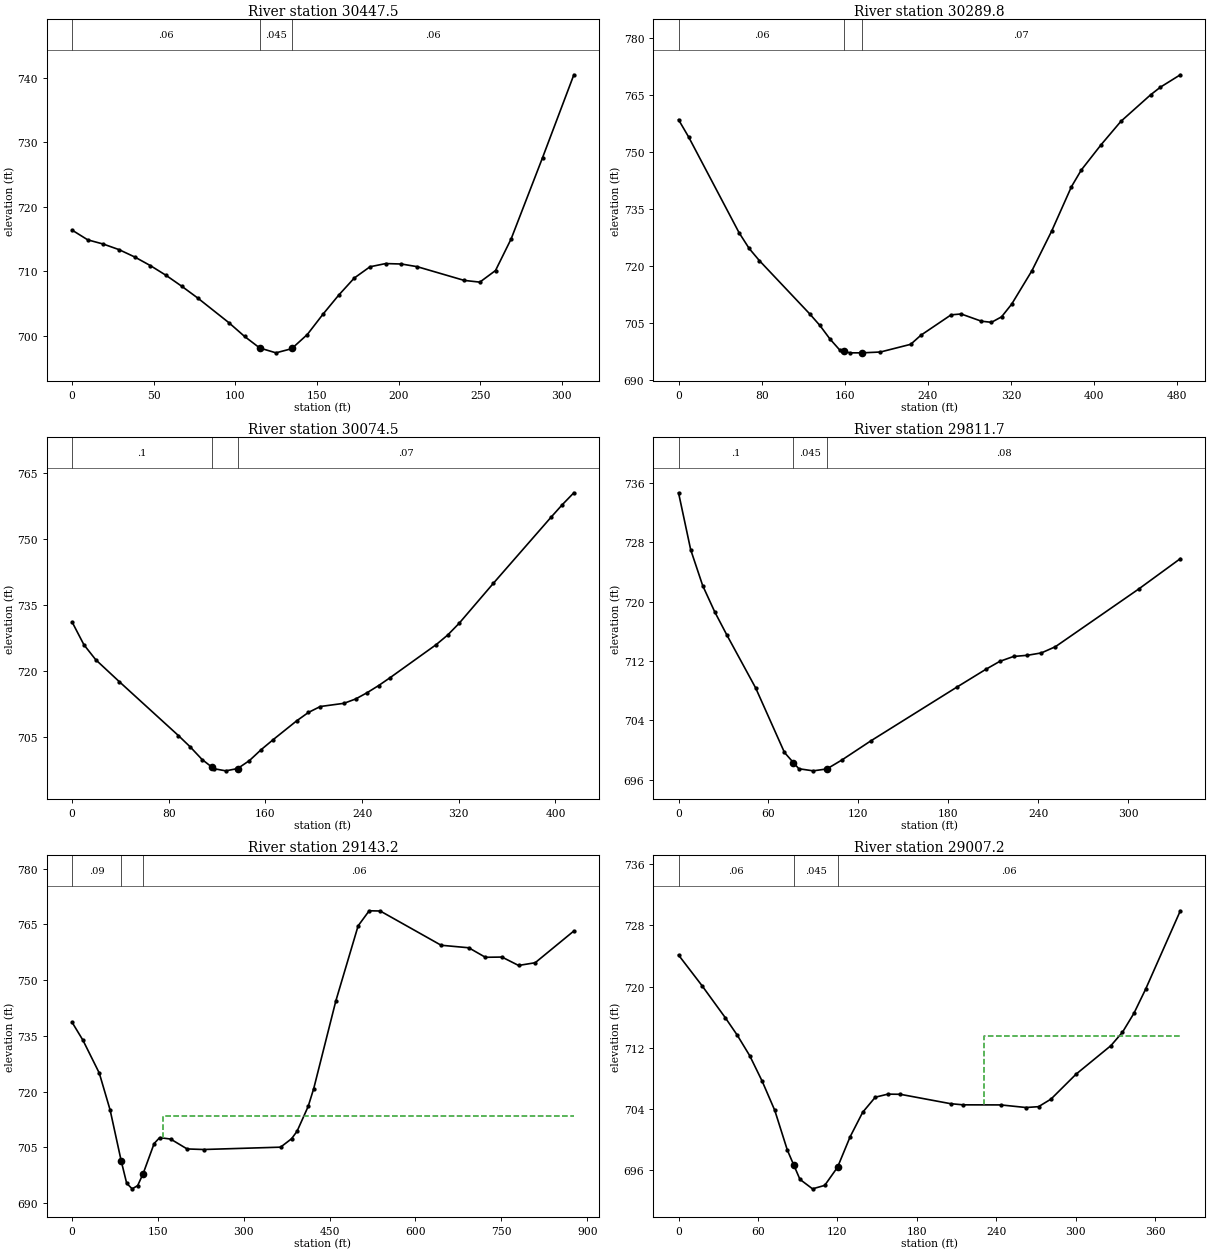
Type RM Length L Ch R = 1 ,30447.5 ,156.6,157.7,158.6
XS GIS Cut Line= 2
     1579164.688      384880.554     1578895.591      385029.209
#Sta/Elev= 29
       0  716.35     9.6  714.84    19.2  714.18    28.8  713.32    38.4  712.18
      48  710.84    57.6  709.33    67.2  707.64    76.9  705.83    96.1  701.98
   105.7  699.85     115 698.058   124.9  697.31   134.5  697.95     135  698.06
   144.1  700.15   153.7   703.3   163.3  706.25   172.9  708.92   182.5  710.66
   192.1  711.16   201.8  711.09   211.4  710.68   240.2  708.55   249.8  708.28
   259.4  710.08     269     715   288.2  727.58   307.4  740.45
#Mann= 3 , 0 , 0
       0     .06       0     115    .045       0     135     .06       0
Bank Sta=115,135
XS Rating Curve= 0 ,0
Exp/Cntr=0.3,0.1

Type RM Length L Ch R = 1 ,30289.8 ,218.1,215.3,212.3
XS GIS Cut Line= 3
     1579140.816      384723.219     1578835.912      384874.044
     1578802.275      385012.933
#Sta/Elev= 30
       0  758.45     9.7  753.92    58.3  728.75      68  724.62    77.8  721.44
   126.4   707.4   136.1  704.39   145.8  700.83   155.5  697.85   159.7  697.57
   165.2   697.2     177   697.2   194.4  697.42   223.5  699.44   233.3  701.82
   262.4  707.18   272.1  707.41   291.6  705.51   301.3  705.22     311  706.66
   320.7  709.98   340.2  718.76   359.2  729.17   378.3  740.86   387.8  745.25
   406.9   751.9   425.9  758.02   454.5  764.99     464  767.01   483.1  770.25
#Mann= 3 , 0 , 0
       0     .06       0   159.7    .045       0     177     .07       0
Bank Sta=159.7,177
XS Rating Curve= 0 ,0
Exp/Cntr=0.3,0.1

Type RM Length L Ch R = 1 ,30074.5 ,260.8,262.9,264.9
XS GIS Cut Line= 3
     1578986.736      384542.013     1578791.424      384672.221
     1578621.068        384731.9
#Sta/Elev= 29
       0  731.06     9.8  725.88    19.6  722.47    39.1  717.49      88  705.25
    97.8  702.67   107.6  699.81     116 698.019   117.4  697.72   127.2  697.24
     137 697.759   146.7  699.56   156.5  702.06   166.3   704.3   185.8  708.59
   195.6  710.51   205.4  711.85     225  712.58   234.7  713.57   244.2     715
   253.7  716.62   263.2  718.41   301.2  725.89   310.7  728.06   320.2  730.73
   348.7  739.87   396.2  754.81   405.7  757.72   415.2   760.4
#Mann= 3 , 0 , 0
       0      .1       0     116    .045       0     137     .07       0
Bank Sta=116,137
XS Rating Curve= 0 ,0
Exp/Cntr=0.3,0.1

Type RM Length L Ch R = 1 ,29811.7 ,296.2,284.5,272.9
XS GIS Cut Line= 4
     1578825.061      384332.594      1578803.36      384356.466
      1578651.45      384438.931     1578555.964      384526.822
#Sta/Elev= 22
       0  734.65     8.1  726.99    16.1  722.16    24.2   718.6    32.3  715.48
    51.5  708.36    70.7  699.68    76.7  698.31    80.3  697.49    89.9  697.21
      99 697.466   109.1  698.68   128.3  701.24   185.9   708.5   205.1  710.88
   214.4  711.95   223.6  712.61   232.9  712.77   242.2  713.09   251.5  713.92
   307.1  721.69   334.9  725.78
#Mann= 3 , 0 , 0
       0      .1       0    76.7    .045       0      99     .08       0
Bank Sta=76.7,99
XS Rating Curve= 0 ,0
Exp/Cntr=0.3,0.1

Type RM Length L Ch R = 1 ,29143.2 ,132.4,136,139.5
XS GIS Cut Line= 5
     1578329.184      383936.544      1578268.42      383963.671
     1577993.898      384140.537     1577887.253      384139.593
     1577626.821      384412.148
#Sta/Elev= 30
       0  738.65      19  733.82    47.5  724.99    66.5  715.02      86 701.224
    95.4  695.31     105  693.81   114.6  694.68   124.2  697.92   143.4  706.01
     153   707.6   172.2  707.21     201  704.55   229.8   704.4   364.3  705.03
   383.5   707.3   393.1  709.32   412.5     716   422.2   720.8     461  744.49
   499.8  764.62   519.1  768.67   538.4  768.61   644.8  759.39   693.1  758.71
   722.1  756.15   751.1  756.21   780.1  753.95   809.1  754.68   876.7  763.23
#Mann= 3 , 0 , 0
       0     .09       0      86    .045       0   124.2     .06       0
#XS Ineff= 2 , 0
                          159.35          713.33
Permanent Ineff=
       F       F
Bank Sta=86,124.2
XS Rating Curve= 0 ,0
Exp/Cntr=0.3,0.1

Type RM Length L Ch R = 1 ,29007.2 ,111.5,125.7,139.3
XS GIS Cut Line= 4
     1578276.016      383846.483     1578232.613      383837.803
     1577998.238      383940.884     1577921.198       383957.16
#Sta/Elev= 30
       0  724.13    17.7  720.13    35.4  715.91    44.3  713.66    53.8  710.95
    63.2  707.61    72.7   703.8    82.2   698.6      87  696.67    91.7  694.78
   101.2  693.54   110.4  693.99   120.1  696.37   129.6  700.35   139.1  703.56
   148.6  705.53   158.1  705.93   167.5  705.91   205.5  704.68     215  704.53
   243.4  704.52   262.4  704.18   271.9  704.29   281.3  705.28   300.3  708.55
   326.6  712.28   335.3  714.03     344  716.52   352.8  719.67     379  729.92
#Mann= 3 , 0 , 0
       0     .06       0      87    .045       0   120.1     .06       0
#XS Ineff= 2 , 0
                          230.88          713.53
Permanent Ineff=
       F       F
Bank Sta=87,120.1
XS Rating Curve= 0 ,0
Exp/Cntr=0.3,0.1

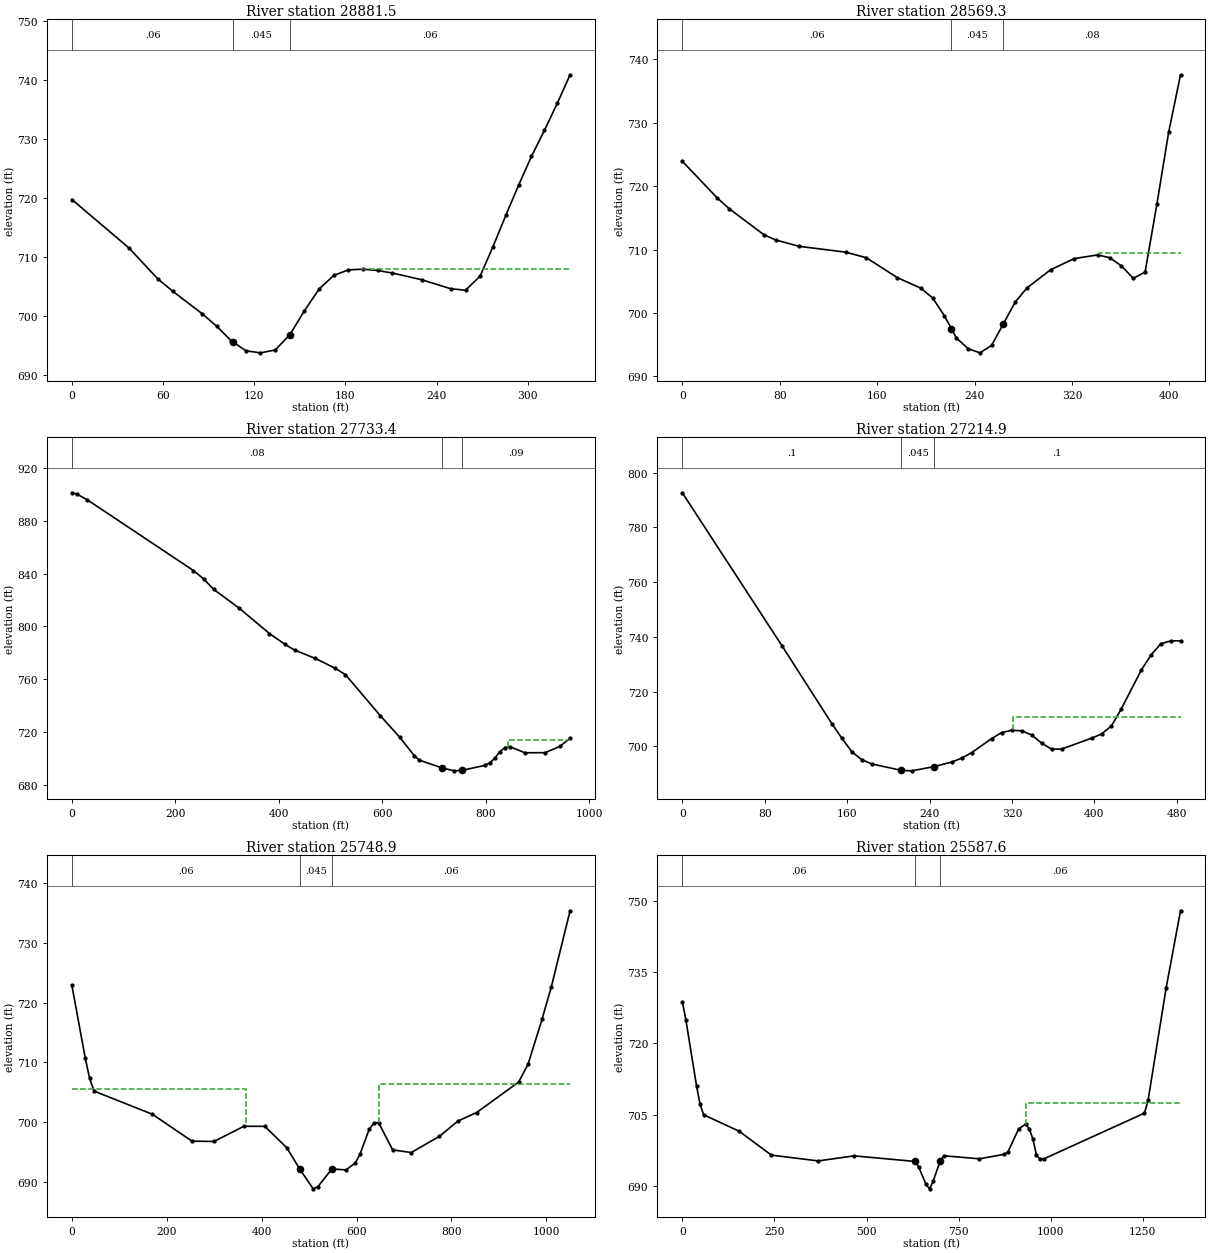
Type RM Length L Ch R = 1 ,28881.5 ,118.6,122.1,126.2
XS GIS Cut Line= 4
     1578269.505      383771.613     1578234.783      383757.508
     1578008.004       383713.02      1577953.75      383689.148
#Sta/Elev= 30
       0  719.69    37.5  711.49    56.7  706.19    66.4  704.13    85.6  700.35
    95.2  698.22   104.9  695.72     106 695.528   114.5  694.04   124.1  693.69
   133.8  694.17   143.4  696.75     153  700.83   162.7  704.52   172.3  706.82
   181.9  707.76   191.6  707.88   201.2  707.66   210.8  707.23   230.1  706.09
   249.3  704.56     259  704.31   268.6   706.7     277  711.65   285.5     717
     294  722.16   302.4     727   310.9  731.41   319.4  736.02   327.8  740.85
#Mann= 3 , 0 , 0
       0     .06       0     106    .045       0   143.4     .06       0
#XS Ineff= 2 , 0
                          190.35          707.91
Permanent Ineff=
       F       F
Bank Sta=106,143.4
XS Rating Curve= 0 ,0
Exp/Cntr=0.3,0.1

Type RM Length L Ch R = 1 ,28569.3 ,120.6,118.8,117.1
XS GIS Cut Line= 5
      1578347.63      383632.725     1578318.334      383541.579
     1578304.228      383505.771     1578276.016      383474.304
     1578073.108      383360.372
#Sta/Elev= 30
       0   723.9    28.7  718.12    38.3  716.46      67  712.33    76.6  711.51
    95.7  710.51   134.2  709.58   151.1  708.71   176.5  705.58   195.9  703.91
   205.6  702.37   215.3  699.56     221 697.521     225  696.09   234.7  694.38
   244.4  693.72     254  694.89   263.8  698.32   273.4  701.72   283.1  703.95
   302.5  706.81   321.9  708.57   341.3  709.15     351  708.71   360.7  707.42
   370.4  705.45   380.1  706.44   389.8  717.15   399.5  728.51   409.2  737.53
#Mann= 3 , 0 , 0
       0     .06       0     221    .045       0   263.8     .08       0
#XS Ineff= 2 , 0
                           341.9          709.52
Permanent Ineff=
       F       F
Bank Sta=221,263.8
XS Rating Curve= 0 ,0
Exp/Cntr=0.3,0.1

Type RM Length L Ch R = 1 ,27733.4 ,225.5,223.2,220.7
XS GIS Cut Line= 5
     1578880.409      383080.811     1578734.676      382848.499
     1578466.454      382728.417     1578401.884      382674.608
     1578102.405      382758.159
#Sta/Elev= 30
       0  901.37     9.8  900.31    29.4  896.14   235.1  842.34   254.6  836.08
   274.2  828.09   323.2  813.92     382  794.58   411.4  786.54     431     782
   470.2  775.81   509.3  768.21   528.9  763.42   596.1  732.36   633.5  716.12
   661.9  701.95   671.6  698.63     715 692.739   739.6  690.47     754 690.804
   797.9  694.59   807.6   696.4   817.3  699.95   827.1  704.92   836.8  708.02
   846.5  708.83   875.6  704.19   914.5  704.24   943.6  709.02   963.1  715.35
#Mann= 3 , 0 , 0
       0     .08       0     715    .045       0     754     .09       0
#XS Ineff= 2 , 0
                          842.34           713.9
Permanent Ineff=
       F       F
Bank Sta=715,754
XS Rating Curve= 0 ,0
Exp/Cntr=0.3,0.1

Type RM Length L Ch R = 1 ,27214.9 ,180.8,179.6,178.4
XS GIS Cut Line= 4
     1578168.603      382095.568     1578093.073       382219.53
     1577898.629      382394.877     1577837.865      382441.752
#Sta/Elev= 30
       0  792.68    96.8  736.75   145.2  708.31   154.9  702.98   164.6  698.04
   174.2  695.17     184  693.59   212.7  691.24   222.7  691.07     244 692.571
   261.5  694.28   271.2   695.7   280.9  697.71   300.3  702.86     310  705.04
   319.7  705.88   329.4   705.7   339.1  704.19   348.8  701.23   358.5     699
   368.2  699.03   397.3  702.99     407  704.53   416.6  707.46   426.2  713.68
   445.4  727.74     455  733.37   464.6   737.5   474.1  738.55   483.7  738.59
#Mann= 3 , 0 , 0
       0      .1       0   212.7    .045       0     244      .1       0
#XS Ineff= 2 , 0
                          321.08          710.61
Permanent Ineff=
       F       F
Bank Sta=212.7,244
XS Rating Curve= 0 ,0
Exp/Cntr=0.3,0.1

Type RM Length L Ch R = 1 ,25748.9 ,163.2,161.3,166.2
XS GIS Cut Line= 6
     1577149.641      381810.459     1577067.119      381734.325
     1576984.711      381760.546     1576787.228      381775.737
     1576693.912      381836.501     1576361.881      382264.018
#Sta/Elev= 30
       0  722.88    28.1  710.75    37.4   707.3    46.8  705.19   169.9   701.3
     253  696.81   299.4  696.75   362.6   699.3   406.6  699.29     453  695.69
   480.8  692.06   508.7  688.82   518.5  689.18     548  692.15   577.6  691.99
   597.2  693.14   607.1  694.59   626.8  698.83   636.6  699.83   646.4  699.92
     676  695.35   715.3   694.9   774.4   697.6   813.8  700.18   853.1   701.6
   941.7  706.71   961.4  709.68   990.9  717.22  1010.6  722.67    1050  735.39
#Mann= 3 , 0 , 0
       0     .06       0   480.8    .045       0     548     .06       0
#XS Ineff= 2 , 0
          366.29   705.5  646.74           706.3
Permanent Ineff=
       F       F
Bank Sta=480.8,548
XS Rating Curve= 0 ,0
Exp/Cntr=0.3,0.1

Type RM Length L Ch R = 1 ,25587.6 ,469.7,503.4,536.3
XS GIS Cut Line= 5
     1577184.364      381806.119     1577080.197       381667.23
     1576622.298      381695.442     1576368.391      381888.584
     1576240.353      382268.358
#Sta/Elev= 30
       0  728.76     9.6  724.97    38.6  711.08    48.2  707.19    57.9     705
   154.3  701.55   241.9  696.52   368.8  695.31   466.4  696.37   632.4  695.19
     642  693.96   661.4  690.37     671  689.44   680.7     691     700  695.33
   709.7  696.39   806.4  695.75   874.1   696.7   883.7  697.16   912.7  702.02
   932.1  703.05   941.7  702.06   951.4  699.95   961.2  696.54     971  695.68
   980.7  695.72  1254.4  705.35  1264.2  708.05  1313.1  731.62  1352.2  747.88
#Mann= 3 , 0 , 0
       0     .06       0   632.4    .045       0     700     .06       0
#XS Ineff= 2 , 0
                             933          707.53
Permanent Ineff=
       F       F
Bank Sta=632.4,700
XS Rating Curve= 0 ,0
Exp/Cntr=0.3,0.1

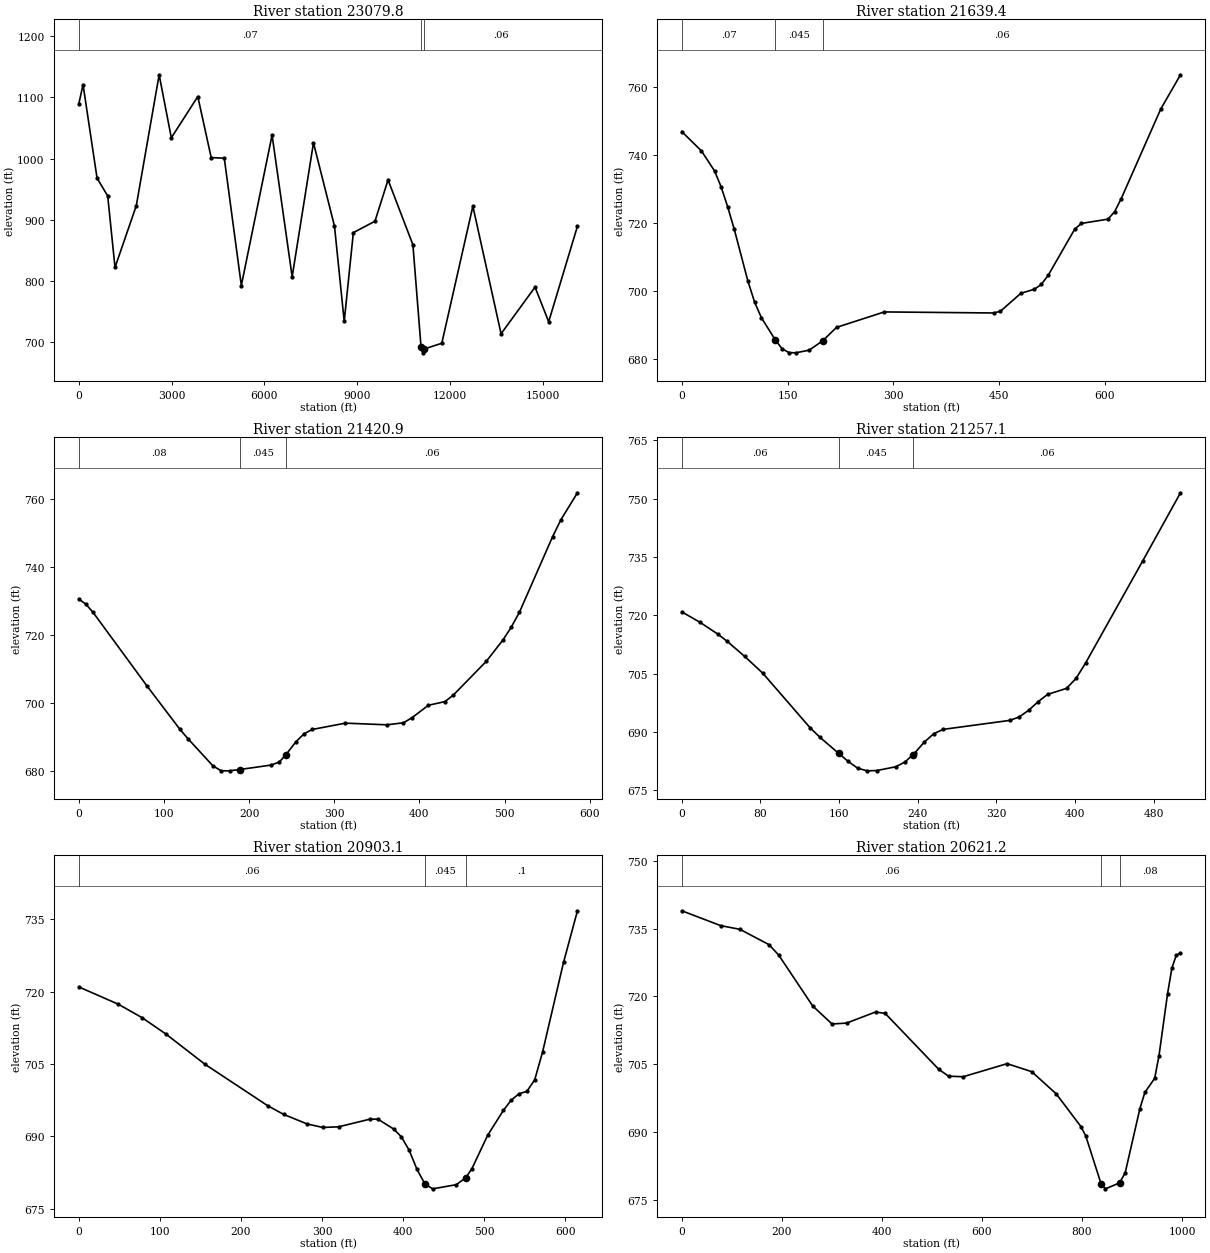
Type RM Length L Ch R = 1 ,23079.8 ,388.4,387,383.8
XS GIS Cut Line= 6
     1586737.947      374130.782     1579913.335       377479.89
     1577655.284      379944.573     1576086.334      381066.577
      1575132.29      382688.786      1574004.28       383357.46
#Sta/Elev= 30
       0 1089.23   137.7 1120.84   590.1  968.06   934.3  938.95  1170.3  822.18
  1858.7  923.22  2596.3 1136.89  2989.7 1033.95  3845.3 1101.33    4278 1001.62
  4700.9 1000.62  5251.6  792.67  6244.9 1038.38    6894  806.92  7582.4 1025.71
    8261  889.74  8575.7  733.96  8870.8  879.04  9569.1  897.67    9992  965.18
 10794.8  859.2211058.78  691.62 11114.1  682.69   11163 689.015 11728.2  698.35
 12732.1  922.14 13643.4  713.84 14741.2  790.02 15181.7  733.42 16111.3  889.56
#Mann= 3 , 0 , 0
       0     .07       011058.78    .045       0   11163     .06       0
Bank Sta=11058.78,11163
XS Rating Curve= 0 ,0
Exp/Cntr=0.3,0.1

Type RM Length L Ch R = 1 ,21639.4 ,125.9,128.9,129
XS GIS Cut Line= 5
     1576582.512      379100.968     1576508.727      379109.649
     1576165.845      379393.937      1576079.04      379430.829
     1575985.724       379435.17
#Sta/Elev= 30
       0  746.83    27.9  741.16    46.4  735.31    55.7  730.67      65  724.78
    74.3  718.24    93.7  702.99   103.3  696.76     113  692.17   132.4  685.76
   142.1  683.12   151.8  681.99   161.4   681.9   180.8  682.69     200 685.462
   219.5  689.38   287.3  693.91   442.2   693.6   451.9  694.09     481  699.38
   500.3  700.58     510     702   519.7  704.65   557.4  718.22   566.9  719.89
   604.6  721.14     614  723.34   623.4   727.2   679.4  753.46   707.4  763.52
#Mann= 3 , 0 , 0
       0     .07       0   132.4    .045       0     200     .06       0
Bank Sta=132.4,200
XS Rating Curve= 0 ,0
Exp/Cntr=0.3,0.1

Type RM Length L Ch R = 1 ,21420.9 ,162.9,163.8,164.6
XS GIS Cut Line= 3
     1576421.922      378953.399     1576376.349        378975.1
     1575946.661      379294.111
#Sta/Elev= 30
       0  730.68     8.4  729.14    16.8  726.73    79.7   705.2   118.6  692.34
   128.3   689.5   157.5  681.53   167.2  680.07     177  680.06     189 680.448
   225.6  681.75   235.4  682.64     243 684.748   254.8  688.57   264.5  690.97
   274.3  692.26   313.2  694.11   361.8  693.62   381.3  694.22     391  695.66
   410.5  699.37     430  700.46   439.7  702.35   478.6  712.34   498.1  718.62
   507.8  722.36   517.5  726.81   556.4  749.04   566.2  754.05   585.6  761.98
#Mann= 3 , 0 , 0
       0     .08       0     189    .045       0     243     .06       0
Bank Sta=189,243
XS Rating Curve= 0 ,0
Exp/Cntr=0.3,0.1

Type RM Length L Ch R = 1 ,21257.1 ,346.7,354,361.1
XS GIS Cut Line= 3
     1576309.074      378864.423     1576230.949      378890.465
     1575879.387       379129.18
#Sta/Elev= 30
       0  720.87    18.3  718.22    36.6  715.16    45.8  713.37      64  709.41
    82.4  705.09   130.6  691.04   140.3  688.67   159.6  684.47   169.3   682.4
   178.9  680.67   188.6  679.99   198.2  680.06   217.6  681.03   227.2   682.3
     235 684.117   236.9  684.56   246.5  687.34   256.2  689.52   265.8  690.65
   333.5  692.96   343.1  693.83   352.8  695.55   362.4  697.76   372.1  699.64
   391.4   701.2   401.1  703.78   410.7  707.69   468.7  733.89   507.3   751.5
#Mann= 3 , 0 , 0
       0     .06       0   159.6    .045       0     235     .06       0
Bank Sta=159.6,235
XS Rating Curve= 0 ,0
Exp/Cntr=0.3,0.1

Type RM Length L Ch R = 1 ,20903.1 ,279.4,281.9,284.2
XS GIS Cut Line= 4
     1576265.672      378740.725     1576144.144      378643.069
     1575747.008      378766.767     1575714.456      378794.979
#Sta/Elev= 30
       0  720.95    48.7  717.37      78  714.59   107.2  711.22   155.9  704.89
   233.3  696.31   252.6  694.55   281.7  692.56     301  691.84   320.4  691.98
     359  693.56   368.7  693.58   388.1  691.54   397.7  689.92   407.4  687.11
   417.1  683.14   426.8  680.14   436.4  679.13   465.4  679.99     477 681.406
   484.8  683.32   504.1   690.2   523.5  695.37   533.2   697.5   542.8  698.81
   552.5  699.32   562.2  701.71   571.9  707.47   597.7  726.01   614.9  736.72
#Mann= 3 , 0 , 0
       0     .06       0   426.8    .045       0     477      .1       0
Bank Sta=426.8,477
XS Rating Curve= 0 ,0
Exp/Cntr=0.3,0.1

Type RM Length L Ch R = 1 ,20621.2 ,376.5,373.6,370.8
XS GIS Cut Line= 5
     1576487.026      378486.819     1576070.769      378302.738
     1575937.981      378445.586     1575647.182      378495.499
     1575599.439      378515.031
#Sta/Elev= 30
       0  738.94    77.5  735.66   116.2  734.83   174.3  731.44   193.7  729.13
   261.5  717.88   300.2  713.88   329.2  714.07   387.4  716.54   406.7   716.2
   513.6  703.84   533.2  702.32   562.4   702.2   650.2  705.09   699.4  703.32
   748.5   698.4   797.7  691.18   807.5  689.08     838 678.513   846.9  677.38
     875   678.7   886.2   680.9   915.7  695.16   925.6  698.73   945.2  701.84
   953.8  706.83     971  720.61   979.6  726.23   988.2  729.04   996.8   729.6
#Mann= 3 , 0 , 0
       0     .06       0     838    .045       0     875     .08       0
Bank Sta=838,875
XS Rating Curve= 0 ,0
Exp/Cntr=0.3,0.1

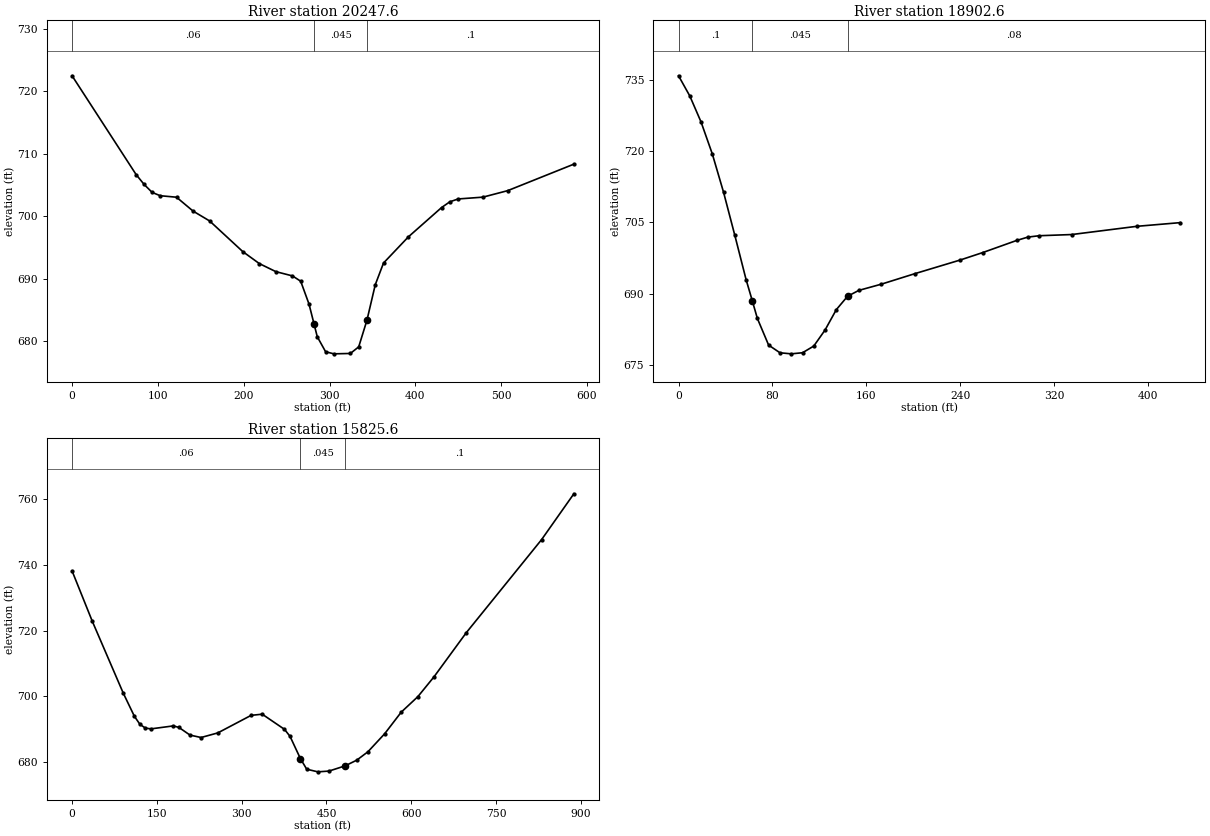
Type RM Length L Ch R = 1 ,20247.6 ,417.7,389.2,360.5
XS GIS Cut Line= 4
      1575924.96      377996.367     1575833.814      378061.472
     1575510.463      378159.128     1575447.529      378278.486
#Sta/Elev= 30
       0  722.49    74.7  706.67      84   705.1    93.3  703.83   102.7   703.3
   121.7  703.06     141  700.84   160.3  699.26   198.9  694.36   218.2  692.44
   237.5  691.15   256.8  690.47   266.4  689.62   276.1  685.96     282 682.752
   285.7  680.74   295.4  678.34     305     678   324.3  678.06     334  679.12
   343.6  683.38   353.3  689.06   362.9  692.53   391.9  696.72   430.5   701.4
   440.1  702.32   449.8  702.78   478.7  703.07   507.6  704.11   584.7  708.35
#Mann= 3 , 0 , 0
       0     .06       0     282    .045       0   343.6      .1       0
Bank Sta=282,343.6
XS Rating Curve= 0 ,0
Exp/Cntr=0.3,0.1

Type RM Length L Ch R = 1 ,18902.6 ,297.5,299.2,301
XS GIS Cut Line= 3
     1574622.876      378386.992     1574863.762      378577.965
     1574931.036      378677.791
#Sta/Elev= 28
       0  735.86     9.6  731.61    19.2  726.13    28.8   719.4    38.4  711.32
      48  702.25    57.6  692.93   62.89  688.48    67.2  684.77    76.8  679.15
    86.5  677.53    96.1  677.31   105.7  677.54   115.3  678.95   124.9  682.32
   134.5  686.61   144.1  689.43   153.7  690.67   172.9  691.98   201.7  694.21
   240.2  697.07   259.4  698.64   288.2  701.18   297.8  701.89   307.4  702.18
   335.2  702.43   390.7  704.16   427.8  704.94
#Mann= 3 , 0 , 0
       0      .1       0   62.89    .045       0   144.1     .08       0
Bank Sta=62.89,144.1
XS Rating Curve= 0 ,0
Exp/Cntr=0.3,0.1

Type RM Length L Ch R = 1 ,15825.6 ,187.9,186.3,184.6
XS GIS Cut Line= 4
     1574531.731      377358.347     1574483.987      377293.242
     1574015.237      377043.677     1573754.821      377134.822
#Sta/Elev= 30
       0  738.12    35.9  722.76    90.6  700.94   110.2  693.93   120.1  691.45
   129.9  690.31   139.7  690.09   179.1  690.99   188.9  690.54   208.6   688.2
   228.2  687.46   257.8  688.86   316.8   694.2   336.4  694.55   375.8  689.94
   385.6  687.81     404 681.021   415.1  677.82   434.8  677.02   454.4  677.25
     483 678.836   503.6  680.57   523.3  683.11   552.8  688.56   582.3  695.17
   611.8   699.9   640.3  705.92   697.4  719.34   830.6  747.64   887.7  761.58
#Mann= 3 , 0 , 0
       0     .06       0     404    .045       0     483      .1       0
Bank Sta=404,483
XS Rating Curve= 0 ,0
Exp/Cntr=0.3,0.1