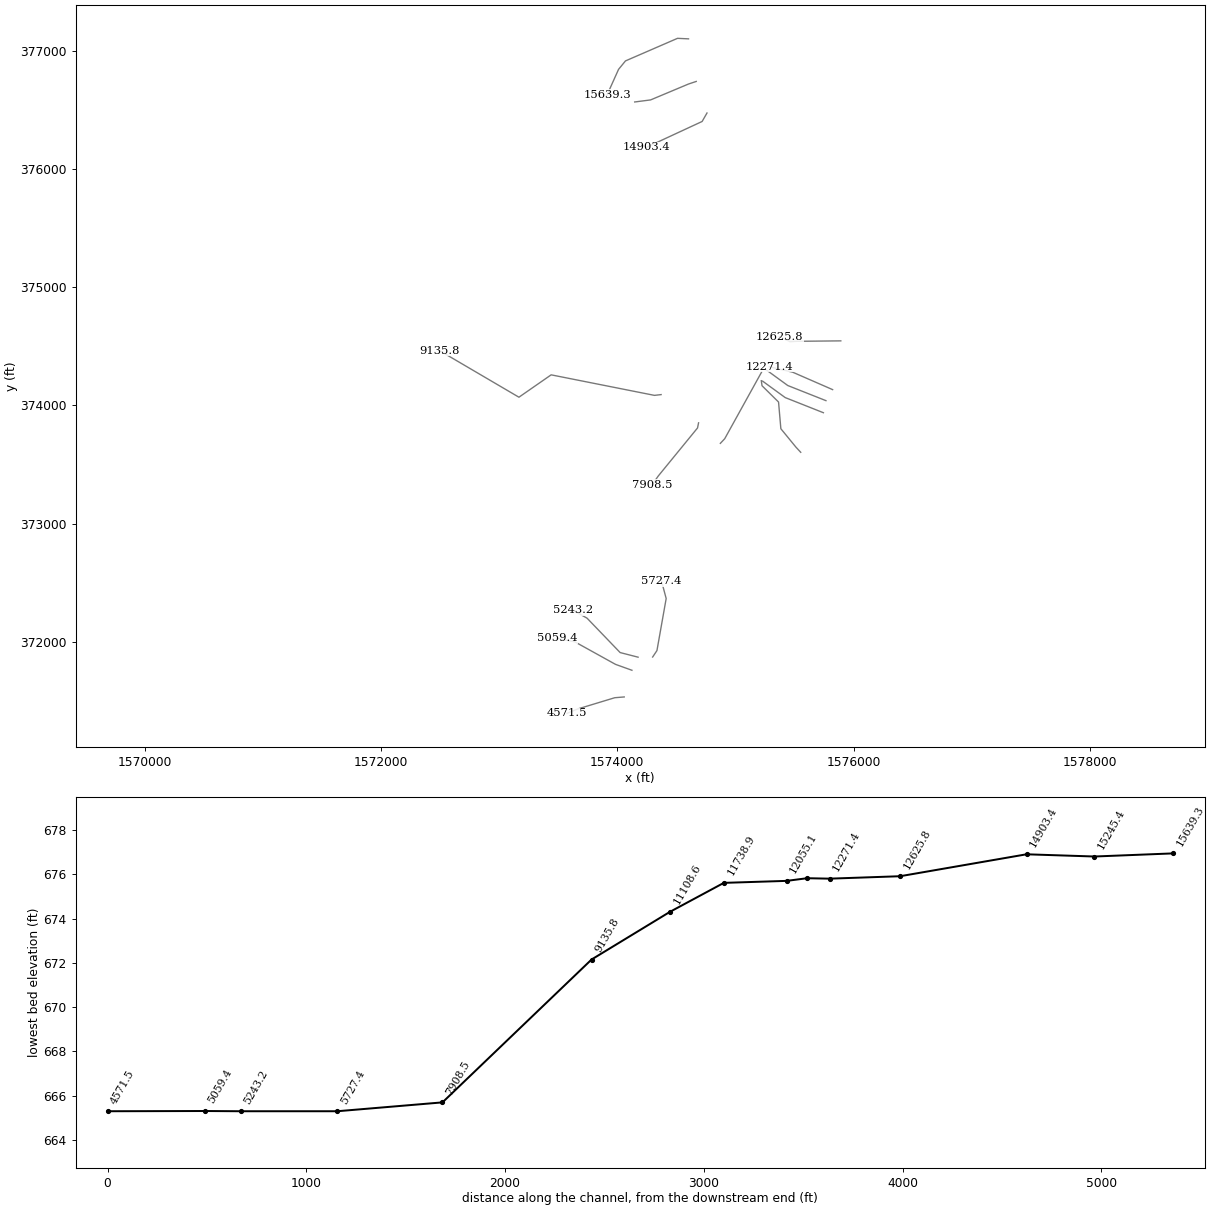
HEC-RAS study PTPLSCRK.prj: PTPLSCRK

--- PTPLSCRK.g02 (geometry) --- (continued)

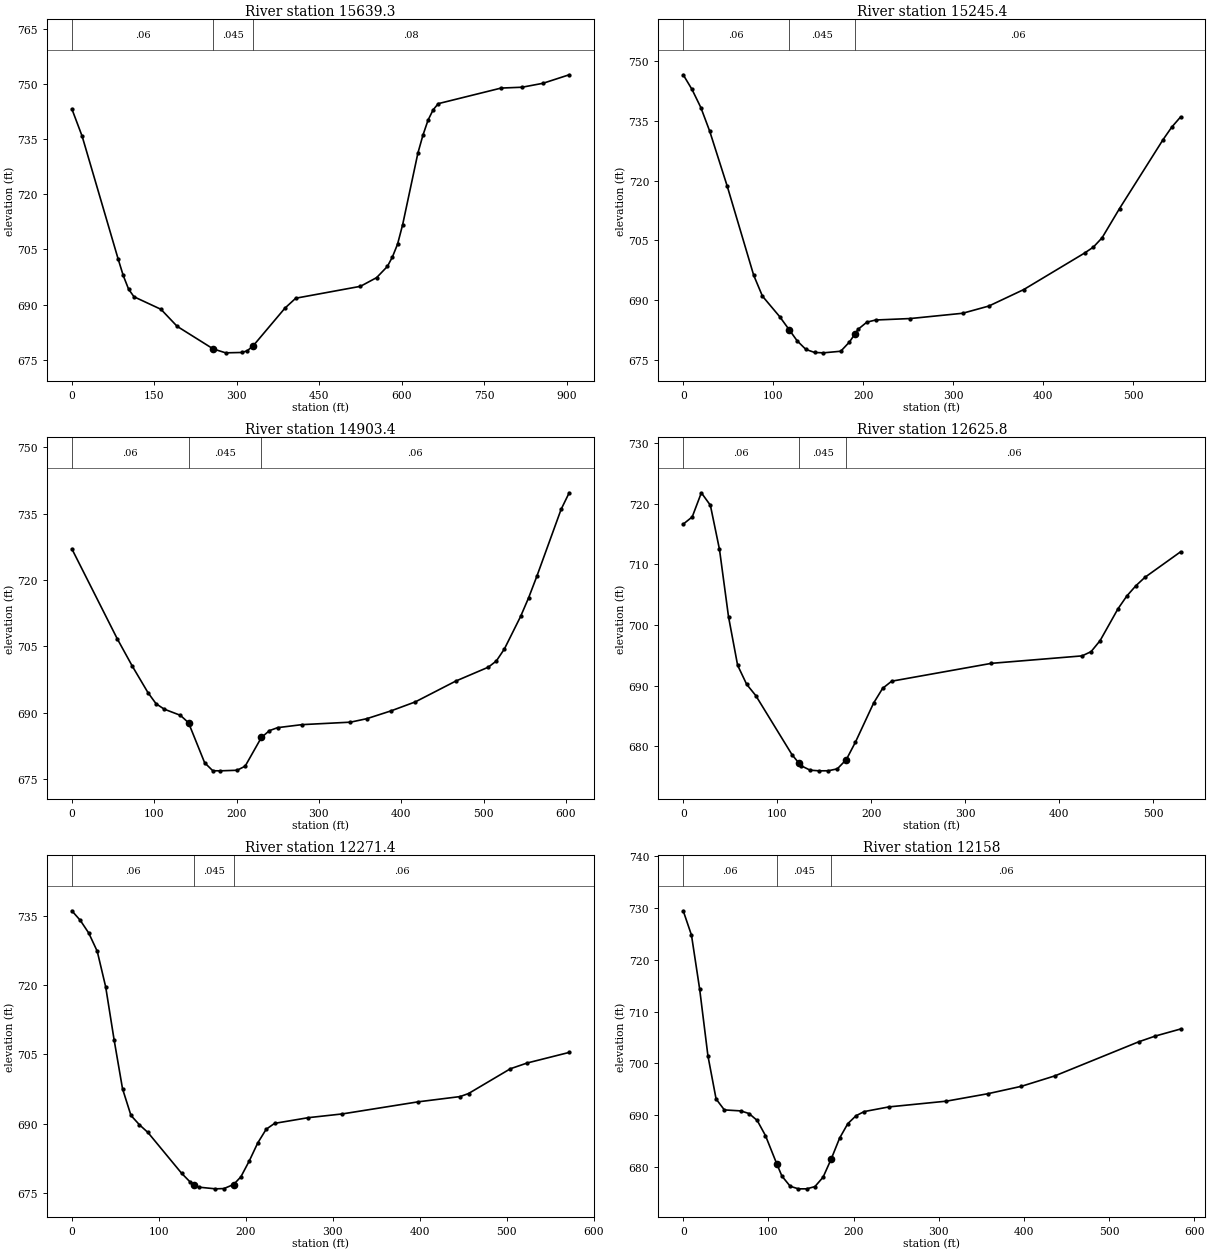
Type RM Length L Ch R = 1 ,15639.3 ,394,393.9,393.8
XS GIS Cut Line= 5
     1574603.345        377100.1     1574510.029       377104.44
     1574069.491      376913.468     1574010.897      376841.854
     1573913.241       376624.84
#Sta/Elev= 30
       0  743.18    18.7  735.76    84.1  702.45    93.4  697.94   103.2  694.22
     113  692.16     162  688.76   191.4  684.14     257 677.999   279.6  676.94
     309  677.04   318.8  677.49     330 678.911   387.4  689.08     407  691.77
   524.6     695     554  697.36   573.6   700.4   582.8  702.99   592.1  706.45
   601.3  711.71   629.1  731.19   638.3  736.07   647.6  740.15   656.8  742.93
   666.1   744.6   780.3  748.83   818.4  749.06   856.5  750.13   904.1  752.44
#Mann= 3 , 0 , 0
       0     .06       0     257    .045       0     330     .08       0
Bank Sta=257,330
XS Rating Curve= 0 ,0
Exp/Cntr=0.3,0.1

Type RM Length L Ch R = 1 ,15245.4 ,341.1,342,342.9
XS GIS Cut Line= 4
     1574668.449      376739.857     1574603.345      376718.156
     1574282.165      376583.607     1574147.616      376566.246
#Sta/Elev= 30
       0  746.51     9.8  742.83    19.6  738.29    29.4  732.39      49  718.51
    78.3  696.25      88  691.02   107.3  685.84     118 682.507   126.7  679.78
   136.3  677.66     146  676.89   155.7   676.8     175   677.2   184.7  679.52
     191 681.605   194.4  682.73     204  684.49   213.7  685.03   252.4   685.4
   310.4  686.72   339.5  688.53   378.2  692.65   445.9  701.82   455.6   703.3
   465.3  705.63   484.7  712.97   533.1  730.26   542.8  733.41   552.5  735.93
#Mann= 3 , 0 , 0
       0     .06       0     118    .045       0     191     .06       0
Bank Sta=118,191
XS Rating Curve= 0 ,0
Exp/Cntr=0.3,0.1

Type RM Length L Ch R = 1 ,14903.4 ,630.5,636.2,640.6
XS GIS Cut Line= 3
     1574759.595       376472.93     1574718.362      376401.315
     1574245.272      376182.131
#Sta/Elev= 30
       0  727.07    55.1  706.76    73.4  700.57    92.5  694.56   102.3  692.06
   112.2  690.84   131.8  689.45   141.7  687.77   161.3  678.72   171.2  676.92
     180   676.9   200.7  677.03   210.5  677.96   230.2  684.44     240  685.99
   249.9  686.66   279.4  687.34   338.4   687.9   358.1  688.68   387.6  690.45
   417.1  692.48   466.3  697.19   505.7  700.32   515.5  701.72   525.3  704.44
     545  711.79   554.8  716.04   564.7  720.86   594.2     736     604  739.74
#Mann= 3 , 0 , 0
       0     .06       0   141.7    .045       0   230.2     .06       0
Bank Sta=141.7,230.2
XS Rating Curve= 0 ,0
Exp/Cntr=0.3,0.1

Type RM Length L Ch R = 1 ,12625.8 ,363.7,354.3,344.6
XS GIS Cut Line= 3
     1575892.408      374545.847      1575458.38      374541.506
     1575371.574      374580.569
#Sta/Elev= 30
       0  716.64     9.6  717.84    19.3  721.82    28.9  719.76    38.6  712.47
    48.2  701.37    57.9  693.34    67.5   690.2    77.2  688.34   115.8  678.57
     123 677.213   125.4  676.76     135  676.02   144.7  675.91   154.3  675.92
     164  676.24   173.6  677.78   183.3  680.66   202.6   687.1   212.2  689.53
   221.8  690.71     328  693.66   424.4  694.89     434  695.59   443.6  697.41
   462.6  702.66   472.1  704.79   481.6  706.46   491.2  707.85   529.2  712.07
#Mann= 3 , 0 , 0
       0     .06       0     123    .045       0   173.6     .06       0
Bank Sta=123,173.6
XS Rating Curve= 0 ,0
Exp/Cntr=0.3,0.1

Type RM Length L Ch R = 1 ,12271.4 ,112.7,113.4,114.3
XS GIS Cut Line= 3
     1575822.963       374133.52     1575484.422       374281.09
     1575286.939      374326.663
#Sta/Elev= 30
       0  736.23     9.7  734.15    19.4   731.4    29.2  727.43    38.9  719.71
    48.6  708.19    58.3  697.54      68  691.75    77.8  689.71    87.5  688.05
   126.3  679.17   136.1  677.28     141 676.719   145.8  676.17   165.2   675.8
   174.9  675.86     186 676.739   194.4  678.41   204.1  681.88   213.8  685.77
   223.5  688.75   233.2  690.03   272.1  691.27     311  692.08   398.3  694.71
   446.5  695.85   456.2  696.51   504.4   701.9   523.7  703.15     572  705.45
#Mann= 3 , 0 , 0
       0     .06       0     141    .045       0     186     .06       0
Bank Sta=141,186
XS Rating Curve= 0 ,0
Exp/Cntr=0.3,0.1

Type RM Length L Ch R = 1 ,12158   ,102.9,102.9,102.9
XS GIS Cut Line= 3
      1575766.54      374040.204     1575443.189      374168.242
     1575252.217      374307.131
#Sta/Elev= 30
       0  729.44     9.7  724.75    19.3  714.35      29  701.49    38.6  693.15
    48.3  691.04    67.6  690.85    77.3  690.34    86.9     689    96.6  686.08
     110 680.572   115.9  678.28   125.6  676.32   135.2  675.82   144.9  675.82
   154.6  676.25   164.2  678.06   173.9  681.63   183.6  685.59   193.2  688.38
   202.9  689.92   212.5  690.72   241.5  691.62   309.1  692.73   357.6  694.16
     397  695.59   436.3   697.6   534.7  704.17   554.4  705.29   583.9  706.64
#Mann= 3 , 0 , 0
       0     .06       0     110    .045       0   173.9     .06       0
Bank Sta=110,173.9
XS Rating Curve= 0 ,0
Exp/Cntr=0.3,0.1

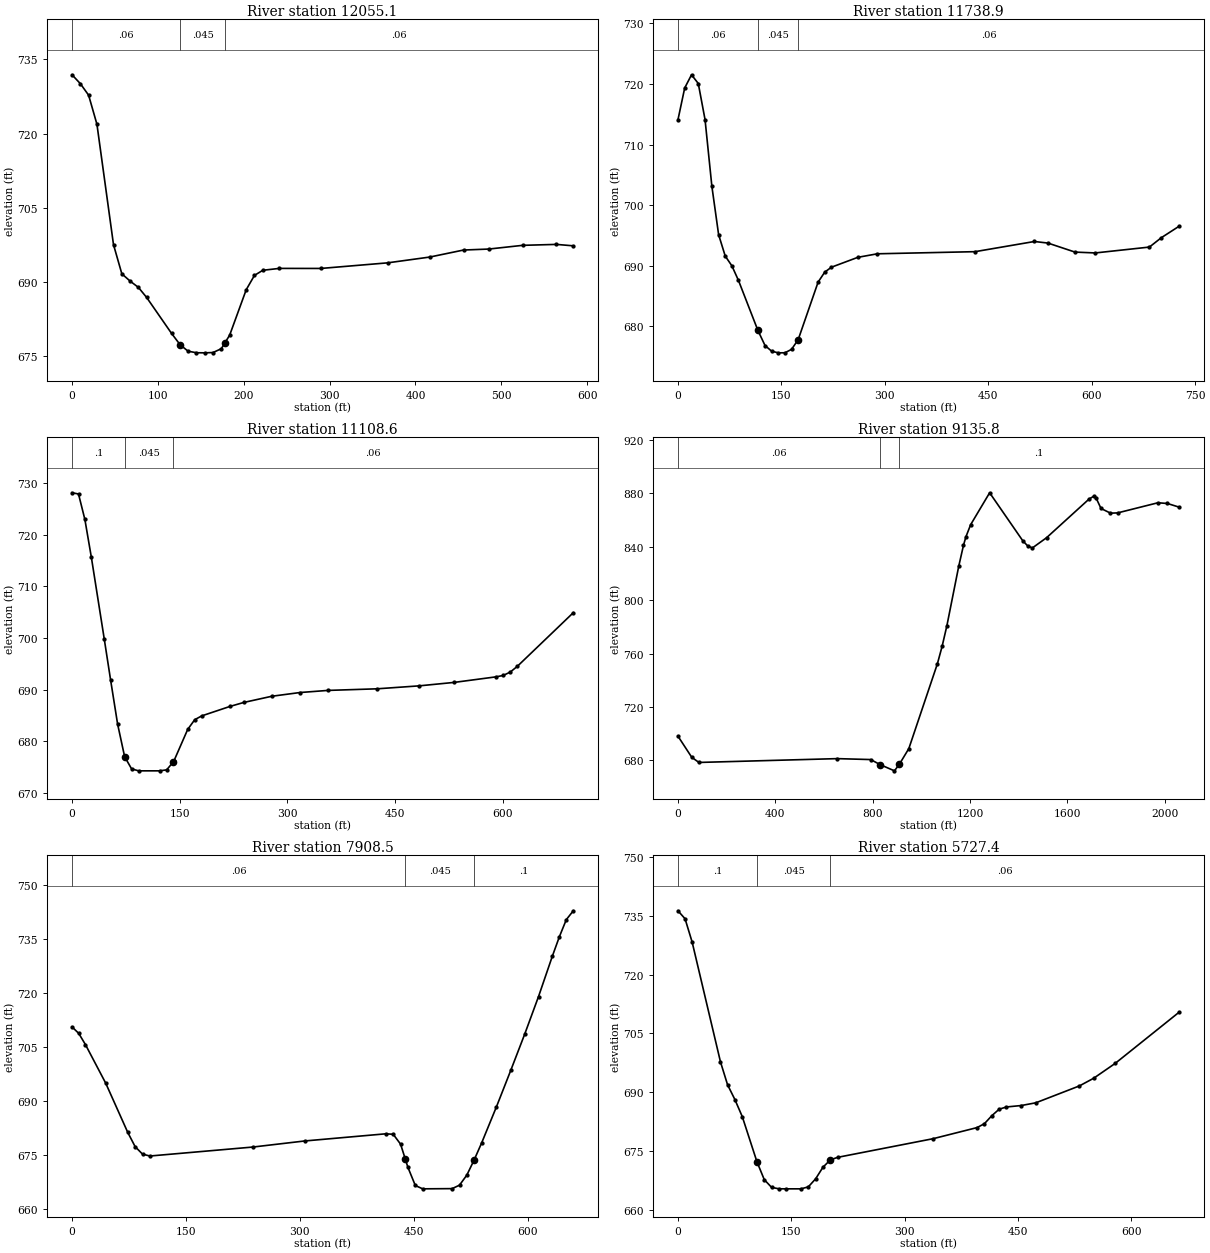
Type RM Length L Ch R = 1 ,12055.1 ,327.3,316.2,304.1
XS GIS Cut Line= 3
     1575744.838      373938.208     1575421.487      374066.246
     1575230.515      374205.135
#Sta/Elev= 30
       0  731.88     9.7  730.08    19.3  727.76      29  721.88    48.3  697.55
      58  691.67    67.6   690.2    77.3  688.92    86.9  686.89   115.9  679.63
     126 677.314   135.2  676.03   144.9  675.72   154.6   675.7   164.2  675.76
   173.9  676.54     178 677.694   183.6  679.27   202.9  688.46   212.5  691.35
   222.2  692.38   241.5  692.76   289.8  692.75   367.5  693.88   416.6  695.05
     456  696.47   485.5  696.67   524.9  697.42   564.2  697.61   583.9  697.32
#Mann= 3 , 0 , 0
       0     .06       0     126    .045       0     178     .06       0
Bank Sta=126,178
XS Rating Curve= 0 ,0
Exp/Cntr=0.3,0.1

Type RM Length L Ch R = 1 ,11738.9 ,286.2,271.6,257.8
XS GIS Cut Line= 6
      1575553.05      373603.388      1575512.85      373646.541
     1575384.812      373802.791     1575365.281      374028.486
     1575225.415      374166.264     1575219.283      374208.965
#Sta/Elev= 30
       0  714.07     9.8  719.33    19.7  721.51    29.5  720.07    39.3  714.12
    49.2  703.11      59  695.11    68.6  691.58    78.2  689.98    87.8  687.56
     116 679.301   126.3  676.82   135.9  675.88   145.6  675.61   155.2  675.62
   164.8  676.19   174.4  677.79   203.3  687.29   212.9  688.93   222.5  689.74
     261  691.38   289.3  691.96   430.9  692.31     517  693.99   536.6  693.73
   575.9  692.24   605.3   692.1   683.8  693.07   701.1  694.62     727  696.52
#Mann= 3 , 0 , 0
       0     .06       0     116    .045       0   174.4     .06       0
Bank Sta=116,174.4
XS Rating Curve= 0 ,0
Exp/Cntr=0.3,0.1

Type RM Length L Ch R = 1 ,11108.6 ,397.8,394,390
XS GIS Cut Line= 3
     1574872.659      373679.093     1574909.552      373718.156
     1575222.052      374282.392
#Sta/Elev= 30
       0  728.13       9   727.9    17.9  722.96    26.9  715.66    44.8  699.91
    53.7  691.93    63.5  683.36    73.3  677.04      83  674.68    92.8   674.3
   122.1   674.3   131.9  674.49     141 676.004   141.7  676.12   161.2  682.32
     171   684.2   180.8  684.94   219.9  686.76   239.4  687.54   278.5  688.74
   317.6  689.46   356.7  689.87   425.1  690.18   483.7  690.75   532.6  691.42
   591.2   692.5     601  692.77   610.8  693.42   620.5  694.51   698.7  704.92
#Mann= 3 , 0 , 0
       0      .1       0    73.3    .045       0     141     .06       0
Bank Sta=73.3,141
XS Rating Curve= 0 ,0
Exp/Cntr=0.3,0.1

Type RM Length L Ch R = 1 ,9135.8  ,727.9,750.1,771.6
XS GIS Cut Line= 5
     1574371.357       374091.42     1574314.934      374084.909
     1573440.368       374258.52     1573167.715      374069.375
     1572495.887      374463.085
#Sta/Elev= 30
       0  698.16    56.8  682.29    86.2  678.44   654.5   681.3   791.7   680.6
     831 676.766   889.3  672.15   909.2  676.98   948.4  688.83  1065.6  752.32
  1085.1  765.43  1104.6  780.81  1153.4   825.5  1172.9  841.17  1182.7  847.42
  1202.2  856.57  1280.3  880.52  1416.5  844.54    1436  840.83  1455.5  839.14
  1513.9  846.81  1689.1  875.88  1708.6  877.99  1718.3  876.32  1737.8  868.76
  1776.7  865.25  1805.9  865.44  1971.4  873.03  2010.3  872.51    2059  869.74
#Mann= 3 , 0 , 0
       0     .06       0     831    .045       0   909.2      .1       0
Bank Sta=831,909.2
XS Rating Curve= 0 ,0
Exp/Cntr=0.3,0.1

Type RM Length L Ch R = 1 ,7908.5  ,531.7,529.1,526.5
XS GIS Cut Line= 4
     1574688.198      373852.704     1574679.517      373809.302
     1574347.486      373403.486     1574294.751      373328.616
#Sta/Elev= 30
       0  710.69     8.8   708.9    17.7  705.76    44.3  695.08    73.4  681.37
    83.1  677.42    92.8  675.35   102.5  674.82   238.5  677.32   306.4     679
   413.2  680.99     423  680.86   432.7  678.11     439 673.914   442.4  671.65
   452.1  666.63   461.8   665.7   500.6  665.76   510.3  666.72     520  669.53
   529.8  673.83   539.5  678.47   558.9  688.46   577.8  698.61   596.1  708.64
   614.4  719.14   632.7  730.41   641.9  735.78     651  740.51   660.2  742.96
#Mann= 3 , 0 , 0
       0     .06       0     439    .045       0   529.8      .1       0
Bank Sta=439,529.8
XS Rating Curve= 0 ,0
Exp/Cntr=0.3,0.1

Type RM Length L Ch R = 1 ,5727.4  ,461.3,484.3,505.8
XS GIS Cut Line= 4
     1574299.526      371872.019     1574335.984      371926.706
     1574414.109       372366.81     1574375.047      372512.644
#Sta/Elev= 30
       0  736.34     9.4  734.31    18.8  728.35    56.3  697.75    65.7  691.89
    75.4  688.11    85.2  683.74   104.6  672.22   114.3  667.65     124  665.67
   133.8  665.31   142.7   665.3   162.9   665.3   172.6   665.8   182.3  667.86
     192  670.82   201.8   672.7   211.5  673.35   337.8  678.11   396.1  680.95
   405.8  681.95   415.5  683.97   425.3  685.65     435  686.22   454.4  686.58
   473.8  687.28   531.6   691.6   550.4  693.55   578.8  697.33   663.7  710.45
#Mann= 3 , 0 , 0
       0      .1       0   104.6    .045       0   201.8     .06       0
Bank Sta=104.6,201.8
XS Rating Curve= 0 ,0
Exp/Cntr=0.3,0.1

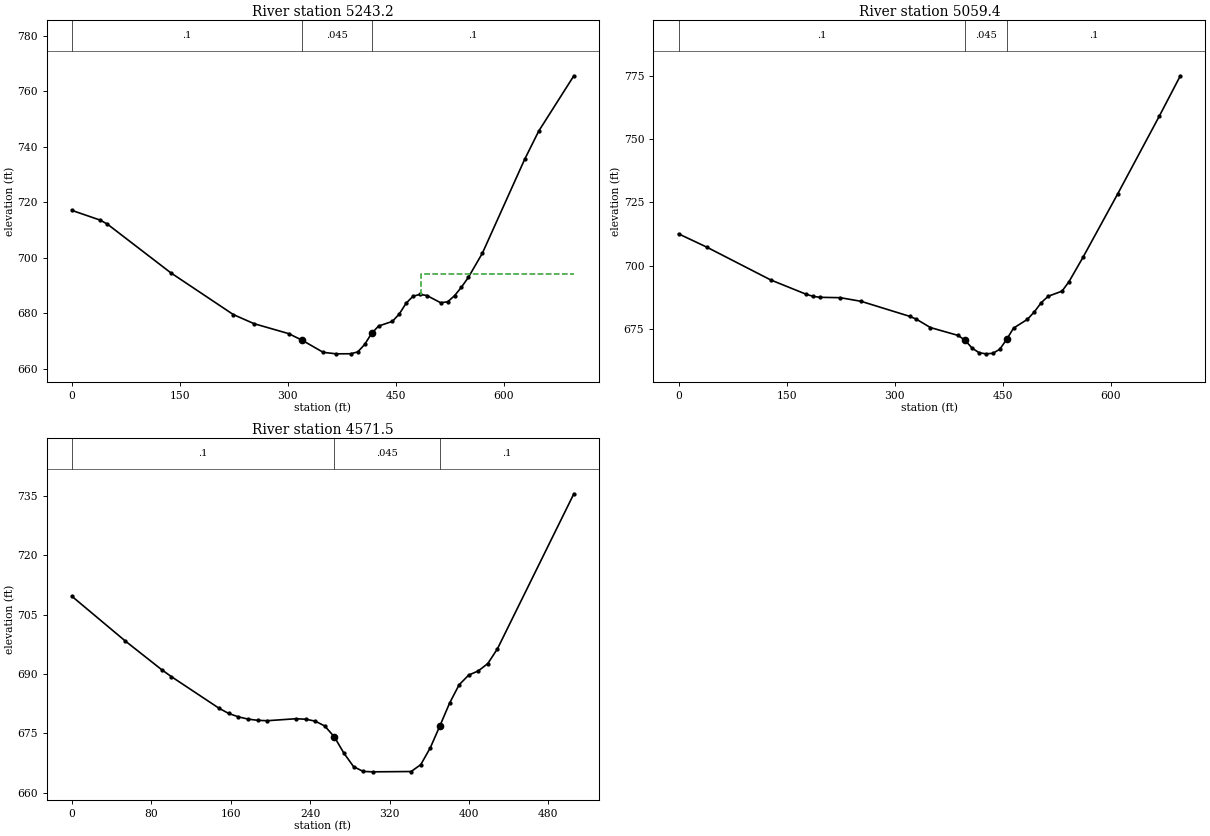
Type RM Length L Ch R = 1 ,5243.2  ,178.6,183.7,190.1
XS GIS Cut Line= 4
     1574176.262      371870.716     1574024.352      371909.779
     1573744.404      372200.578     1573625.047      372267.852
#Sta/Elev= 30
       0  717.05    39.2  713.55      49  712.13   137.2  694.55   224.1  679.48
     253  676.18     301   672.6   320.2  670.15   349.1  665.84   367.3   665.3
   387.5  665.33   397.1     666   406.7  668.68   416.3  672.65     426  675.33
   445.2     677   454.8  679.67   464.4   683.6     474  686.09   483.6  686.75
   493.2  686.35   512.4  683.73   522.1  684.09   531.7  686.29   541.3  689.38
   550.9  692.92   570.3   701.6     629  735.44   648.6  745.66   697.5  765.65
#Mann= 3 , 0 , 0
       0      .1       0   320.2    .045       0   416.3      .1       0
#XS Ineff= 2 , 0
                          484.84             694
Permanent Ineff=
       F       F
Bank Sta=320.2,416.3
XS Rating Curve= 0 ,0
Exp/Cntr=0.3,0.1

Type RM Length L Ch R = 1 ,5059.4  ,469.8,487.9,506.2
XS GIS Cut Line= 4
     1574124.178      371760.039      1573985.29      371809.953
     1573640.237      372000.925     1573488.328      372029.137
#Sta/Elev= 30
       0  712.61    39.4  707.34   127.9  694.44   176.4  688.88   186.1  688.02
   195.7  687.59   224.5  687.44   253.4  686.01   320.7   680.1   330.3  678.94
   349.6  675.67   388.1  672.56   397.7  670.66   407.3  667.63   416.9  665.79
   426.5  665.31   436.2  665.52   445.8  667.09   455.4  670.99     465  675.45
   484.2  678.89   493.9  681.86   503.5  685.49   513.1     688   532.3  690.02
     542  693.77   561.3  703.31   609.6  728.37   667.5  759.09   696.5   774.9
#Mann= 3 , 0 , 0
       0      .1       0   397.7    .045       0   455.4      .1       0
Bank Sta=397.7,455.4
XS Rating Curve= 0 ,0
Exp/Cntr=0.3,0.1

Type RM Length L Ch R = 1 ,4571.5  ,449.1,451.6,453.6
XS GIS Cut Line= 4
     1574059.074      371534.345     1573978.779      371527.834
     1573664.109      371432.348     1573575.133      371395.456
#Sta/Elev= 30
       0  709.63    53.7  698.35    90.2  691.14    99.9  689.39   148.3  681.34
   157.9  680.05   167.6   679.2   177.3  678.63     187  678.32   196.6  678.22
   225.6  678.72   235.3   678.6     245  678.12   254.6   676.9   264.3  674.14
     274     670   283.7  666.61   293.3  665.41   302.8   665.3   341.7  665.38
   351.4  667.12     361  671.37   370.7  676.92   380.4  682.63     390  687.28
   399.7  689.75   409.4   690.8     419  692.67   428.7   696.4   505.7  735.57
#Mann= 3 , 0 , 0
       0      .1       0   264.3    .045       0   370.7      .1       0
Bank Sta=264.3,370.7
XS Rating Curve= 0 ,0
Exp/Cntr=0.3,0.1